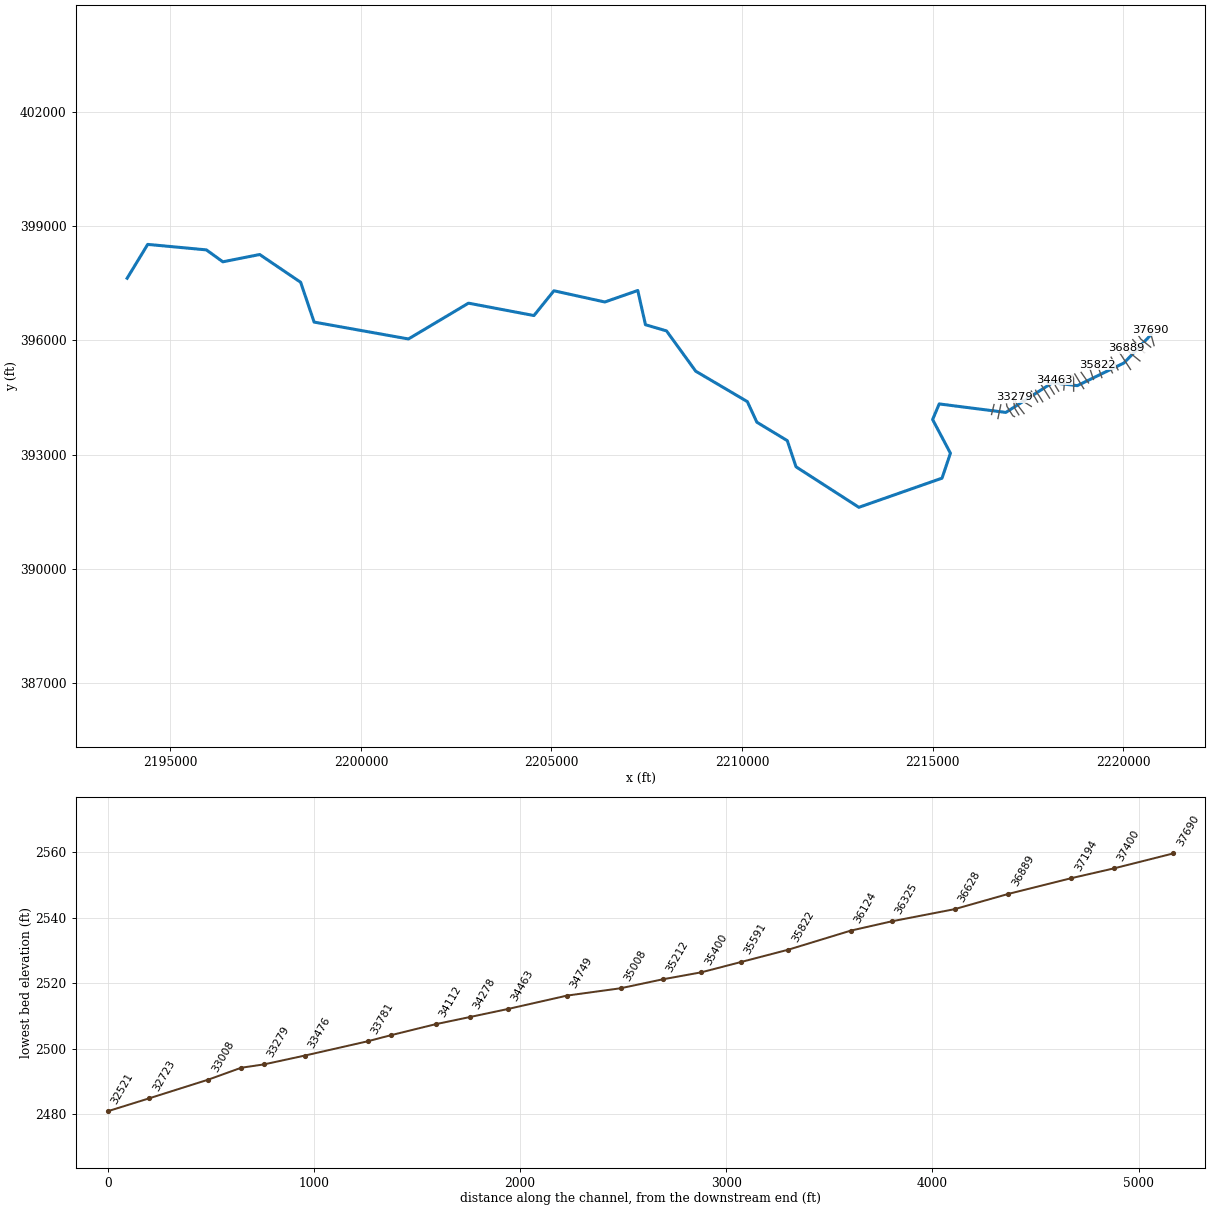
--- LAURELRN1.prj (project) ---

Proj Title=LAURELRN1
Current Plan=p01
Default Exp/Contr=0,0
English Units
Geom File=g01
Flow File=f01
Plan File=p01
Background Map Layer=Inundation Boundary (01pct Value_0)
Background Map Layer=Inundation Boundary (01pct Value_0)
Background Map Layer=Inundation Boundary (01pct Value_0)
Background Map Layer=Inundation Boundary (01pct Value_0)
BEGIN DESCRIPTION:
----------MODEL BY WOOD PLC 2021----------
Stream Name: Laurel Run I
Flood Zone: Enhanced Approximate
Pocahontas County, WV
HEC-RAS Version: RAS 6.1
Vertical Datum: NAVD88
Projection: NAD 1983 StatePlane West Virginia S FIPS 4702 (US Feet)
Terrain: 1-meter LIDAR (FEMA Region III 3DEP collected 2016-2018)
Land Use: 2019 NLCD
Hydrologic Method:
WV SIR2010-5033 regression equations
Model Notes:
Normal depth tie in.
END DESCRIPTION:
DSS Export Rating Curves= 0
DSS Export Rating Curve Sorted= 0
DSS Export Volume Flow Curves= 0
DXF OffsetX= 0
DXF OffsetY= 0
DXF ScaleX= 0
DXF ScaleY= 0

--- LAURELRN1.p01 (plan) ---

Plan Title=Floodplain
Program Version=6.10
Short Identifier=Floodplain
Geom File=g01
Flow File=f01
Subcritical Flow
K Sum by GR= 0
Std Step Tol= 0.01
Critical Tol= 0.01
Num of Std Step Trials= 20
Max Error Tol= 0.3
Flow Tol Ratio= 0.001
Split Flow NTrial= 30
Split Flow Tol= 0.02
Split Flow Ratio= 0.02
Log Output Level= 0
Friction Slope Method= 1
Unsteady Friction Slope Method= 2
Unsteady Bridges Friction Slope Method= 1
Parabolic Critical Depth
Global Vel Dist= 0 , 0 , 0
Global Log Level= 0
CheckData=False
Encroach Param=-1 ,0,0, 0
Mapping Interval=1HOUR
Computation Time Step Use Courant=        0
Computation Time Step Use Time Series=    0
Computation Time Step Count To Double=0
Computation Time Step Max Doubling=0
Computation Time Step Max Halving=0
Computation Time Step Residence Courant=0
Run HTab= 0
Run UNet= 0
Run Sediment= 0
Run PostProcess= 0
Run WQNet= 0
Run RASMapper=-1
UNET Theta= 0
UNET Theta Warmup= 0
UNET ZTol= 0
UNET ZSATol= 0
UNET MxIter= 0
UNET Max Iter WO Improvement= 0
UNET MaxInSteps= 0
UNET DtIC= 0
UNET DtMin= 0
UNET MaxCRTS= 0
UNET WFStab= 0
UNET SFStab= 0
UNET WFX= 1
UNET SFX= 1
UNET Gravity=32.174
UNET 1D Methodology=Finite Difference
UNET DSS MLevel= 1
UNET Pardiso=0
UNET DZMax Abort= 0
UNET Use Existing IB Tables= 0
UNET Froude Reduction=False
UNET Froude Limit= 0
UNET Froude Power= 0
UNET D1 Cores= 0
UNET WindReference=Eulerian
UNET WindDragFormulation=Hsu (1988)
UNET D2 Coriolis=0
UNET D2 Cores= 0
UNET D2 Theta= 1
UNET D2 Theta Warmup= 1
UNET D2 Z Tol= 0.01
UNET D2 Volume Tol= 0.01
UNET D2 Max Iterations= 20
UNET D2 Equation= 0
UNET D2 RampUpFraction=0.1
UNET D2 TimeSlices= 1
UNET D2 Turbulence Formulation=Non-Conservative (original)
UNET D2 Eddy Viscosity=0.3
UNET D2 Transverse Eddy Viscosity=0.1
UNET D2 Smagorinsky Mixing=0
UNET D2 BCVolumeCheck=0
UNET D2 Cores=0
UNET D2 SolverType=PARDISO (Direct)
UNET D2 Minimum Iterations= 2147483647
UNET D2 Maximum Iterations= 2147483647
UNET D2 Restart Number= 10
UNET D2 Relaxation Coeff=1.3
UNET D2 SOR Precondition Iterations= 10
UNET D2 ILUT Maximum Fill= 8
UNET D2 ILUT Tolerance=1E-08
UNET D1D2 MaxIter= 0
UNET D1D2 ZTol=0.01
UNET D1D2 QTol=0.1
UNET D1D2 MinQTol=1
Write IC File= 0
Write IC File at Fixed DateTime=0
Write IC File at Sim End=0
Echo Input=False
Echo Parameters=False
Echo Output=False
Write Detailed= 0
HDF Write Warmup=0
HDF Write Time Slices=0
HDF Flush=0
HDF Compression= 1
HDF Chunk Size= 1
HDF Spatial Parts= 1
HDF Use Max Rows=0
HDF Fixed Rows= 1
Calibration Method= 0
Calibration Iterations= 20
Calibration Max Change=0.05
Calibration Tolerance=0.2
Calibration Maximum=1.5
Calibration Minimum=0.5
Calibration Optimization Method= 1
WQ AD Non Conservative
WQ ULTIMATE=-1
WQ Max Comp Step=1HOUR
WQ Output Interval=15MIN
WQ Output Selected Increments= 0
WQ Output face flow=0
WQ Output face velocity=0
WQ Output face area=0
WQ Output face dispersion=0
WQ Output cell volume=0
WQ Output cell surface area=0
WQ Output cell continuity=0
WQ Output cumulative cell continuity=0
WQ Output face conc=0
WQ Output face dconc_dx=0
WQ Output face courant=0
WQ Output face peclet=0
WQ Output face adv mass=0
WQ Output face disp mass=0
WQ Output cell mass=0
WQ Output cell source sink temp=0
WQ Output nsm pathways=0
WQ Output nsm derived pathways=0
WQ Create Restart=0
WQ Fixed Restart=0
WQ System Summary=0
WQ Write To DSS=0
Sorting and Armoring Iterations= 10
XS Update Threshold= 0.02
Bed Roughness Predictor= 0
Hydraulics Update Threshold= 0.02
Energy Slope Method= 1
Volume Change Method= 1
Sediment Retention Method= 0
Sediment TS Multiplier= 1
Warm Up Method= 0
XS Weighting Method= 0
Number of US Weighted Cross Sections= 1
Number of DS Weighted Cross Sections= 1
Upstream XS Weight=0
Main XS Weight=1
Downstream XS Weight=0
Number of DS XS's Weighted with US Boundary= 1
Upstream Boundary Weight= 1
Weight of XSs Associated with US Boundary= 0
Number of US XS's Weighted with DS Boundary= 1
Downstream Boundary Weight= 0.5
Weight of XSs Associated with DS Boundary= 0.5
Percentile Method= 0
Sediment Output Level= 3
Mass or Volume Output= 0
Output Increment Type= 1
Profile and TS Output Increment= 1
Transport Output Increment 1
XS Output Flag= 0
XS Output Increment= 10
Read HDF5 Sediment Hotstart= 0
Sediment Hotstart Type= 0
Write Gradation File= 0
Read Gradation Hotstart= 0
Write HDF5 File= 1
Write Binary Output= 1
Write DSS Sediment File= 0
DSS Sediment Output Type= 1
SV Curve= 0
Specific Gage Flag= 0
Subcell Erosion Methods= 0
Subcell Deposition Methods= 0
Advection Scheme= 1
Matrix Solver= 0
Implicit Weighting Factor= 1
Maximum Outer Loop Convergence Iterations= 5
Convergence Maximum Absolute= 0.001
Convergence RMSE= 0.0001
Grain Fractions Max Abs Error= 0.001
Max Subgrid Regions= 1
Max Subgrid Length Scale= 3.402823E+38
Initial Layer Thickness= 3.402823E+38
Min Layer Thickness= 3.402823E+38
Max Layer Thickness= 3.402823E+38
Number of Layers= 5

--- LAURELRN1.f01 (steady flow) ---

Flow Title=Flow
Program Version=6.00
Number of Profiles= 6
Profile Names=01pct,10pct,04pct,02pct,0_2pct,01plus
River Rch & RM=LAURELRN1,Main,37690
     900     484     638     765    1250    1330
River Rch & RM=LAURELRN1,Main,31515
    1300     708     927    1110    1780    1920
River Rch & RM=LAURELRN1,Main,27911
    1850    1020    1330    1580    2520    2730
River Rch & RM=LAURELRN1,Main,23991
    2060    1140    1490    1760    2810    3050
River Rch & RM=LAURELRN1,Main,15665
    2300    1280    1660    1970    3120    3390
Boundary for River Rch & Prof#=LAURELRN1,Main            , 1
Up Type= 0
Dn Type= 3
Dn Slope=0.00817
Boundary for River Rch & Prof#=LAURELRN1,Main            , 2
Up Type= 0
Dn Type= 3
Dn Slope=0.00817
Boundary for River Rch & Prof#=LAURELRN1,Main            , 3
Up Type= 0
Dn Type= 3
Dn Slope=0.00817
Boundary for River Rch & Prof#=LAURELRN1,Main            , 4
Up Type= 0
Dn Type= 3
Dn Slope=0.00817
Boundary for River Rch & Prof#=LAURELRN1,Main            , 5
Up Type= 0
Dn Type= 3
Dn Slope=0.00817
Boundary for River Rch & Prof#=LAURELRN1,Main            , 6
Up Type= 0
Dn Type= 3
Dn Slope=0.00817
DSS Import GetInterval= 0
DSS Import GetPeak= 0
DSS Import FillOption= 0

--- LAURELRN1.g01 (geometry) ---

Geom Title=Geometry
Program Version=6.10

River Reach=LAURELRN1       ,Main
Reach XY= 30
     2220735.631      396149.914     2220024.584      395406.427
2218799.34916211394810.186127802     2218145.261      394886.814
     2216923.143      394107.206     2215175.071      394330.014
     2215002.428      393919.7312215469.85212092393035.661863603
2215249.39046894392380.8233199912213067.32544655391615.361219002
2211418.21200734392678.9678153442211188.15846525393366.519343375
     2210391.052      393849.377  2210141.043638394390.228730106
     2208785.766      395190.042     2208019.498      396248.004
2207467.52933052  396409.50524772207265.94779515397308.265632525
     2206401.058      397006.815     2205065.353      397301.384
2204541.57062881396650.804194055     2202824.137      396976.121
2201247.65611422396035.972515815     2198773.146      396478.786
     2198419.656397524.498138386     2197344.971      398253.259
2196377.22535846398062.1885974412195945.84896693 398375.12078402
     2194406.472      398519.124     2193866.663        397630.2

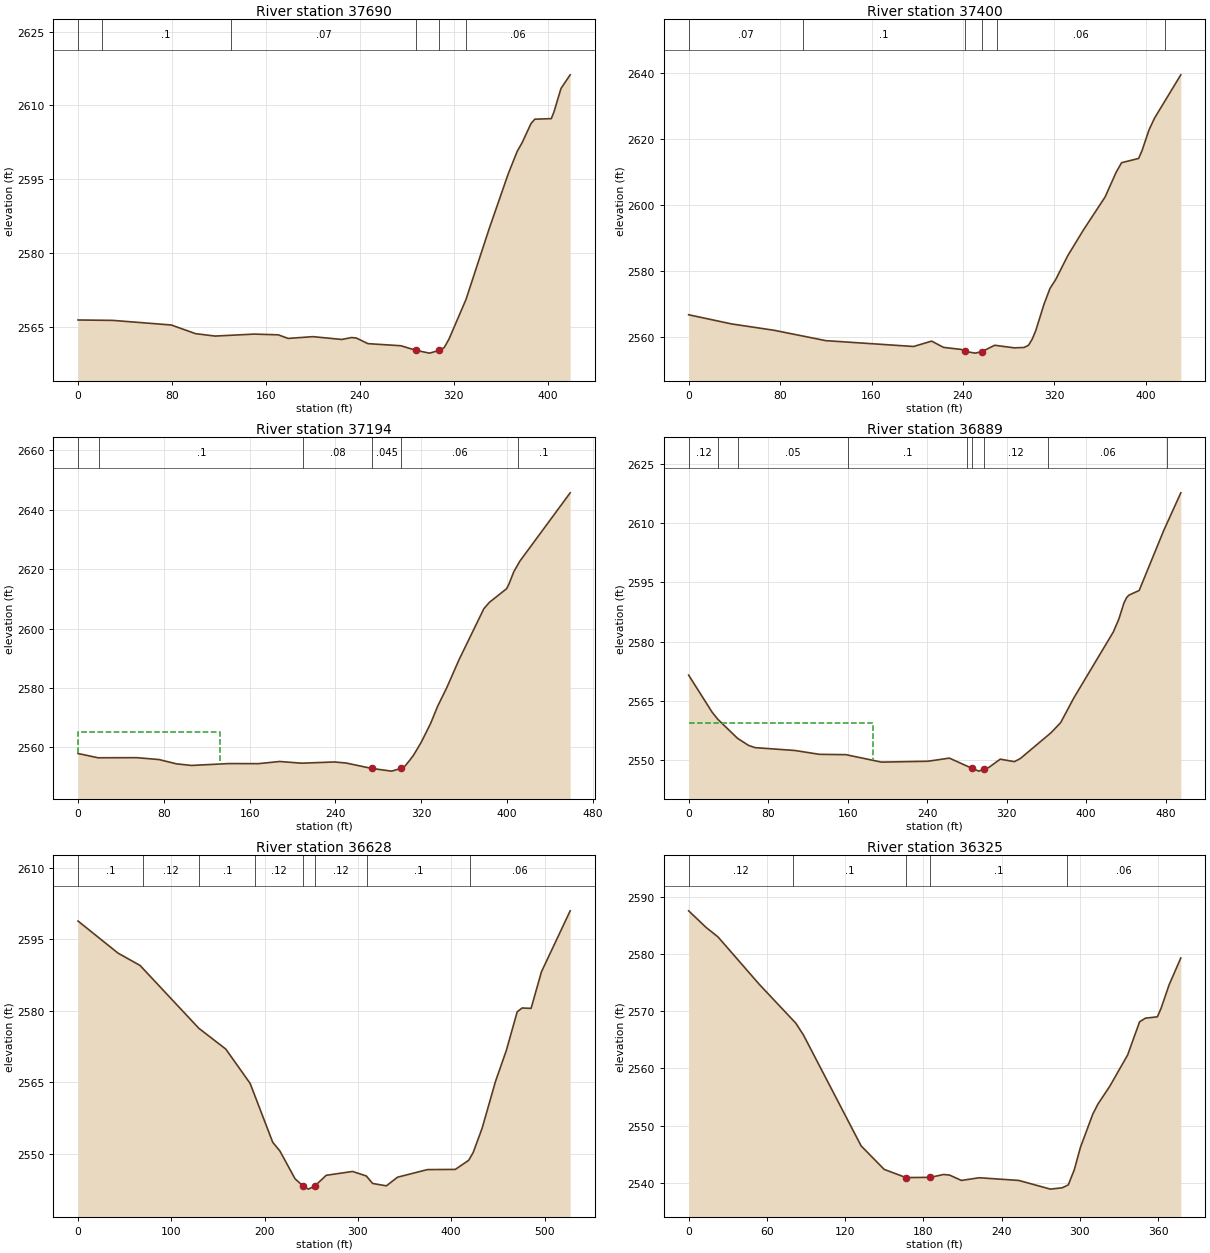
Type RM Length L Ch R = 1 ,37690   ,289.2,289.2,289.2
XS GIS Cut Line= 2
2220813.33761465395860.5853158842220702.69661531396264.732299579
#Sta/Elev= 30
       0 2566.34    29.6 2566.26    79.4 2565.32   100.1 2563.56   116.7 2563.07
   149.9 2563.47   170.5 2563.32   178.9 2562.59     200 2562.95   224.6 2562.38
   232.9 2562.77     237 2562.67   246.8 2561.53   274.9  2561.1   287.9 2560.16
   299.2  2559.6   307.4 2560.14   311.7 2560.71   315.8 2562.44   330.3 2570.51
   349.8 2584.73   366.1 2595.96   373.9 2600.64     378 2602.35   385.6 2606.27
   388.9 2607.18   402.9 2607.29   405.2 2608.65   411.2 2613.44     419  2616.2
#Mann= 6 ,-1,0
       0     .07       0      20      .1       0     130     .07       0
   287.9    .045       0   307.4     .07       0     330     .06       0
Bank Sta=287.9,307.4
XS Rating Curve= 0 ,0
Exp/Cntr(USF)=0,0
Exp/Cntr=0.3,0.1

Type RM Length L Ch R = 1 ,37400   ,206.2,206.3,206.6
XS GIS Cut Line= 3
2220724.58896917395820.6694946572220464.18658451396034.199450077
2220412.10610758396112.320165474
#Sta/Elev= 30
       0 2566.64    37.6 2563.86    74.6 2561.95     120  2558.8   196.8 2557.03
   212.6 2558.66     223 2556.76   238.5 2556.14   242.2 2555.52   250.8 2555.02
   256.5 2555.48   267.8  2557.4   284.9 2556.62   293.4 2556.73   297.3 2557.38
   300.6 2559.26   303.6 2561.74   310.9 2569.82   316.1 2574.58   321.3  2577.4
   331.6 2584.48   345.1 2592.16   364.4 2602.34     374 2609.78   378.8  2612.7
   393.7 2613.98   396.6 2616.29   402.8 2622.64   407.6 2626.19   430.6 2639.31
#Mann= 6 ,-1,0
       0     .07       0     100      .1       0   242.2    .045       0
   256.5     .08       0     270     .06       0  416.76      .1       0
Bank Sta=242.2,256.5
XS Rating Curve= 0 ,0
Exp/Cntr(USF)=0,0
Exp/Cntr=0.3,0.1

Type RM Length L Ch R = 1 ,37194   ,299.7,304.6,308.2
XS GIS Cut Line= 2
2220556.46622621395672.1701545422220254.59993796396017.818771916
#Sta/Elev= 30
       0 2557.97    18.7 2556.53    54.8 2556.57    75.7 2555.92    91.6  2554.5
   105.8 2553.95   140.3 2554.58   168.2 2554.55     188 2555.28   208.5 2554.71
   239.1 2555.12   249.8 2554.78   274.1 2552.93   292.3 2552.04   301.4 2552.98
   304.3 2553.47   309.4 2555.75   312.8 2557.38     320 2561.73   328.8 2568.11
   335.4 2573.92   343.9 2580.16   355.3 2589.54   378.4 2606.66   383.6 2608.82
   399.6  2613.4   401.8 2614.94   406.3 2619.08     412 2622.67   458.9 2645.65
#Mann= 6 ,-1,0
       0     .05       0      20      .1       0     210     .08       0
   274.1    .045       0   301.4     .06       0     410      .1       0
#XS Ineff= 2 , 0
           132.1 2565.19
Permanent Ineff=
       F       F
Bank Sta=274.1,301.4
XS Rating Curve= 0 ,0
Exp/Cntr(USF)=0,0
Exp/Cntr=0.3,0.1

Type RM Length L Ch R = 1 ,36889   ,264.8,261.5,258.8
XS GIS Cut Line= 3
2220443.11082739395459.0000662422220169.96403829395680.266529893
2220083.16324341395794.843579142
#Sta/Elev= 30
       0 2571.54    23.5 2562.21    29.2 2560.41    49.1 2555.57    60.4 2553.74
      67 2553.19   106.7 2552.48   131.6  2551.5   158.2 2551.42   194.1 2549.53
   240.6 2549.75   262.4 2550.54   285.2 2547.95   292.1 2547.25   297.2 2547.75
   302.3 2548.22   313.6 2550.28   327.8 2549.64   333.9 2550.46   364.9 2557.01
   374.4 2559.53   387.7  2565.8   427.4 2582.47     433 2585.77     438 2589.74
   440.6 2591.11     443 2591.78   453.4 2592.97   478.1 2608.14   495.3 2617.68
#Mann= 9 ,-1,0
       0     .12       0      30      .1       0      50     .05       0
     160      .1       0     280     .12       0   285.2    .045       0
   297.2     .12       0  361.52     .06       0  481.52      .1       0
#XS Ineff= 2 , 0
          185.87 2559.45
Permanent Ineff=
       F       F
Bank Sta=285.2,297.2
XS Rating Curve= 0 ,0
Exp/Cntr(USF)=0,0
Exp/Cntr=0.3,0.1

Type RM Length L Ch R = 1 ,36628   ,304.4,303.2,306.8
XS GIS Cut Line= 2
2220196.44166313395234.2269577972219908.68061729395676.366447104
#Sta/Elev= 30
       0 2598.87    42.8 2592.14    66.5 2589.54   129.5 2576.35   158.4 2571.98
   184.5 2564.77   208.7 2552.41   216.3 2550.61   232.6 2544.76   241.5 2543.17
   246.9 2542.58  253.81 2543.23     266 2545.48   294.3 2546.29     309 2545.34
   315.8 2543.77   330.5 2543.27   342.4 2545.08   374.5 2546.68   404.4 2546.72
   418.7 2548.63   423.5 2550.24   433.1 2555.36   447.5 2565.22   459.1 2571.71
   470.7  2579.8     476 2580.61   485.6 2580.53   496.7  2588.2   527.5 2601.01
#Mann= 8 ,-1,0
       0      .1       0      70     .12       0     130      .1       0
     190     .12       0   241.5    .045       0  253.81     .12       0
     310      .1       0     420     .06       0
Bank Sta=241.5,253.81
XS Rating Curve= 0 ,0
Exp/Cntr(USF)=0,0
Exp/Cntr=0.3,0.1

Type RM Length L Ch R = 1 ,36325   ,199.4,200.9,201.5
XS GIS Cut Line= 2
2219867.89727209395225.4303646912219687.35161873395557.009401155
#Sta/Elev= 30
       0 2587.56    13.4 2584.65    22.5    2583    54.4 2574.65    82.2 2567.91
    88.1 2565.83   132.3 2546.45     150 2542.34   166.7 2540.91   185.4 2540.95
   195.6 2541.45   200.2 2541.34   209.2 2540.41   222.9 2540.88   253.2 2540.41
   277.5 2538.89   286.6 2539.13   291.2 2539.63   295.8 2542.28   300.5 2546.19
     310 2552.01     314 2553.79   323.1 2556.91   336.7 2562.34   345.9 2568.16
   350.4 2568.79   359.5 2569.02   362.3 2570.47   368.6 2574.66   377.5 2579.31
#Mann= 5 ,-1,0
       0     .12       0      80      .1       0   166.7    .045       0
   185.4      .1       0     290     .06       0
Bank Sta=166.7,185.4
XS Rating Curve= 0 ,0
Exp/Cntr(USF)=0,0
Exp/Cntr=0.3,0.1

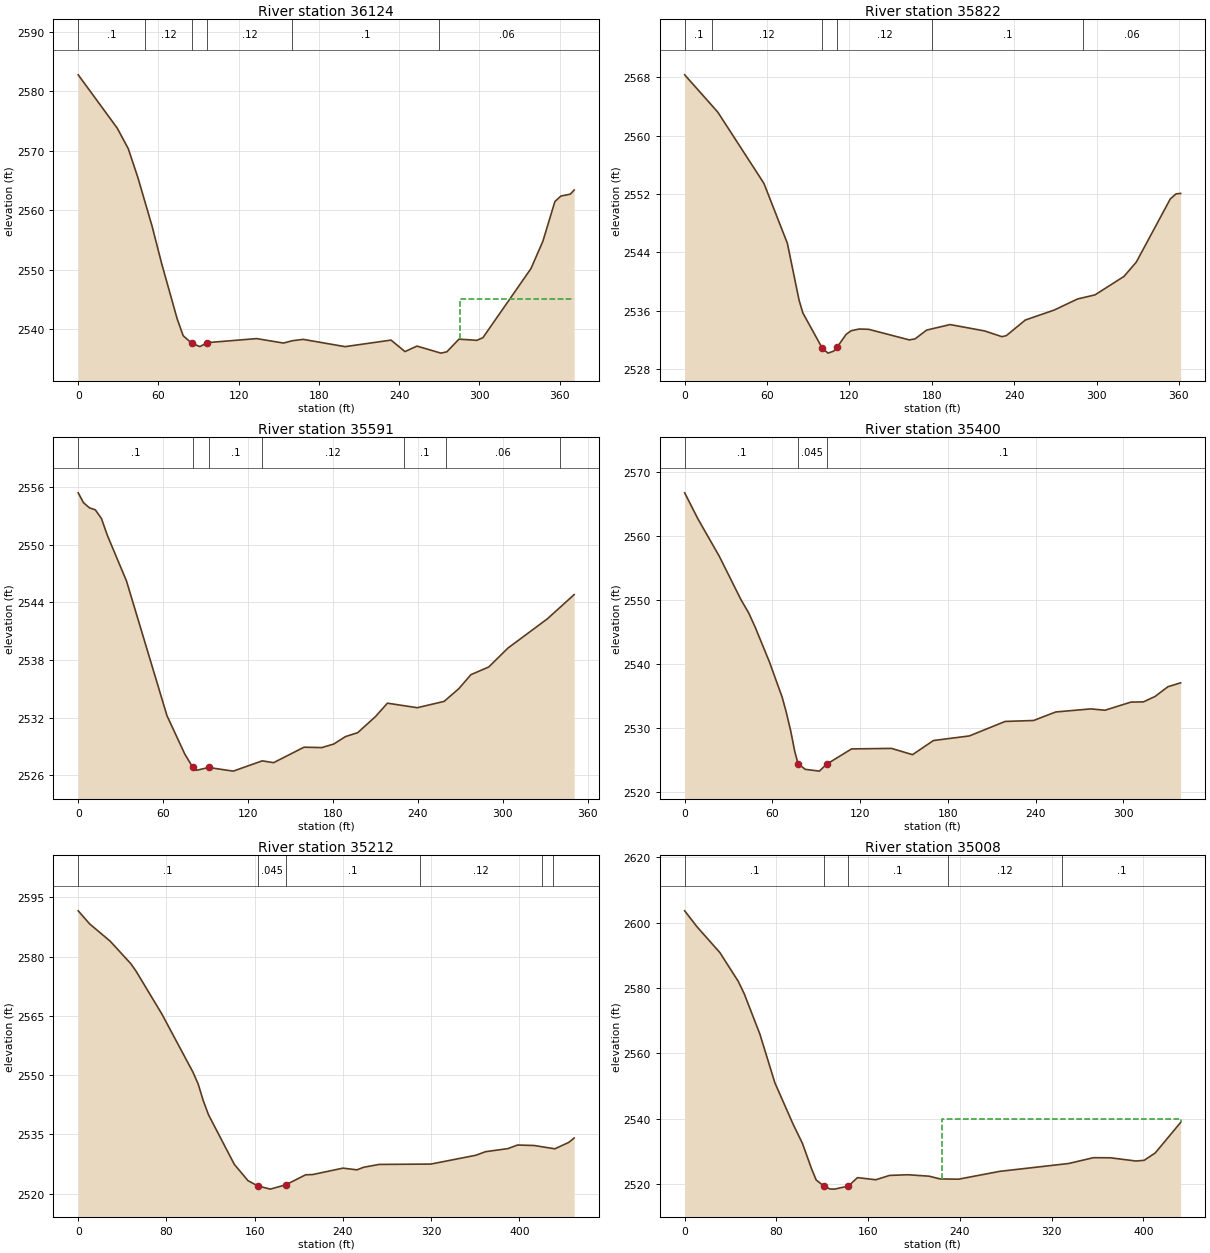
Type RM Length L Ch R = 1 ,36124   ,302.1,301.9,298.6
XS GIS Cut Line= 2
2219720.32862779395147.0954419242219553.12333864395478.033988412
#Sta/Elev= 30
       0 2582.77    29.2 2573.81    37.4 2570.38    44.7 2565.45    55.3 2557.29
    62.4 2551.06      74 2541.77    78.5 2538.94      85 2537.66      91 2537.12
    96.4 2537.78   133.4 2538.46   153.5 2537.71     160  2538.1   168.2 2538.33
   199.5 2537.11   233.9 2538.21   244.3 2536.28   253.3  2537.2   271.2 2536.02
   275.6 2536.24   284.7 2538.37   298.1 2538.17   302.6 2538.62   338.5 2550.22
   347.4  2554.8   356.4 2561.48   360.9 2562.41   367.9 2562.72   370.8 2563.42
#Mann= 6 ,-1,0
       0      .1       0      50     .12       0      85    .045       0
    96.4     .12       0     160      .1       0     270     .06       0
#XS Ineff= 2 , 0
                          285.71         2545.14
Permanent Ineff=
       F       F
Bank Sta=85,96.4
XS Rating Curve= 0 ,0
Exp/Cntr(USF)=0,0
Exp/Cntr=0.3,0.1

Type RM Length L Ch R = 1 ,35822   ,230.1,231,229.9
XS GIS Cut Line= 2
2219442.57337715395022.316504658  2219326.260312395364.311636508
#Sta/Elev= 30
       0 2568.31    24.1 2563.21    57.7 2553.46    74.8 2545.25    83.3 2537.48
    86.1 2535.71   100.2  2530.9   104.4 2530.22   108.6  2530.5   111.3  2531.1
   117.6 2532.79   121.3 2533.29   127.1 2533.52     134 2533.48   163.6 2532.03
   167.8 2532.17   176.2 2533.37   193.3 2534.13   218.4 2533.26   231.1 2532.47
   234.3 2532.62   248.1 2534.75   269.2 2536.12   286.1 2537.63   298.8 2538.19
   319.9 2540.71   328.9 2542.67   353.7 2551.33   357.9 2552.02   361.2 2552.08
#Mann= 6 ,-1,0
       0      .1       0      20     .12       0   100.2    .045       0
   111.3     .12       0     180      .1       0     290     .06       0
Bank Sta=100.2,111.3
XS Rating Curve= 0 ,0
Exp/Cntr(USF)=0,0
Exp/Cntr=0.3,0.1

Type RM Length L Ch R = 1 ,35591   ,187.1,191.1,193.5
XS GIS Cut Line= 2
 2219222.8021435394973.6386746392219113.61239095395306.434405687
#Sta/Elev= 30
       0 2555.39     3.7 2554.37     7.9 2553.83    12.1 2553.62    16.4 2552.72
    20.6 2550.96    34.1 2546.22    62.7  2532.2    75.3  2528.2      81 2526.81
    83.7 2526.52    92.1 2526.81   109.5 2526.43     130  2527.5     138 2527.31
   159.5 2528.92   172.1 2528.88   180.5 2529.25   188.7 2530.02   197.4 2530.43
     210 2532.11   218.4  2533.5   239.5 2533.03   258.5 2533.69   268.9 2535.02
   277.4 2536.47     290 2537.27   303.5 2539.23   331.4 2542.28   350.3  2544.8
#Mann= 7 ,-1,0
       0      .1       0      81    .045       0    92.1      .1       0
     130     .12       0     230      .1       0     260     .06       0
     340     .07       0
Bank Sta=81,92.1
XS Rating Curve= 0 ,0
Exp/Cntr(USF)=0,0
Exp/Cntr=0.3,0.1

Type RM Length L Ch R = 1 ,35400   ,188,188.4,187.1
XS GIS Cut Line= 2
2219093.63418171394881.6992169432218899.20040116395159.461760578
#Sta/Elev= 30
       0 2566.78     9.1 2562.69    23.7 2556.86    38.4 2550.13    43.8 2548.01
    48.2  2545.8      58 2540.34    66.7 2534.83    69.6 2532.38    72.5 2529.59
    75.3 2526.35    77.5  2524.5    82.4 2523.59    92.1 2523.31      97 2524.38
   114.1 2526.78   141.4 2526.86   155.8 2525.88   170.1 2528.09   194.7 2528.81
   219.1 2531.07   238.6 2531.22   253.7 2532.55   277.7 2533.03   287.4 2532.82
   305.1 2534.09   313.7 2534.13   321.6 2534.97   330.4 2536.49   339.1  2537.1
#Mann= 3 ,-1,0
       0      .1       0    77.5    .045       0      97      .1       0
Bank Sta=77.5,97
XS Rating Curve= 0 ,0
Exp/Cntr(USF)=0,0
Exp/Cntr=0.3,0.1

Type RM Length L Ch R = 1 ,35212   ,209,203.4,191
XS GIS Cut Line= 2
2218966.90502117394732.4018497392218732.54287498395116.061363135
#Sta/Elev= 30
       0 2591.58    10.3 2588.29      29  2583.9    47.8 2578.17    52.5 2576.29
    75.9 2565.44     104 2550.77   108.7 2547.81   113.4 2543.52   118.1 2539.99
   141.5 2527.44   153.9 2523.31   162.8 2521.97   174.2 2521.16   188.4 2522.28
   206.2 2524.79   212.4 2524.84     240 2526.47   252.8 2526.04   258.7 2526.69
   272.8 2527.41   319.7  2527.5   360.5 2529.73   369.2 2530.63   389.6 2531.42
   398.3 2532.32   413.4  2532.2   432.1 2531.36   444.8    2533   449.6 2534.09
#Mann= 6 ,-1,0
       0      .1       0   162.8    .045       0   188.4      .1       0
     310     .12       0     420      .1       0     430     .06       0
Bank Sta=162.8,188.4
XS Rating Curve= 0 ,0
Exp/Cntr(USF)=0,0
Exp/Cntr=0.3,0.1

Type RM Length L Ch R = 1 ,35008   ,257,259,254.3
XS GIS Cut Line= 4
2218703.03060472394666.4332456262218703.03060472394855.658978477
2218699.55857293395004.9563456812218659.63020728395090.021124669
#Sta/Elev= 30
       0 2603.61    10.7 2598.75    30.7 2590.83    46.7 2582.05    51.9 2578.26
    65.6 2565.87    78.7 2550.94    94.7  2538.2   102.7 2532.44   110.7 2524.62
   114.7 2521.23   121.6 2519.33   126.7 2518.49   130.7 2518.44   142.7 2519.37
   150.7 2521.96   166.7 2521.31   178.7 2522.64   194.7 2522.84   213.1  2522.4
   222.8 2521.56   238.8 2521.48   274.8 2523.88   334.8 2526.28   356.5 2528.06
   371.3 2528.03   393.6 2527.04   400.7 2527.26   410.4 2529.52   432.5 2538.85
#Mann= 5 ,-1,0
       0      .1       0   121.6    .045       0   142.7      .1       0
  229.23     .12       0  329.23      .1       0
#XS Ineff= 2 , 0
                          224.27         2539.78
Permanent Ineff=
       F       F
Bank Sta=121.6,142.7
XS Rating Curve= 0 ,0
Exp/Cntr(USF)=0,0
Exp/Cntr=0.3,0.1

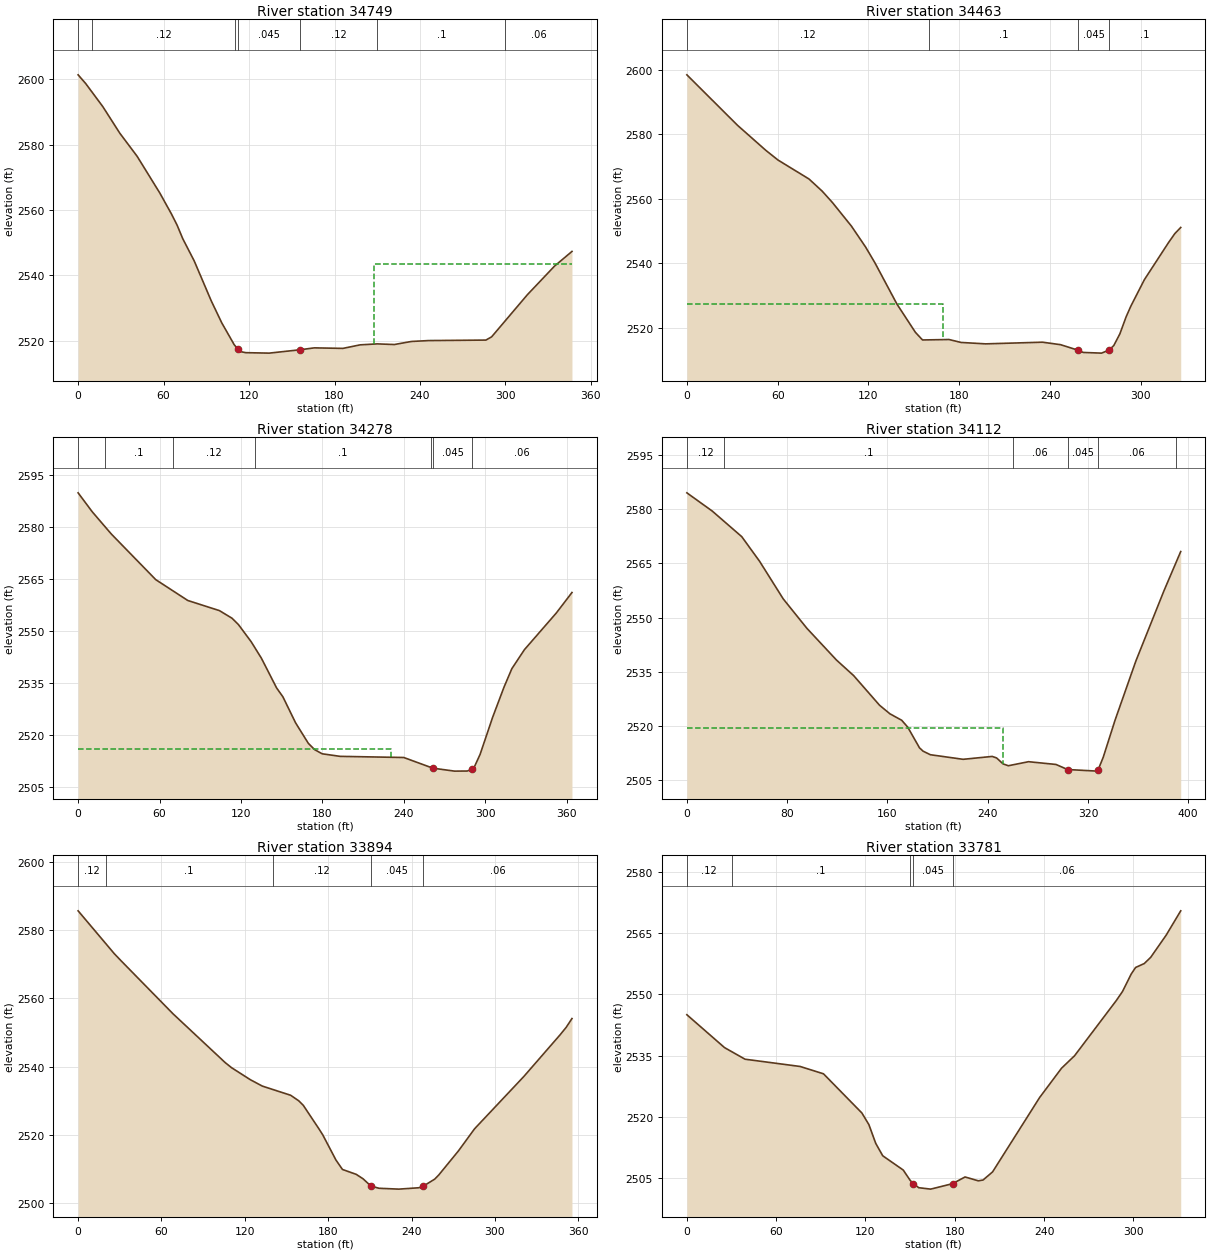
Type RM Length L Ch R = 1 ,34749   ,277.3,286.3,277.5
XS GIS Cut Line= 2
2218444.36423596394695.9455158872218473.87650622395041.412679533
#Sta/Elev= 30
       0 2601.35     5.3  2598.7    17.3 2591.65    29.3 2583.48    41.4 2576.45
    57.4 2565.17    65.5 2558.81    69.5 2555.36    73.5 2551.19    81.5 2544.43
    93.4 2532.27   100.8 2525.51   109.6 2518.78   111.9 2517.59   113.6 2516.71
   117.7 2516.35   134.1 2516.21   155.72517.231   165.8 2517.82   185.9 2517.66
     198 2518.74     210 2519.04     222 2518.84     234 2519.78   246.1 2520.05
   286.3  2520.2   290.3 2521.19   315.3 2534.03   334.4 2542.81   346.7 2547.32
#Mann= 7 ,-1,0
       0      .1       0      10     .12       0     110      .1       0
   111.9    .045       0   155.7     .12       0     210      .1       0
     300     .06       0
#XS Ineff= 2 , 0
                          207.53         2543.54
Permanent Ineff=
       F       F
Bank Sta=111.9,155.7
XS Rating Curve= 0 ,0
Exp/Cntr(USF)=0,0
Exp/Cntr=0.3,0.1

Type RM Length L Ch R = 1 ,34463   ,176.5,185.4,189.7
XS GIS Cut Line= 3
2218310.69101184394664.6972297282218223.89021695394805.314517443
2218203.05802618394965.027980033
#Sta/Elev= 30
       0  2598.4    33.5 2582.74    52.3 2574.94    60.3 2571.96    80.7 2566.11
    89.4 2562.35    96.2  2558.8   108.7 2551.52   118.1 2545.02   124.3 2540.09
   138.8 2527.34     151 2518.58   155.7 2516.21   173.2 2516.35   181.2 2515.44
   197.4    2515     235 2515.52   246.9 2514.75   258.2 2513.08   261.9 2512.34
     274 2512.13   279.1 2513.12   282.1  2514.5   286.1 2518.11   290.2 2523.35
   293.3 2526.65   302.3 2534.91   318.3 2546.44   322.4 2549.18   326.3 2551.08
#Mann= 4 ,-1,0
       0     .12       0     160      .1       0   258.2    .045       0
   279.1      .1       0
#XS Ineff= 2 , 0
          169.35 2527.44
Permanent Ineff=
       F       F
Bank Sta=258.2,279.1
XS Rating Curve= 0 ,0
Exp/Cntr(USF)=0,0
Exp/Cntr=0.3,0.1

Type RM Length L Ch R = 1 ,34278   ,165.9,165.8,165.8
XS GIS Cut Line= 2
2218194.37794669394588.3125302292218005.15221384 394899.05937592
#Sta/Elev= 30
       0 2589.92    10.4 2584.46    24.4 2578.07    57.2 2564.88    80.8 2558.87
   104.1 2555.95   113.4 2553.75   118.1 2551.93   127.5 2546.97     135 2542.24
   146.2 2533.67   150.9 2531.06   160.2 2523.59   169.6 2517.67   174.3 2515.84
   179.8 2514.66     193 2513.92   239.9 2513.59   261.3 2510.52   277.3 2509.66
   286.7 2509.69   290.42510.265   291.4 2510.45   296.1 2514.47   305.4 2525.23
   313.7 2533.84   319.5  2539.2   328.8  2544.7   352.3 2555.28   363.8 2561.17
#Mann= 7 ,-1,0
       0     .12       0      20      .1       0      70     .12       0
     130      .1       0     260     .06       0   261.3    .045       0
   290.4     .06       0
#XS Ineff= 2 , 0
          230.31 2516.05
Permanent Ineff=
       F       F
Bank Sta=261.3,290.4
XS Rating Curve= 0 ,0
Exp/Cntr(USF)=0,0
Exp/Cntr=0.3,0.1

Type RM Length L Ch R = 1 ,34112   ,218.9,217.8,217
XS GIS Cut Line= 2
2218071.12081795394484.1515763662217861.06289433394817.466628727
#Sta/Elev= 30
       0 2584.52    20.3 2579.46    43.8 2572.38      58 2565.58    76.9 2555.15
    95.8    2547   119.4 2538.22   133.1 2533.91   153.7 2525.73     162 2523.35
   171.4 2521.56   176.2 2519.66   185.6 2513.93   188.5    2513   194.3 2512.02
   220.4 2510.75   243.6 2511.55   247.1 2511.13   252.3 2509.48   256.5 2508.97
   272.6 2510.09   294.4 2509.33   303.8 2507.92   327.5 2507.48   328.1 2507.83
   332.2 2511.34   341.6 2521.57   358.1 2537.85   380.6 2557.38     394 2568.27
#Mann= 6 ,-1,0
       0     .12       0      30      .1       0     260     .06       0
   303.8    .045       0   328.1     .06       0     390      .1       0
#XS Ineff= 2 , 0
          252.53 2519.52
Permanent Ineff=
       F       F
Bank Sta=303.8,328.1
XS Rating Curve= 0 ,0
Exp/Cntr(USF)=0,0
Exp/Cntr=0.3,0.1

Type RM Length L Ch R = 1 ,33894   ,114.7,112.8,110.5
XS GIS Cut Line= 4
2217892.31118049394386.9346860942217793.35827432394548.384164581
 2217727.3896702 394640.393007162217706.55747943394689.001452296
#Sta/Elev= 30
       0 2585.65    26.1 2573.07    30.8 2571.07    68.3 2555.49   105.8 2541.21
   110.5 2539.68   123.9 2536.19   132.6  2534.3     153 2531.61   158.8    2530
   162.1 2528.66   173.3 2521.81   176.1 2520.02   185.6 2512.64   190.3 2509.87
   200.2 2508.44   205.1 2507.14   210.8    2505   216.6 2504.36   230.9 2504.11
   245.2 2504.51   248.1 2504.89   256.7 2507.04   259.6 2508.25   273.8 2515.32
   285.4 2521.79   320.9 2537.13   346.9  2549.3   351.3 2551.49   355.5 2554.09
#Mann= 5 ,-1,0
       0     .12       0      20      .1       0     140     .12       0
   210.8    .045       0   248.1     .06       0
Bank Sta=210.8,248.1
XS Rating Curve= 0 ,0
Exp/Cntr(USF)=0,0
Exp/Cntr=0.3,0.1

Type RM Length L Ch R = 1 ,33781   ,297.3,305.5,314
XS GIS Cut Line= 2
2217758.06480316394379.2873425412217592.24275324394666.628435767
#Sta/Elev= 30
       0 2545.02    25.3 2536.96    39.1 2534.11    76.1 2532.33    91.8 2530.53
   117.6 2520.92   122.3 2518.07   126.9 2513.47   131.6 2510.43   145.4 2506.92
     150 2504.42   152.1 2503.62   155.8  2502.6   163.8 2502.25   178.5 2503.59
   186.9 2505.23   195.8 2504.29     199 2504.48   205.4 2506.48     237 2524.71
   251.7 2531.89   260.5 2534.97   288.5 2548.49   292.7 2550.72   298.5 2554.98
   301.5 2556.61   307.3 2557.57   311.6 2559.08     322 2564.52   331.8  2570.5
#Mann= 5 ,-1,0
       0     .12       0      30      .1       0     150     .06       0
   152.1    .045       0   178.5     .06       0
Bank Sta=152.1,178.5
XS Rating Curve= 0 ,0
Exp/Cntr(USF)=0,0
Exp/Cntr=0.3,0.1

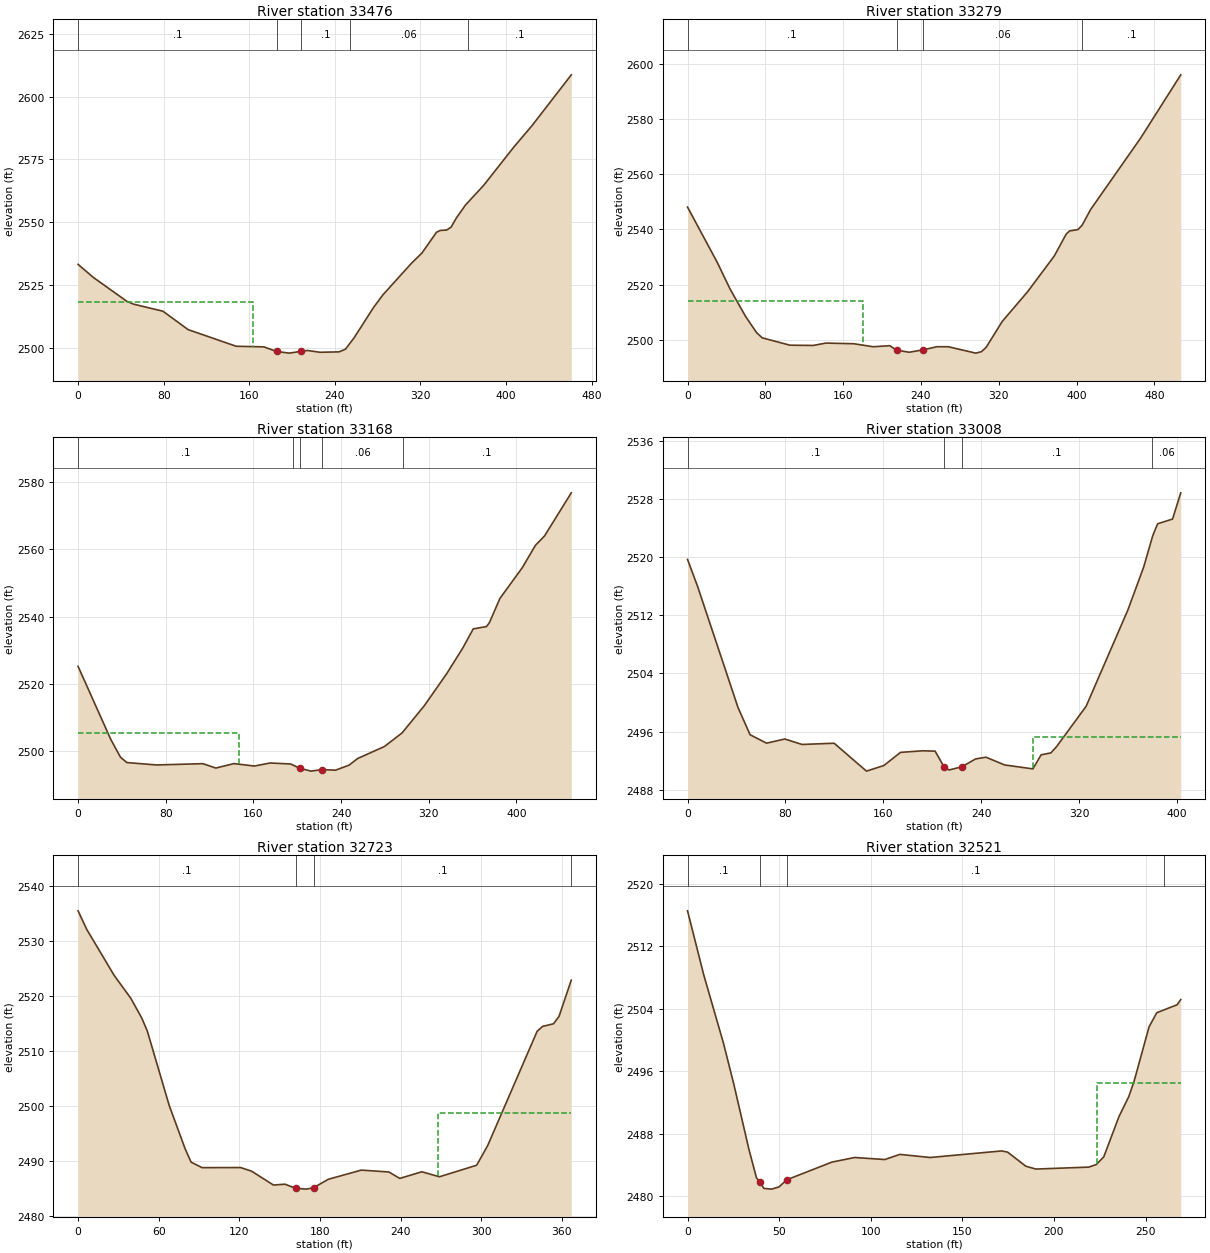
Type RM Length L Ch R = 1 ,33476   ,199.5,196.5,188.2
XS GIS Cut Line= 3
2217591.55172248394265.086535721 2217401.0474895 394383.56432447
2217289.63746153394592.329343933
#Sta/Elev= 30
       0  2533.2    14.1 2528.06    45.6 2518.49    51.9 2517.37    79.3 2514.56
   102.9 2507.23   147.7 2500.62   173.6 2500.37   185.5 2498.56   197.1 2497.88
   208.7 2498.58   214.5 2498.93   226.1 2498.22   243.9 2498.38   249.8 2499.41
   257.9 2503.92   276.4 2516.19   285.1 2521.16   311.9 2533.78   321.4 2537.71
     335 2545.98   338.5  2546.7   344.4 2546.86   348.6 2547.99   353.6 2551.68
   362.1 2556.82   379.1 2564.65   407.5    2580   424.3 2588.41     461 2608.63
#Mann= 5 ,-1,0
       0      .1       0   185.5    .045       0   208.7      .1       0
  254.34     .06       0  364.34      .1       0
#XS Ineff= 2 , 0
          163.59 2518.16
Permanent Ineff=
       F       F
Bank Sta=185.5,208.7
XS Rating Curve= 0 ,0
Exp/Cntr(USF)=0,0
Exp/Cntr=0.3,0.1

Type RM Length L Ch R = 1 ,33279   ,119.7,111,102.5
XS GIS Cut Line= 3
2217402.75469733394076.1878404022217204.84888499394334.854209162
2217137.14426498394503.247751241
#Sta/Elev= 30
       0 2548.07    30.6 2528.03    43.7 2518.45    59.6 2508.55      71 2502.63
    76.8 2500.75   105.3 2498.08   129.3 2497.99   142.3 2498.85   170.9 2498.61
   190.9 2497.52     208  2497.9   214.9  2496.3   227.9 2495.53   242.2 2496.39
   256.5 2497.53   268.2 2497.52   296.4 2495.21   302.2 2495.73   307.1 2497.31
   323.6 2506.67   349.8 2517.48   377.2  2530.4   389.5 2538.37   392.9 2539.43
   401.5 2539.95   405.8  2541.5   414.4 2547.14   466.2 2573.19   507.2 2595.95
#Mann= 4 ,-1,0
       0      .1       0   214.9    .045       0   242.2     .06       0
  405.69      .1       0
#XS Ineff= 2 , 0
          180.51 2513.93
Permanent Ineff=
       F       F
Bank Sta=214.9,242.2
XS Rating Curve= 0 ,0
Exp/Cntr(USF)=0,0
Exp/Cntr=0.3,0.1

Type RM Length L Ch R = 1 ,33168   ,155.1,159.7,165.5
XS GIS Cut Line= 3
2217264.63682874394044.399258938 2217160.9994717394211.172017392
 2217118.1150481394461.331155073
#Sta/Elev= 30
       0 2525.22    29.9 2503.56    38.7 2498.31    44.5 2496.72    71.6 2496.01
   113.9 2496.39   125.8 2495.09   142.2 2496.41     161 2495.69   175.2 2496.59
     194  2496.3   202.3 2495.05   212.5 2494.18   223.1 2494.65   234.9 2494.45
   247.3 2495.94   255.2 2497.92   279.6 2501.47   295.8 2505.52   316.1  2513.6
   336.4 2523.02   351.2 2530.69   360.7 2536.33   372.9 2537.03   375.5 2538.22
   385.1 2545.38   405.4 2554.44   417.5 2561.11   425.7 2563.84   450.2 2576.65
#Mann= 5 ,-1,0
       0      .1       0  196.35     .06       0   202.3    .045       0
   223.1     .06       0  296.35      .1       0
#XS Ineff= 2 , 0
           146.7  2505.6
Permanent Ineff=
       F       F
Bank Sta=202.3,223.1
XS Rating Curve= 0 ,0
Exp/Cntr(USF)=0,0
Exp/Cntr=0.3,0.1

Type RM Length L Ch R = 1 ,33008   ,293.9,285.4,275.4
XS GIS Cut Line= 4
2217151.67761607393998.2186555312217109.36801062 394017.16329988
2216953.12657982394265.4135732532216942.15606494394327.767638539
#Sta/Elev= 30
       0 2519.69     8.2 2515.99    41.2 2499.33    51.1 2495.56    64.6  2494.4
    79.5 2494.97    93.6 2494.22   119.8 2494.39   146.2 2490.55   160.4 2491.32
     174 2493.13   192.3 2493.35   202.3  2493.3   209.7  2491.1   213.8 2490.71
   224.2 2491.15   235.4 2492.23   243.8 2492.47   259.1  2491.4   282.2 2490.86
   288.9 2492.79   296.9 2493.06   301.6 2493.94   325.7 2499.48   359.8 2512.73
   372.7 2518.64   380.1 2522.95   384.1  2524.6   396.3 2525.25     403 2528.86
#Mann= 4 ,-1,0
       0      .1       0   209.7    .045       0   224.2      .1       0
  379.68     .06       0
#XS Ineff= 2 , 0
                          282.54         2495.28
Permanent Ineff=
       F       F
Bank Sta=209.7,224.2
XS Rating Curve= 0 ,0
Exp/Cntr(USF)=0,0
Exp/Cntr=0.3,0.1

Type RM Length L Ch R = 1 ,32723   ,199.8,201.9,198.4
XS GIS Cut Line= 2
2216716.33747039393946.8106475232216791.36200896 394306.09479504
#Sta/Elev= 30
       0 2535.52     6.5 2532.12    26.9 2523.75    39.2 2519.62    47.4    2516
    51.5 2513.66    67.8 2500.11    79.6 2492.26    84.1 2489.78    92.3 2488.78
   120.9  2488.8   129.1 2488.14   145.4 2485.61     154 2485.77   161.8 2485.03
     170 2484.87   175.3 2485.14   186.3 2486.67   210.8 2488.33   231.3 2487.99
   239.4 2486.82   255.8 2488.03   268.9 2487.12   296.6 2489.22   304.8 2492.79
   341.6 2513.59   345.7 2514.49   353.8 2514.96   357.9 2516.31     367  2522.9
#Mann= 4 ,-1,0
       0      .1       0   161.8    .045       0   175.3      .1       0
  367.03     .06       0
#XS Ineff= 2 , 0
                           267.9         2498.78
Permanent Ineff=
       F       F
Bank Sta=161.8,175.3
XS Rating Curve= 0 ,0
Exp/Cntr(USF)=0,0
Exp/Cntr=0.3,0.1

Type RM Length L Ch R = 1 ,32521   ,156.4,155.8,154.1
XS GIS Cut Line= 2
2216548.98785066394052.6653331112216613.89452193394313.908370495
#Sta/Elev= 30
       0 2516.55     8.8 2508.39    19.6 2499.61    25.3 2494.31    33.5 2486.01
    37.6 2482.38    39.4 2481.82    41.7    2481    45.9 2480.91      50  2481.2
    54.1  2482.1    78.8 2484.37    91.2 2484.96   107.7  2484.7   115.9 2485.36
   132.4 2484.96   171.4  2485.8   174.7 2485.65   184.6 2483.85   190.1 2483.48
     219 2483.73   223.1 2484.06   227.2 2485.05   235.5 2490.21   240.8 2492.74
   243.7 2494.69   251.9 2501.69   256.1  2503.5   267.2 2504.52   269.2 2505.19
#Mann= 4 ,-1,0
       0      .1       0    39.4    .045       0    54.1      .1       0
     260     .06       0
#XS Ineff= 2 , 0
                           223.5         2494.49
Permanent Ineff=
       F       F
Bank Sta=39.4,54.1
XS Rating Curve= 0 ,0
Exp/Cntr(USF)=0,0
Exp/Cntr=0.3,0.1