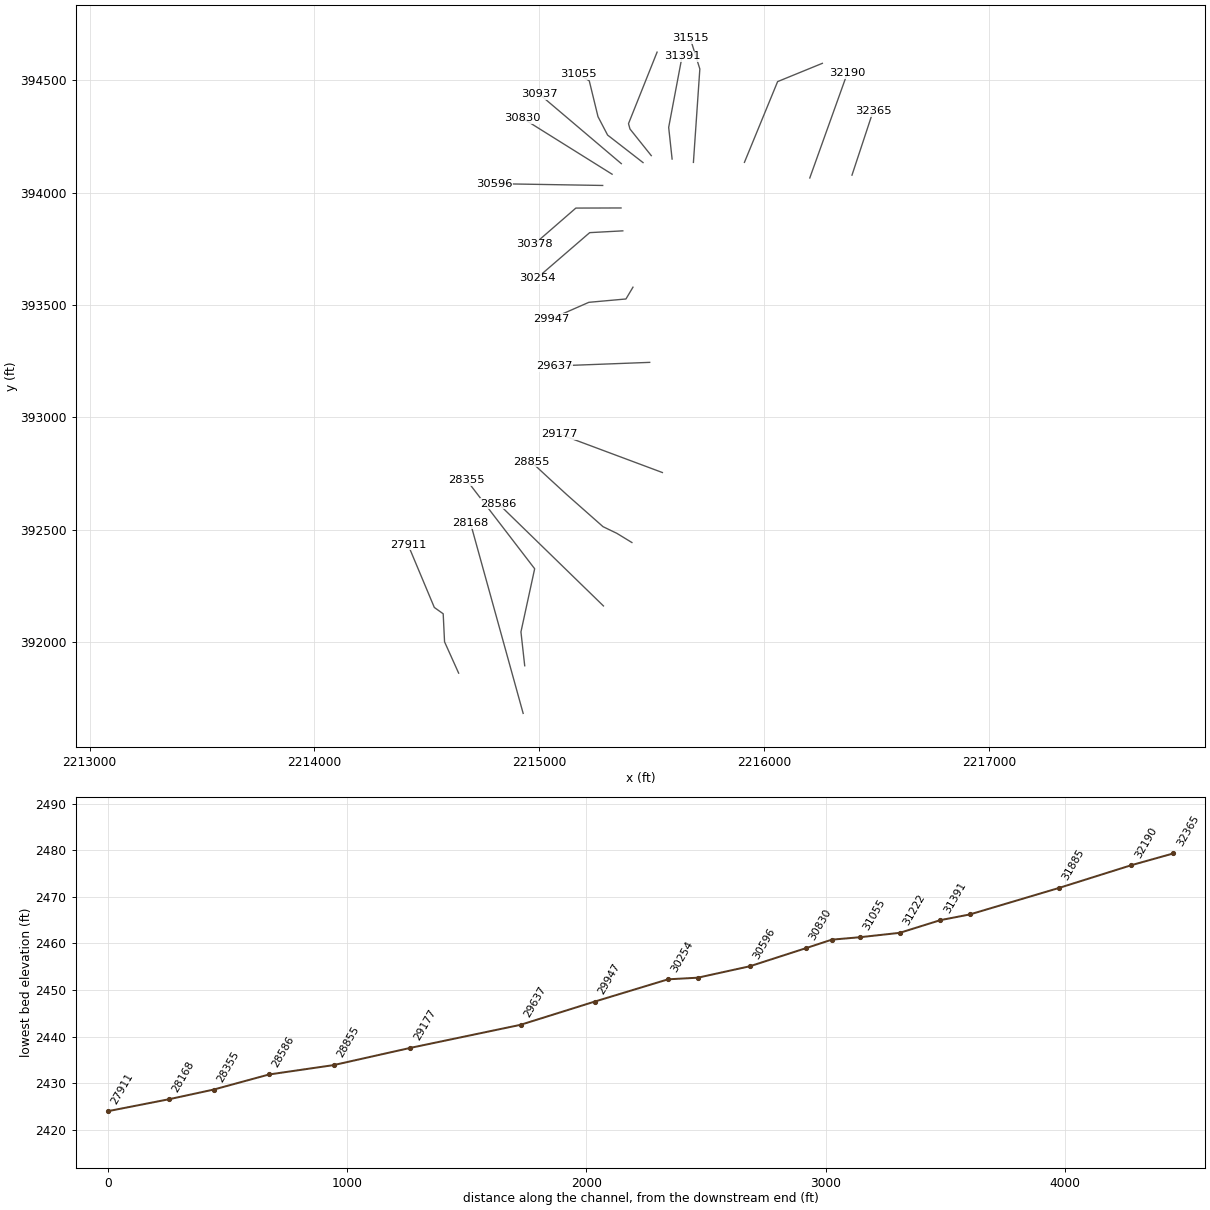
HEC-RAS study LAURELRN1.prj: LAURELRN1

--- LAURELRN1.g01 (geometry) --- (continued)

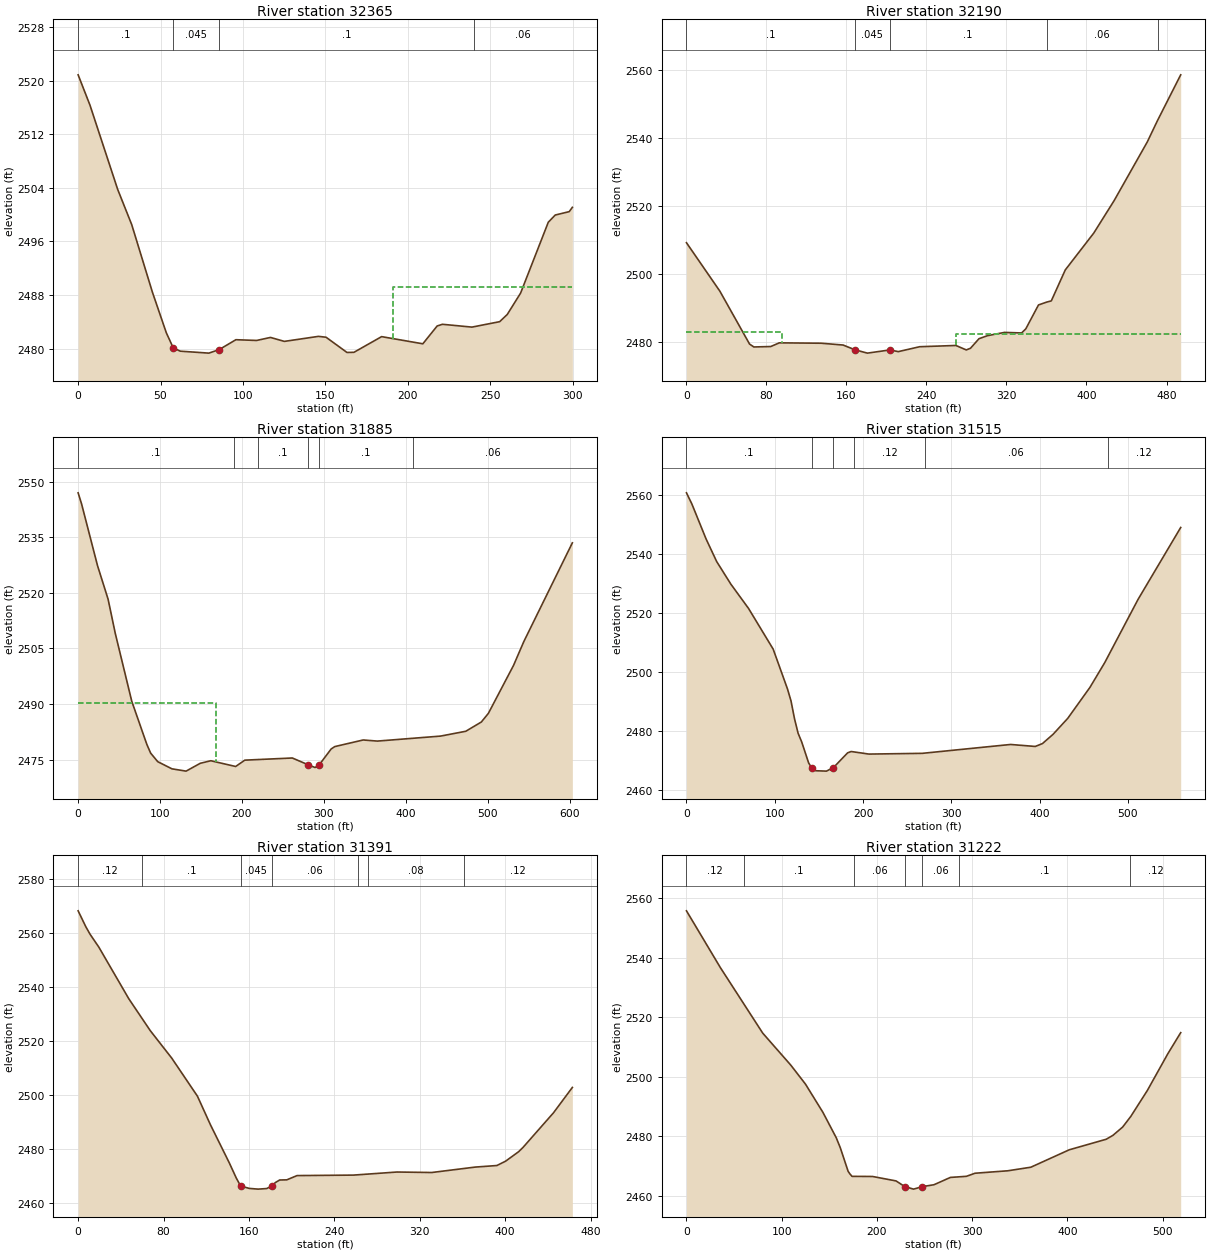
Type RM Length L Ch R = 1 ,32365   ,175.1,175.7,175.7
XS GIS Cut Line= 2
2216390.85285778394078.3525965692216484.87793383394363.030344658
#Sta/Elev= 30
       0 2520.85     7.2 2516.32      24 2503.76    32.5 2498.52    45.1 2488.41
    53.5 2482.38    57.7 2480.13      62 2479.64    79.3 2479.35    85.6 2479.88
    95.7 2481.35   108.3 2481.24   116.7 2481.69   125.1  2481.1   145.8 2481.85
   150.4 2481.72   163.1 2479.45   167.3 2479.47   184.1 2481.81   209.1 2480.74
   217.8  2483.4     221 2483.65   238.9 2483.23   255.7 2484.04   260.3 2485.11
   268.4  2488.3   285.2 2498.87   289.4 2499.94   297.9 2500.45   299.8 2501.09
#Mann= 4 ,-1,0
       0      .1       0    57.7    .045       0    85.6      .1       0
     240     .06       0
#XS Ineff= 2 , 0
                          190.78         2489.19
Permanent Ineff=
       F       F
Bank Sta=57.7,85.6
XS Rating Curve= 0 ,0
Exp/Cntr(USF)=0,0
Exp/Cntr=0.3,0.1

Type RM Length L Ch R = 1 ,32190   ,305.5,304.3,299.1
XS GIS Cut Line= 2
2216203.16771201394065.7717450162216369.82523819394531.024005604
#Sta/Elev= 30
       0 2509.27    33.4 2495.03    63.1 2479.48    67.4 2478.63    84.3 2478.76
    92.8 2479.84   134.8 2479.73   156.6  2479.2   168.42477.809   180.9 2476.82
   203.4 2477.76   211.8 2477.26   233.1  2478.7   269.4 2479.07   279.8 2477.76
     284 2478.25   292.5 2481.06     301 2481.95     318 2482.91   335.1 2482.75
   339.3 2483.95     352 2490.98   360.1 2491.81   364.8 2492.17   378.8 2501.28
   407.3 2512.12   427.7 2521.68   460.8  2538.9     471 2545.18   494.2 2558.62
#Mann= 5 ,-1,0
       0      .1       0   168.4    .045       0   203.4      .1       0
   360.1     .06       0     471      .1       0
#XS Ineff= 2 , 0
       0   95.34 2483.16   269.3       0 2482.38
Permanent Ineff=
       F       F
Bank Sta=168.4,203.4
XS Rating Curve= 0 ,0
Exp/Cntr(USF)=0,0
Exp/Cntr=0.3,0.1

Type RM Length L Ch R = 1 ,31885   ,365.2,370.3,368.8
XS GIS Cut Line= 3
2215912.54639166394135.2957117472216060.10774297394494.651002574
2216259.06088917394576.019085858
#Sta/Elev= 30
       0 2546.95     4.2 2543.97    23.7  2527.3    36.6 2518.26    45.3  2509.1
    65.5 2490.73    83.9 2479.11    88.5 2476.77    97.2 2474.45   114.5 2472.52
   131.8  2471.9   149.1 2474.01     162  2474.7   192.3 2473.15   203.5 2474.86
   261.5 2475.44   280.72473.628   289.3 2472.87  294.53 2473.66     309 2477.89
   313.4 2478.52     348  2480.3   365.3    2480   442.6 2481.35   473.3 2482.65
   492.3 2485.15   500.9 2487.49   531.6 2500.42   544.1 2506.82   603.4 2533.46
#Mann= 6 ,-1,0
       0      .1       0     190     .12       0     220      .1       0
   280.7    .045       0  294.53      .1       0  408.47     .06       0
#XS Ineff= 2 , 0
          168.39 2490.24
Permanent Ineff=
       F       F
Bank Sta=280.7,294.53
XS Rating Curve= 0 ,0
Exp/Cntr(USF)=0,0
Exp/Cntr=0.3,0.1

Type RM Length L Ch R = 1 ,31515   ,123.9,124.2,119.8
XS GIS Cut Line= 3
2215685.62435942394135.0699319682215714.20579053394550.902993999
2215671.43212774394687.220760051
#Sta/Elev= 30
       0 2560.75     6.1 2556.98    22.2 2545.09    34.2 2537.42    50.2 2529.77
    70.3 2521.49    98.2 2507.66   114.4 2494.15   118.4 2490.06   122.4 2483.97
   126.4 2479.12   130.4 2476.23   138.4 2468.99   141.6 2467.44   146.5 2466.37
   158.5 2466.24   166.5 2467.46   182.5 2472.45   186.5  2472.9   206.6 2472.03
     267 2472.28     367 2475.29     395 2474.62   403.1 2475.59   415.1 2478.72
   431.8 2484.17   456.9 2494.67   473.7  2503.1   511.4 2524.56   559.7 2548.98
#Mann= 6 ,-1,0
       0      .1       0   141.6    .045       0   166.5      .1       0
     190     .12       0     270     .06       0  476.81     .12       0
Bank Sta=141.6,166.5
XS Rating Curve= 0 ,0
Exp/Cntr(USF)=0,0
Exp/Cntr=0.3,0.1

Type RM Length L Ch R = 1 ,31391   ,196.6,169.1,207
XS GIS Cut Line= 3
2215590.84250982394149.9943999352215575.62118663394290.957088628
2215635.18288608394606.634095701
#Sta/Elev= 30
       0 2568.16     7.2 2562.27    11.2 2559.47    19.3 2554.77    47.5 2535.55
    67.6 2523.74    87.7 2513.56   111.8 2499.44   123.9  2488.9   141.8 2474.59
   148.1 2469.16   152.2 2466.16   160.3 2465.27   168.5    2465   176.6 2465.21
   181.8  2466.2   184.7 2467.42   188.8 2468.38   195.5 2468.44   205.1 2470.02
     258  2470.2   298.7 2471.34   331.3 2471.16     372 2473.17   392.3 2473.75
   400.5 2475.37   412.7 2478.88   416.8 2480.47   445.3 2493.28     463 2502.69
#Mann= 7 ,-1,0
       0     .12       0      60      .1       0   152.2    .045       0
   181.8     .06       0  261.78     .12       0  271.78     .08       0
  361.78     .12       0
Bank Sta=152.2,181.8
XS Rating Curve= 0 ,0
Exp/Cntr(USF)=0,0
Exp/Cntr=0.3,0.1

Type RM Length L Ch R = 1 ,31222   ,155.3,166.2,178.7
XS GIS Cut Line= 4
2215498.19097735394165.2157231272215403.55405489394283.677325362
2215396.94474488394307.4781995032215524.04433009394625.824034707
#Sta/Elev= 30
       0 2555.76    35.6 2536.69    80.1 2514.68   109.6 2503.92     125 2497.55
   143.3 2488.08   157.3 2479.55   161.5 2476.23   169.8 2468.26   171.8 2467.34
   173.9 2466.57   195.4 2466.53   220.1 2465.04  229.15 2463.16   238.5 2462.28
247.66662463.109     260 2463.76   277.2 2466.21     294 2466.58   303.1 2467.62
   337.5 2468.44   361.7 2469.64   402.1  2475.5   440.9 2479.04   447.9 2480.34
   458.1 2483.12   466.7 2486.71     484 2495.38   505.5 2507.71   519.1 2514.84
#Mann= 7 ,-1,0
       0     .12       0      60      .1       0  176.32     .06       0
  229.15    .045       0247.6666     .06       0  286.32      .1       0
  466.32     .12       0
Bank Sta=229.15,247.6666
XS Rating Curve= 0 ,0
Exp/Cntr(USF)=0,0
Exp/Cntr=0.3,0.1

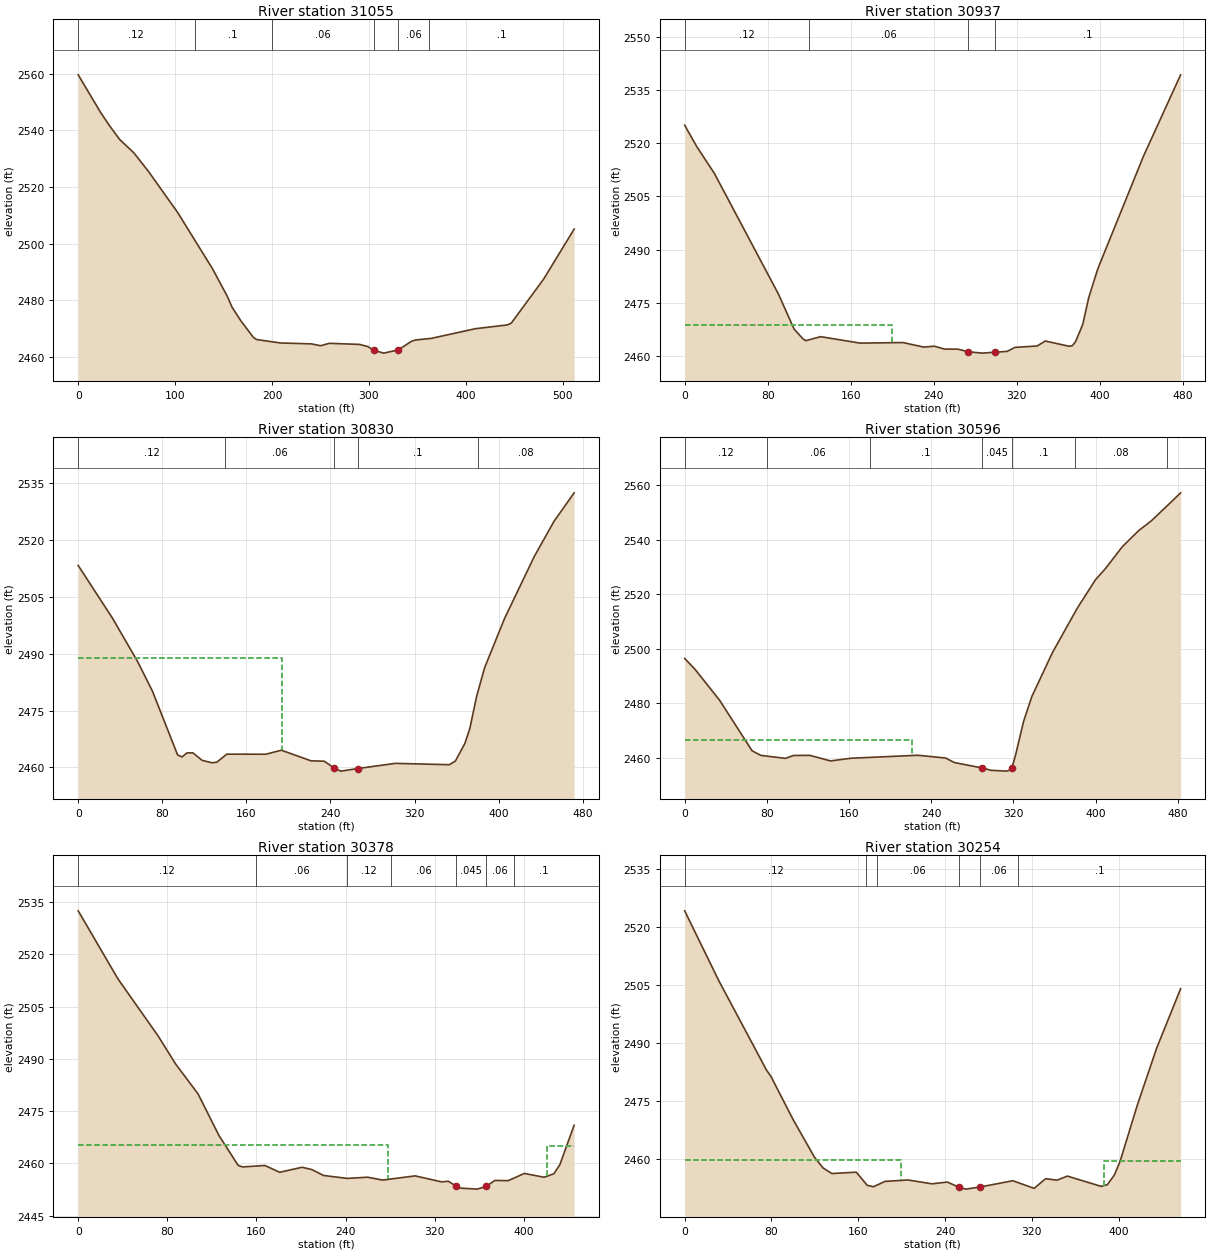
Type RM Length L Ch R = 1 ,31055   ,108.2,118.1,131.1
XS GIS Cut Line= 5
 2215461.5072118394134.2918236512215303.96124216394256.709952971
2215261.26777288394338.606448186 2215222.4680157394497.972886291
2215175.29597835394527.713488356
#Sta/Elev= 30
       0 2559.65      23 2546.43    32.1 2541.78    42.9 2536.76    57.4  2532.1
    72.6 2525.48   102.8 2510.93   138.5 2491.19   153.7 2481.49   158.7  2477.6
   167.7 2472.82   180.7 2466.91     184 2466.15   208.6 2464.93   240.6 2464.61
   250.1 2463.95     259  2464.8   290.3 2464.42   298.6 2463.68   304.8  2462.4
   315.1 2461.34   330.3 2462.48   343.9 2465.54     348 2465.97   364.6 2466.57
   409.8 2469.97   442.7  2471.3   446.8 2471.92   480.2 2487.48   511.7 2505.16
#Mann= 6 ,-1,0
       0     .12       0     120      .1       0  199.52     .06       0
   304.8    .045       0   330.3     .06       0  361.87      .1       0
Bank Sta=304.8,330.3
XS Rating Curve= 0 ,0
Exp/Cntr(USF)=0,0
Exp/Cntr=0.3,0.1

Type RM Length L Ch R = 1 ,30937   ,104.2,107,109.1
XS GIS Cut Line= 2
2215364.97557436394129.5269457582215000.70707285394438.576261218
#Sta/Elev= 30
       0 2525.05    11.5  2519.1    28.7 2511.42    90.2 2477.52   105.3 2467.65
   113.8 2464.86   116.7 2464.31   130.9 2465.45   168.9 2463.63   210.3 2463.79
   230.2 2462.52   240.6 2462.76   250.1 2461.96   263.3 2461.92   273.32461.185
   286.8 2460.81   298.62461.078   310.5 2461.29   318.2 2462.43   339.5 2462.82
   347.3 2464.22   370.4 2462.74   373.5 2462.93   376.6 2464.09   383.4 2468.87
   389.2 2476.46   397.6 2484.25   399.7 2485.85   441.7 2516.17   477.7 2539.25
#Mann= 4 ,-1,0
       0     .12       0     120     .06       0   273.3    .045       0
   298.6      .1       0
#XS Ineff= 2 , 0
          199.44 2468.82
Permanent Ineff=
       F       F
Bank Sta=273.3,298.6
XS Rating Curve= 0 ,0
Exp/Cntr(USF)=0,0
Exp/Cntr=0.3,0.1

Type RM Length L Ch R = 1 ,30830   ,228,234.8,243.9
XS GIS Cut Line= 2
 2215323.9486539394082.5313488562214924.02394316394332.768148397
#Sta/Elev= 30
       0 2513.28    32.8 2499.28    56.4 2487.97    70.5 2480.19    94.6 2463.25
    98.8 2462.75   103.5 2463.81   109.1 2463.82   117.9 2461.85   127.1 2461.21
   131.9 2461.36   141.3 2463.48   178.4 2463.46   193.3 2464.52   221.5 2461.72
     234 2461.62   243.1  2459.9   249.8    2459   265.9 2459.68   301.7 2461.05
     353  2460.7   358.8 2461.65   367.8 2466.28   372.5 2470.19   379.1 2478.82
   386.6 2486.27   405.5 2499.23   433.8 2515.61   452.7 2524.96   471.8 2532.45
#Mann= 5 ,-1,0
       0     .12       0     140     .06       0   243.1    .045       0
   265.9      .1       0     380     .08       0
#XS Ineff= 2 , 0
           193.8 2488.91
Permanent Ineff=
       F       F
Bank Sta=243.1,265.9
XS Rating Curve= 0 ,0
Exp/Cntr(USF)=0,0
Exp/Cntr=0.3,0.1

Type RM Length L Ch R = 1 ,30596   ,209.1,217.8,232.6
XS GIS Cut Line= 2
2215282.14679528394032.4480541582214799.42423338394040.463742455
#Sta/Elev= 30
       0 2496.41      10 2492.48      34 2481.09    65.6 2462.57      74 2460.88
      98 2459.78     106 2460.84     122 2460.88     142 2458.84     162 2459.83
     227 2460.92     254  2459.9   262.4 2458.27   289.9 2456.23   298.2  2455.4
   313.5  2455.1     318 2455.65   318.6 2456.39     322 2460.81     330 2473.42
     338 2482.48     358 2498.55     382 2514.72   399.9 2525.26     410 2529.53
     426 2537.37     442  2543.3     454 2546.77     470 2552.49   482.8 2557.14
#Mann= 7 ,-1,0
       0     .12       0      80     .06       0     180      .1       0
   289.9    .045       0   318.6      .1       0     380     .08       0
     470      .1       0
#XS Ineff= 2 , 0
          221.41 2466.59
Permanent Ineff=
       F       F
Bank Sta=289.9,318.6
XS Rating Curve= 0 ,0
Exp/Cntr(USF)=0,0
Exp/Cntr=0.3,0.1

Type RM Length L Ch R = 1 ,30378   ,124.2,124.2,123.8
XS GIS Cut Line= 3
2215363.76138932393932.3028070982215162.80210286393931.806634426
2214978.43594077393771.510665227
#Sta/Elev= 30
       0  2532.5    35.6 2513.01    71.6 2496.67    87.6 2488.49   107.6 2479.97
   126.4 2468.02   143.6 2459.46   147.6 2459.01   167.6 2459.43   180.9 2457.48
     201 2458.91   209.7 2458.26   220.3 2456.56   241.5 2455.72   259.8 2456.06
   273.3 2455.24   302.5 2456.44   326.4 2454.72   332.3  2454.9   339.1 2453.56
   342.3 2452.95   358.2 2452.64   366.3 2453.42   374.1 2455.13   386.1 2455.07
   400.6 2457.14   418.3 2456.05   427.1 2457.05   432.4 2459.61   445.3 2470.97
#Mann= 7 ,-1,0
       0     .12       0     160     .06       0  240.96     .12       0
  280.96     .06       0   339.1    .045       0   366.3     .06       0
  390.96      .1       0
#XS Ineff= 2 , 0
          278.03 2465.23  420.82         2465.06
Permanent Ineff=
       F       F
Bank Sta=339.1,366.3
XS Rating Curve= 0 ,0
Exp/Cntr(USF)=0,0
Exp/Cntr=0.3,0.1

Type RM Length L Ch R = 1 ,30254   ,311.7,306.3,289.7
XS GIS Cut Line= 3
2215371.58271044  393830.43340042215224.26672765393822.446389285
2214989.98106827393620.108774364
#Sta/Elev= 30
       0 2524.29    31.5 2506.19    75.5 2483.05    79.5 2481.46    99.6 2470.46
   119.6 2460.56   127.6 2457.76   135.6 2456.33   158.2 2456.67   168.3 2453.27
     174 2452.91   184.7 2454.29   205.8 2454.66   227.9 2453.66   242.1 2454.12
   252.4 2452.83   259.1 2452.29   271.9 2452.83   302.5 2454.46   322.1 2452.49
   332.6 2454.98   343.2 2454.62   352.7 2455.66   383.9    2453   389.6 2453.44
   396.1 2455.97   401.3 2459.47   417.2 2474.03   434.9 2488.68   457.1 2504.14
#Mann= 6 ,-1,0
       0     .12       0  167.53      .1       0  177.53     .06       0
   252.4    .045       0   271.9     .06       0  307.53      .1       0
#XS Ineff= 2 , 0
          199.15 2459.87  386.36         2459.52
Permanent Ineff=
       F       F
Bank Sta=252.4,271.9
XS Rating Curve= 0 ,0
Exp/Cntr(USF)=0,0
Exp/Cntr=0.3,0.1

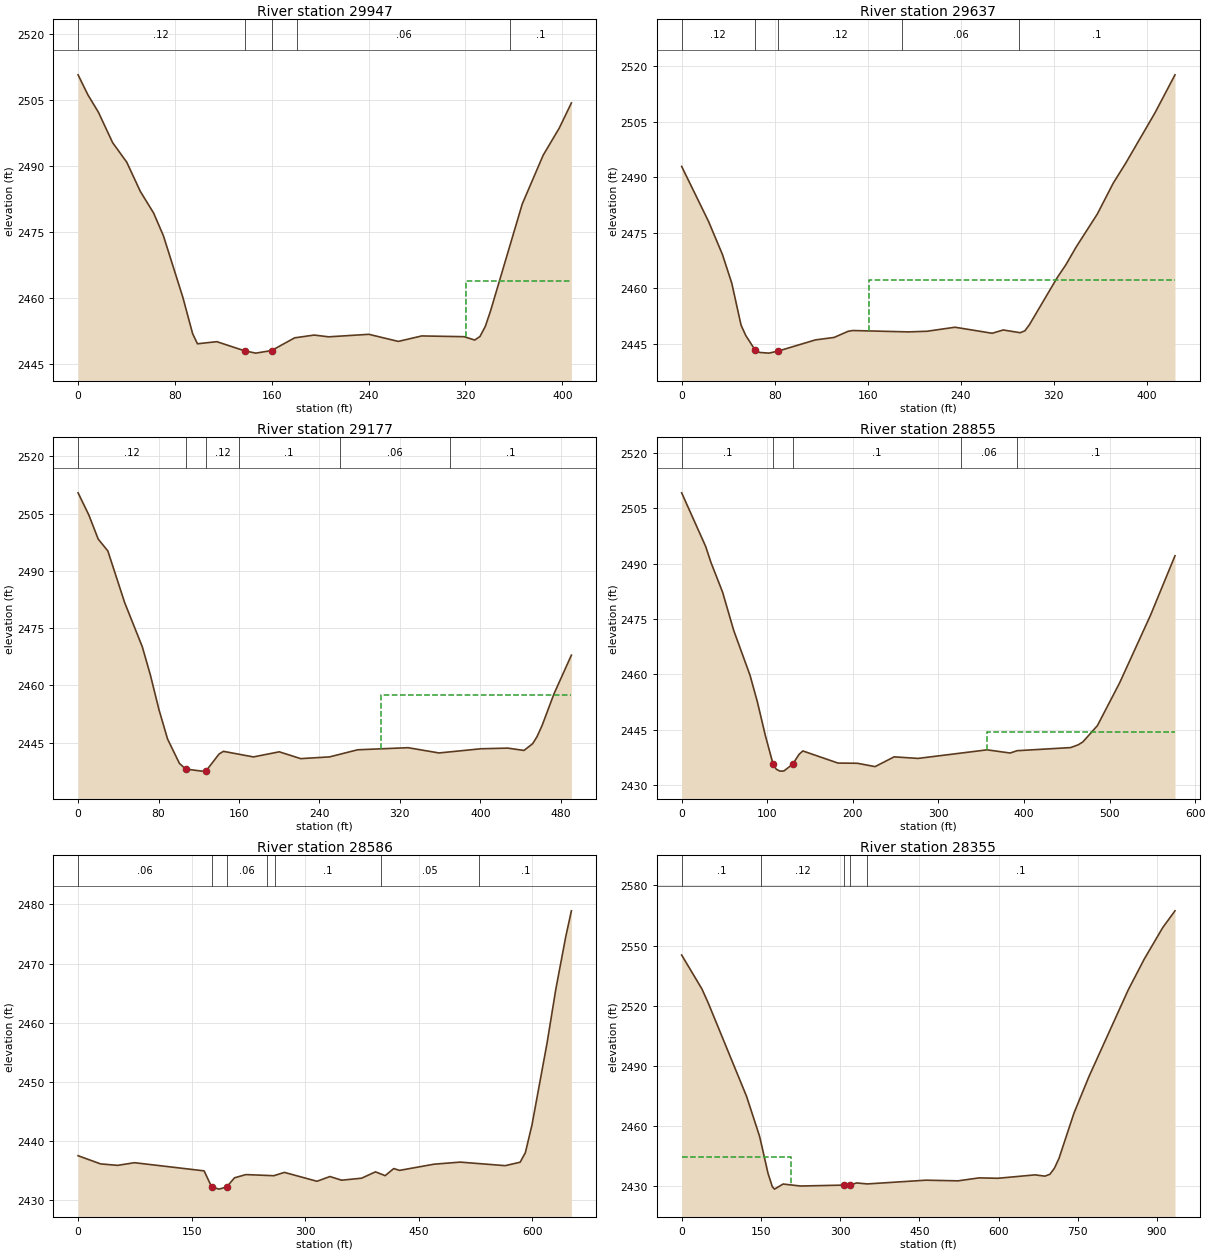
Type RM Length L Ch R = 1 ,29947   ,313.6,310.4,313
XS GIS Cut Line= 4
2215416.77467439393579.6879215882215385.57394556393527.241459227
 2215220.5558494393512.3627784252215055.05034261393439.665991165
#Sta/Elev= 30
       0 2510.66     8.1 2506.13    16.9 2502.12    28.5 2495.29    40.2 2490.84
    51.4 2484.22    62.4  2479.3    70.5 2474.13    86.5 2460.22    94.6 2451.95
    98.6 2449.63   114.6 2450.11137.59322448.033   146.8 2447.51159.79312448.092
   178.9 2450.98     195 2451.61     207 2451.21   240.2 2451.78   264.5 2450.17
   283.9 2451.41   318.9 2451.24   327.6 2450.48     332 2451.29   336.4 2453.59
   340.7 2457.08   366.9 2481.35   384.2 2492.43   397.5 2498.59   407.5 2504.28
#Mann= 5 ,-1,0
       0     .12       0137.5932    .045       0159.7931     .12       0
  181.03     .06       0  356.71      .1       0
#XS Ineff= 2 , 0
                          320.38          2463.9
Permanent Ineff=
       F       F
Bank Sta=137.5932,159.7931
XS Rating Curve= 0 ,0
Exp/Cntr(USF)=0,0
Exp/Cntr=0.3,0.1

Type RM Length L Ch R = 1 ,29637   ,465.1,459.8,453.6
XS GIS Cut Line= 2
2215491.22835703393245.1301546182215067.07122162393228.980299963
#Sta/Elev= 30
       0  2492.9    23.1 2478.07    35.1 2469.12    43.1 2461.41    51.1 2450.08
    55.1  2447.3    63.1 2443.38    67.1 2442.69    75.1 2442.51    83.1 2443.07
   115.1 2446.08   131.1 2446.74   143.2 2448.39   147.2 2448.61   195.2 2448.24
   211.1 2448.41   235.2  2449.5   267.2 2447.87   276.7 2448.76   291.3 2448.02
   295.3 2448.53   299.3 2450.21     323 2462.81   330.7  2466.4   339.3 2471.07
   357.7 2480.07   371.3 2488.35   381.9 2493.67   407.3 2507.37   424.5 2517.62
#Mann= 5 ,-1,0
       0     .12       0    63.1    .045       0    83.1     .12       0
     190     .06       0     290      .1       0
#XS Ineff= 2 , 0
                          160.85         2462.36
Permanent Ineff=
       F       F
Bank Sta=63.1,83.1
XS Rating Curve= 0 ,0
Exp/Cntr(USF)=0,0
Exp/Cntr=0.3,0.1

Type RM Length L Ch R = 1 ,29177   ,322.9,321.6,319.9
XS GIS Cut Line= 2
2215547.58859579392754.8361950262215088.03012509392926.500973636
#Sta/Elev= 30
       0 2510.46    10.7 2504.66      20 2498.35    29.6 2495.24    46.3 2481.73
    63.9 2470.11      72 2462.64    80.5 2453.61      89 2445.97   100.8 2439.58
   107.1  2438.1   123.2 2437.56   127.5  2437.7   140.3 2442.07   144.6 2442.74
   174.4 2441.28   200.1 2442.62   221.4 2440.83   250.1 2441.29     278 2443.15
   328.2  2443.7   358.9 2442.32   400.8 2443.42   427.3 2443.59   443.4 2442.98
     452 2444.73   456.3 2446.53   461.5 2449.54   473.3 2457.83   490.6 2467.94
#Mann= 6 ,-1,0
       0     .12       0   107.1    .045       0   127.5     .12       0
     160      .1       0     260     .06       0     370      .1       0
#XS Ineff= 2 , 0
                          300.85         2457.51
Permanent Ineff=
       F       F
Bank Sta=107.1,127.5
XS Rating Curve= 0 ,0
Exp/Cntr(USF)=0,0
Exp/Cntr=0.3,0.1

Type RM Length L Ch R = 1 ,28855   ,272.4,269.3,259.7
XS GIS Cut Line= 6
 2215412.0540077  392443.33892452215344.92984618 392484.30306183
2215283.57557699 392513.884584482215122.52062034392656.314137976
2215040.87680139392731.2986452122214964.75249954392802.030527322
#Sta/Elev= 30
       0 2509.15      28 2494.67    34.2 2490.33    47.8 2482.29    60.8 2471.94
    79.9 2459.78    88.4 2452.66    97.8 2443.49   106.8 2435.76   110.6 2434.36
     115 2433.85   119.4 2433.89   129.8 2435.73   137.2  2438.4   141.6 2439.31
   182.7 2436.03   205.3 2435.98     226 2435.07   248.3 2437.71   276.2 2437.29
     357 2439.61   383.8 2438.75   392.1 2439.38   454.6 2440.22   463.6 2440.99
   468.8 2441.75   485.8 2446.15   511.8 2457.73     548 2476.09   576.5 2492.12
#Mann= 5 ,-1,0
       0      .1       0   106.8    .045       0   129.8      .1       0
  326.75     .06       0  391.75      .1       0
#XS Ineff= 2 , 0
                          356.96         2444.45
Permanent Ineff=
       F       F
Bank Sta=106.8,129.8
XS Rating Curve= 0 ,0
Exp/Cntr(USF)=0,0
Exp/Cntr=0.3,0.1

Type RM Length L Ch R = 1 ,28586   ,423,231.1,401.9
XS GIS Cut Line= 2
2215285.48100199392161.1080401262214818.83146774392615.584108263
#Sta/Elev= 30
       0 2437.49    29.7 2436.11    52.1 2435.86    74.5 2436.31   166.4 2434.93
   176.4  2432.2   186.1 2431.84   196.2  2432.2   206.5 2433.75   221.6  2434.3
   258.4 2434.11   272.5 2434.67   315.4 2433.17   332.6 2433.97     348 2433.35
   374.4 2433.69   392.7 2434.76   405.5 2434.12   416.8 2435.32   424.4 2435.01
   470.2 2436.06   504.6 2436.41   563.9 2435.81   583.7 2436.39   590.6 2438.01
   599.3 2442.67   619.3 2456.58   630.7 2465.56   643.9 2474.52   651.4 2478.91
#Mann= 7 ,-1,0
       0     .06       0   176.4    .045       0   196.2     .06       0
     250     .12       0     260      .1       0     400     .05       0
     530      .1       0
Bank Sta=176.4,196.2
XS Rating Curve= 0 ,0
Exp/Cntr(USF)=0,0
Exp/Cntr=0.3,0.1

Type RM Length L Ch R = 1 ,28355   ,106.8,186.9,120.2
XS GIS Cut Line= 4
2214935.33880394 391894.893197882214918.59570391392045.581098128
2214979.58842544392326.625991448 2214678.3585498392719.402438307
#Sta/Elev= 30
       0 2545.33    38.5 2528.35    50.6 2521.25     123  2474.8   147.2 2455.22
     1502452.173   163.5  2436.5   171.7 2429.79   175.8  2428.6   192.1 2431.14
   224.9 2430.15   307.3 2430.61     319 2430.61   331.3 2431.69  351.622431.195
   462.6 2433.06   523.3 2432.73   563.3 2434.21   598.7 2434.01   669.3 2435.71
     688 2435.08   697.4 2436.02   705.9 2439.03   714.5 2443.91     743 2466.58
   771.5 2484.86   845.7 2527.97   875.9 2543.27   911.2  2559.1   934.2 2567.37
#Mann= 5 ,-1,0
       0      .1       0     150     .12       0   307.3    .045       0
     319     .12       0  351.62      .1       0
#XS Ineff= 2 , 0
          206.76 2444.63
Permanent Ineff=
       F       F
Bank Sta=307.3,319
XS Rating Curve= 0 ,0
Exp/Cntr=0.3,0.1

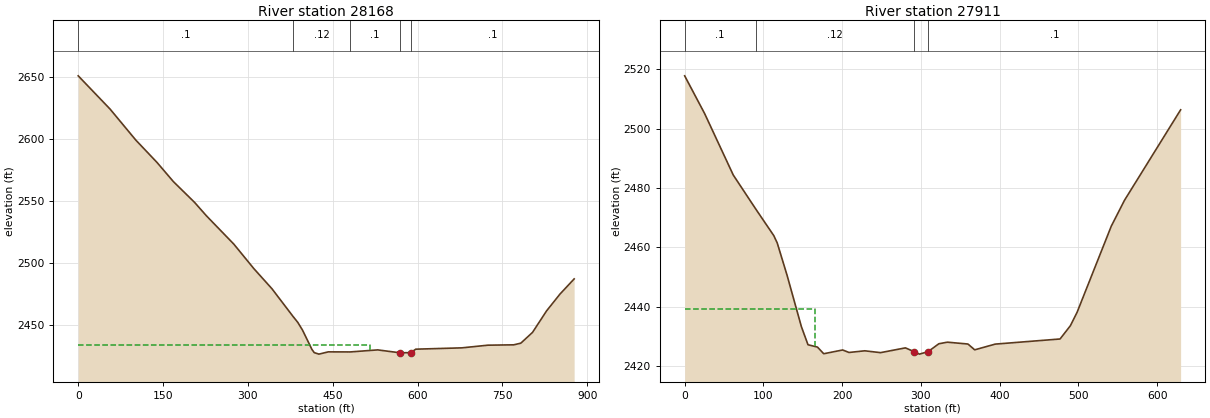
Type RM Length L Ch R = 1 ,28168   ,246.8,256.5,260.2
XS GIS Cut Line= 2
 2214928.3989264 391682.958742282214694.58755929392528.062178406
#Sta/Elev= 30
       0 2651.27    56.3 2624.43   101.9 2599.35   139.3 2581.34   168.3 2565.84
   205.7 2549.08   226.6 2538.27   275.1 2515.38   310.8 2495.45   342.6 2479.31
     380 2456.86   388.3 2452.12   396.6 2445.92   413.2 2430.36   417.3 2427.75
   425.6 2426.52   442.2 2428.35   480.9 2428.29   529.4 2429.94568.68932427.615
587.68922427.703   596.9 2430.52   678.2 2431.58   724.4 2433.74   770.1 2434.03
   782.6 2435.37   803.3 2444.08   828.2 2461.49     852 2475.09   876.9 2487.26
#Mann= 5 ,-1,0
       0      .1       0     380     .12       0   480.9      .1       0
568.6893    .045       0587.6892      .1       0
#XS Ineff= 2 , 0
          516.61 2433.56
Permanent Ineff=
       F       F
Bank Sta=568.6893,587.6892
XS Rating Curve= 0 ,0
Exp/Cntr(USF)=0,0
Exp/Cntr=0.3,0.1

Type RM Length L Ch R = 1 ,27911   ,129.8,129.9,122.7
XS GIS Cut Line= 5
2214641.50362672 391862.044080312214578.81194659392001.389627326
2214572.78945936392126.1847585962214533.32391904392154.319336501
2214416.06901433 392434.40207211
#Sta/Elev= 30
       0 2517.85    25.4 2505.08    61.7 2484.38      902473.009   113.1 2463.96
   117.5 2461.48     130 2450.58   148.2 2433.22   156.6  2427.1   168.6 2426.32
   176.6 2424.07   200.6 2425.34   208.7  2424.5   228.7 2425.06   248.7 2424.44
   280.3 2426.05   291.8 2424.73   298.1 2423.94     309 2424.76   322.7 2427.43
   333.6 2427.97   359.7 2427.35   368.3 2425.39   394.4 2427.32   476.7 2429.05
   489.8 2433.53   498.4  2438.1   541.8 2467.15   558.5 2475.84   629.8 2506.38
#Mann= 4 ,-1,0
       0      .1       0      90     .12       0   291.8    .045       0
     309      .1       0
#XS Ineff= 2 , 0
          165.12 2439.02
Permanent Ineff=
       F       F
Bank Sta=291.8,309
XS Rating Curve= 0 ,0
Exp/Cntr=0.3,0.1