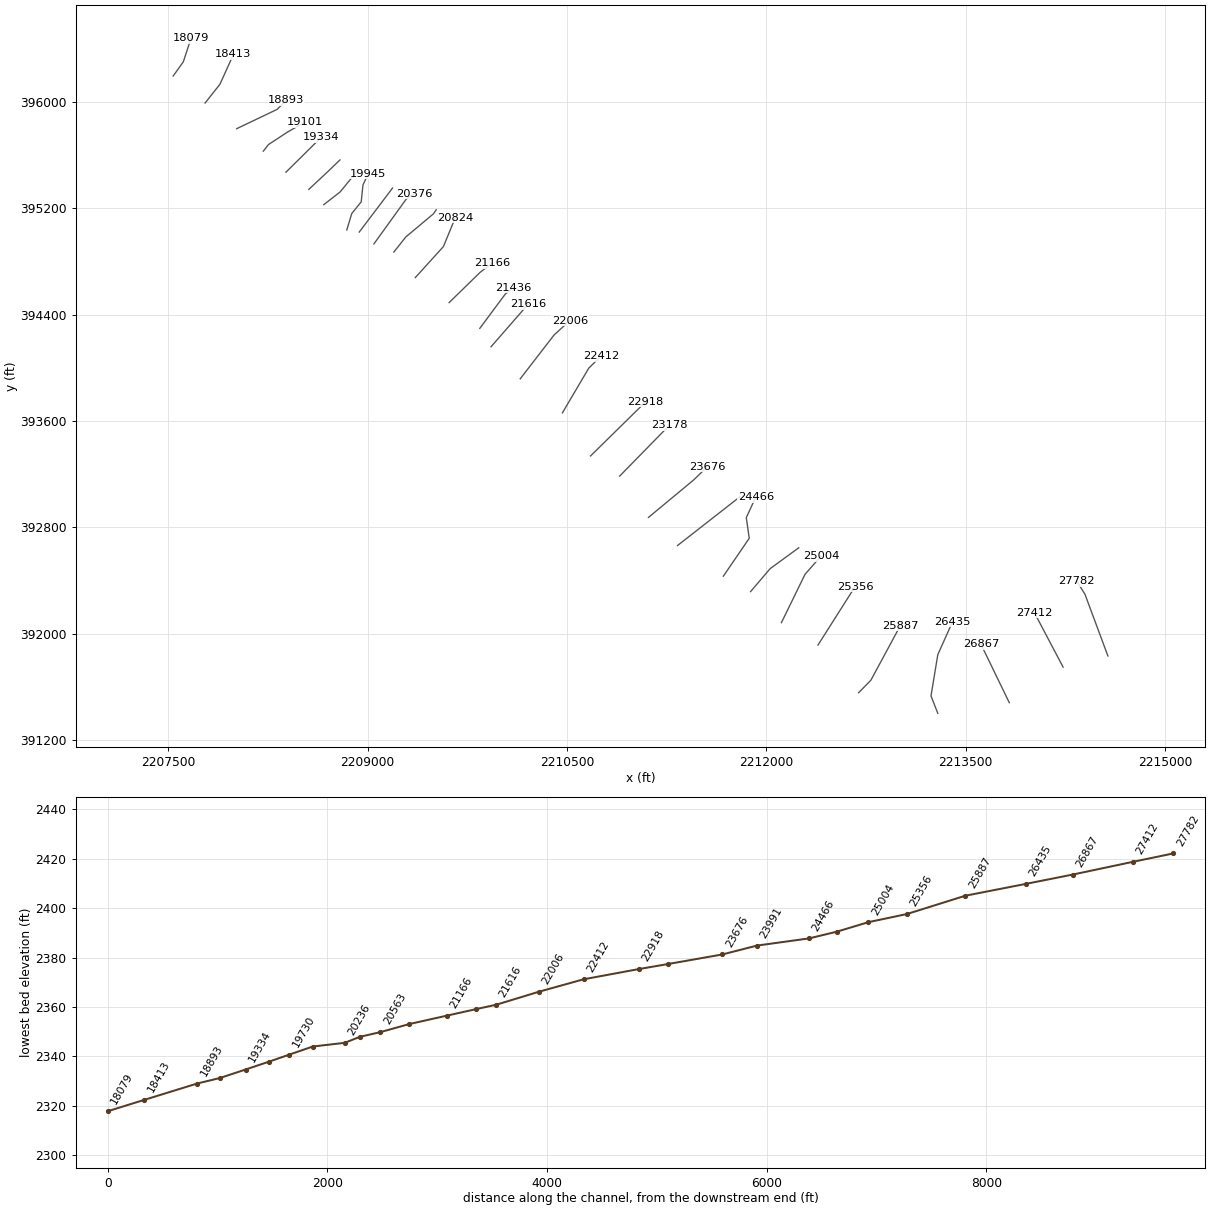
HEC-RAS study LAURELRN1.prj: LAURELRN1

--- LAURELRN1.g01 (geometry) --- (continued)

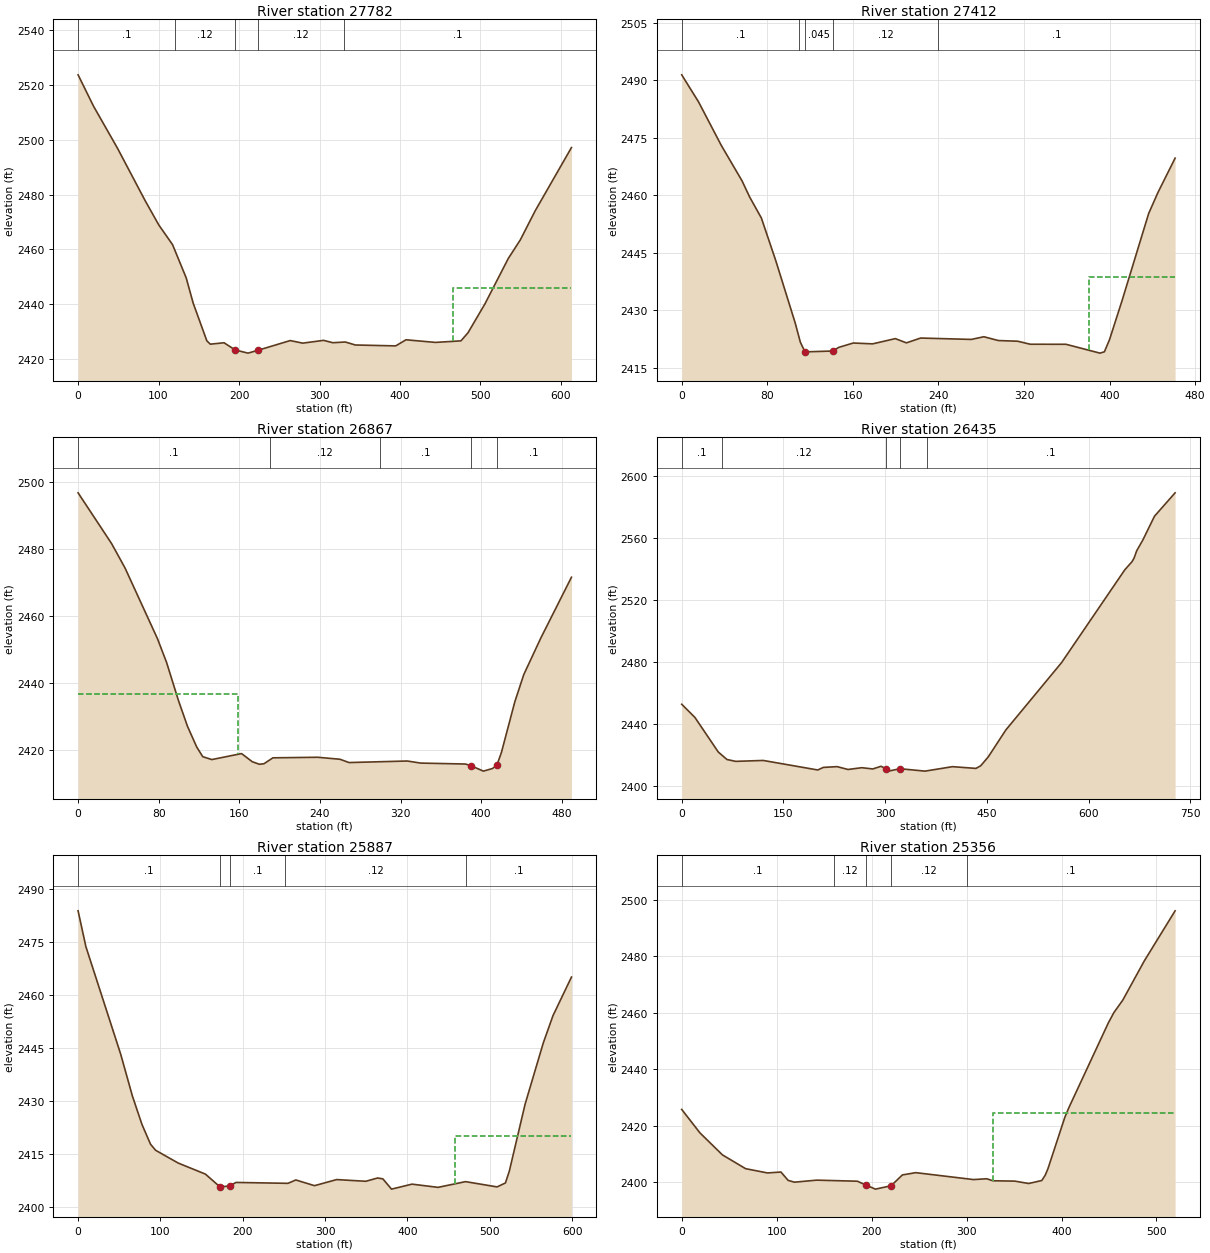
Type RM Length L Ch R = 1 ,27782   ,367.7,369.4,370.9
XS GIS Cut Line= 3
2214569.09951041391831.160755166 2214396.8179759392295.016167345
2214334.31607315392395.426567144
#Sta/Elev= 30
       0 2523.72    19.2 2512.28    49.1 2496.87    83.2 2477.89   100.3 2468.94
   117.4 2461.76   134.4 2449.61     143 2440.45     160 2426.67   164.3 2425.45
   181.4 2425.96   195.2 2423.34   211.2 2422.18     224 2423.26   263.6 2426.76
   279.2 2425.82   305.1 2426.84   316.5 2425.98   332.1 2426.24   344.5 2425.15
   394.7 2424.82   407.5 2427.05   444.1 2426.09   475.8 2426.66   484.6 2429.64
   505.6 2440.16   534.6 2456.71   549.5 2463.47     568 2474.09   613.1 2497.18
#Mann= 5 ,-1,0
       0      .1       0     120     .12       0   195.2    .045       0
     224     .12       0     330      .1       0
#XS Ineff= 2 , 0
                          466.28         2446.05
Permanent Ineff=
       F       F
Bank Sta=195.2,224
XS Rating Curve= 0 ,0
Exp/Cntr(USF)=0,0
Exp/Cntr=0.3,0.1

Type RM Length L Ch R = 1 ,27412   ,541.6,545.3,538.8
XS GIS Cut Line= 2
 2214232.1627747391747.3147082952214017.02749821392155.388764497
#Sta/Elev= 30
       0 2491.48    15.7 2484.43    36.9 2473.09    56.4 2463.78    63.5 2459.57
    74.5 2454.05      88 2442.88   106.1 2426.65   110.9 2421.65   115.2  2419.1
   141.22419.319   146.8 2420.27   160.4 2421.41   178.5 2421.19   199.7 2422.56
   210.1 2421.45   223.4 2422.71   270.8 2422.35   282.5 2423.05     296 2422.06
   314.1 2421.88   325.9 2421.09   359.3 2421.08     391 2418.77   395.2 2419.12
     400  2422.3   411.7 2432.48   436.6 2455.26   445.2  2460.7   461.3 2469.71
#Mann= 5 ,-1,0
       0      .1       0     110     .12       0   115.2    .045       0
   141.2     .12       0     240      .1       0
#XS Ineff= 2 , 0
                           380.4         2438.54
Permanent Ineff=
       F       F
Bank Sta=115.2,141.2
XS Rating Curve= 0 ,0
Exp/Cntr(USF)=0,0
Exp/Cntr=0.3,0.1

Type RM Length L Ch R = 1 ,26867   ,436.6,431.5,416.6
XS GIS Cut Line= 2
2213827.50356416391479.249324095 2213614.0757105391919.764414054
#Sta/Elev= 30
       0 2496.72    33.3 2481.54    46.6 2474.27    78.8 2453.15    87.8 2446.08
    99.7 2434.61   108.5 2427.05   117.7 2420.84   123.7 2417.94   132.7 2417.08
   162.2 2418.87   172.8 2416.44   179.9 2415.68   184.4 2415.83   193.3  2417.6
   237.7 2417.77   259.9 2417.17   268.8 2416.19   326.6 2416.65   339.9 2416.03
   384.4 2415.75   390.2  2415.2   402.1 2413.63   411.1  2414.4   415.5  2415.4
     420 2419.18   433.3 2434.32   442.2 2442.46     459  2453.3   489.5 2471.52
#Mann= 5 ,-1,0
       0      .1       0     190     .12       0     300      .1       0
   390.2    .045       0   415.5      .1       0
#XS Ineff= 2 , 0
          158.22 2436.65
Permanent Ineff=
       F       F
Bank Sta=390.2,415.5
XS Rating Curve= 0 ,0
Exp/Cntr(USF)=0,0
Exp/Cntr=0.3,0.1

Type RM Length L Ch R = 1 ,26435   ,549.5,548.2,538.6
XS GIS Cut Line= 4
2213289.66537293391399.0004511182213238.44268805391530.472008974
2213289.66537293391841.2229639062213400.64785684392088.799274154
#Sta/Elev= 30
       0 2452.85    19.5 2444.35    53.9 2422.12    66.7  2417.3    79.6  2416.1
   120.2 2416.69   200.6 2410.56   208.7  2412.2     229 2412.72   245.2 2410.88
   265.5 2412.03   281.7 2411.22   293.8 2412.94   301.6 2411.27     306 2409.93
   321.82411.368   358.7 2409.82   399.2 2412.69   433.8 2411.57   440.8 2413.27
   451.9 2418.96   477.9 2436.34     560 2479.63   653.3  2539.4   663.7 2544.49
   666.8 2546.76   670.8 2551.62   679.6 2558.34     697 2573.84   727.4  2588.9
#Mann= 5 ,-1,0
       0      .1       0      60     .12       0   301.6    .045       0
   321.8     .12       0   361.1      .1       0
Bank Sta=301.6,321.8
XS Rating Curve= 0 ,0
Exp/Cntr(USF)=0,0
Exp/Cntr=0.3,0.1

Type RM Length L Ch R = 1 ,25887   ,528.5,531.5,532.3
XS GIS Cut Line= 3
2212693.77480551391554.3759285842212785.97563829391648.284184196
 2213007.9406061392059.773086056
#Sta/Elev= 30
       0 2483.76     9.5 2473.62    51.8 2443.18    65.9 2431.43    77.6 2423.33
      88 2417.74    94.2 2416.03   121.6 2412.42   154.6  2409.3   172.3 2405.69
   184.1 2405.94   191.7 2406.94   254.9 2406.69   264.4 2407.64   287.1 2406.03
     314 2407.75   349.4 2407.27   363.7  2408.2   370.1 2407.95   380.6 2405.05
   405.5 2406.46   437.1 2405.55   470.5 2407.17   508.8 2405.68   518.9 2406.79
   523.6 2410.09   542.8 2429.07   564.9  2446.4   576.7 2454.13   599.1 2465.02
#Mann= 5 ,-1,0
       0      .1       0   172.3    .045       0   184.1      .1       0
   251.6     .12       0   471.6      .1       0
#XS Ineff= 2 , 0
                          457.14         2420.07
Permanent Ineff=
       F       F
Bank Sta=172.3,184.1
XS Rating Curve= 0 ,0
Exp/Cntr(USF)=0,0
Exp/Cntr=0.3,0.1

Type RM Length L Ch R = 1 ,25356   ,348.6,351.3,352.2
XS GIS Cut Line= 2
2212388.14611906391912.9347227372212666.45604024392351.742389866
#Sta/Elev= 30
       0 2425.85    19.2 2417.55    42.9 2409.76    67.3 2404.88    90.3 2403.37
   104.5 2403.69   112.1 2400.73   118.7  2400.1   142.2 2400.82     185 2400.44
   194.2 2399.05     204 2397.64   220.5 2398.83   232.4 2402.67   246.5 2403.47
   307.4 2401.02   321.2 2401.31   327.7  2400.6   350.9 2400.47   365.4 2399.63
   379.2 2400.69   382.8 2402.56   385.7 2404.88   403.3 2422.89   407.6 2426.39
   449.4 2456.56   455.2 2460.17   464.5 2464.55   487.1 2478.39   519.6 2496.16
#Mann= 5 ,-1,0
       0      .1       0     160     .12       0   194.2    .045       0
   220.5     .12       0     300      .1       0
#XS Ineff= 2 , 0
                          328.11         2424.42
Permanent Ineff=
       F       F
Bank Sta=194.2,220.5
XS Rating Curve= 0 ,0
Exp/Cntr(USF)=0,0
Exp/Cntr=0.3,0.1

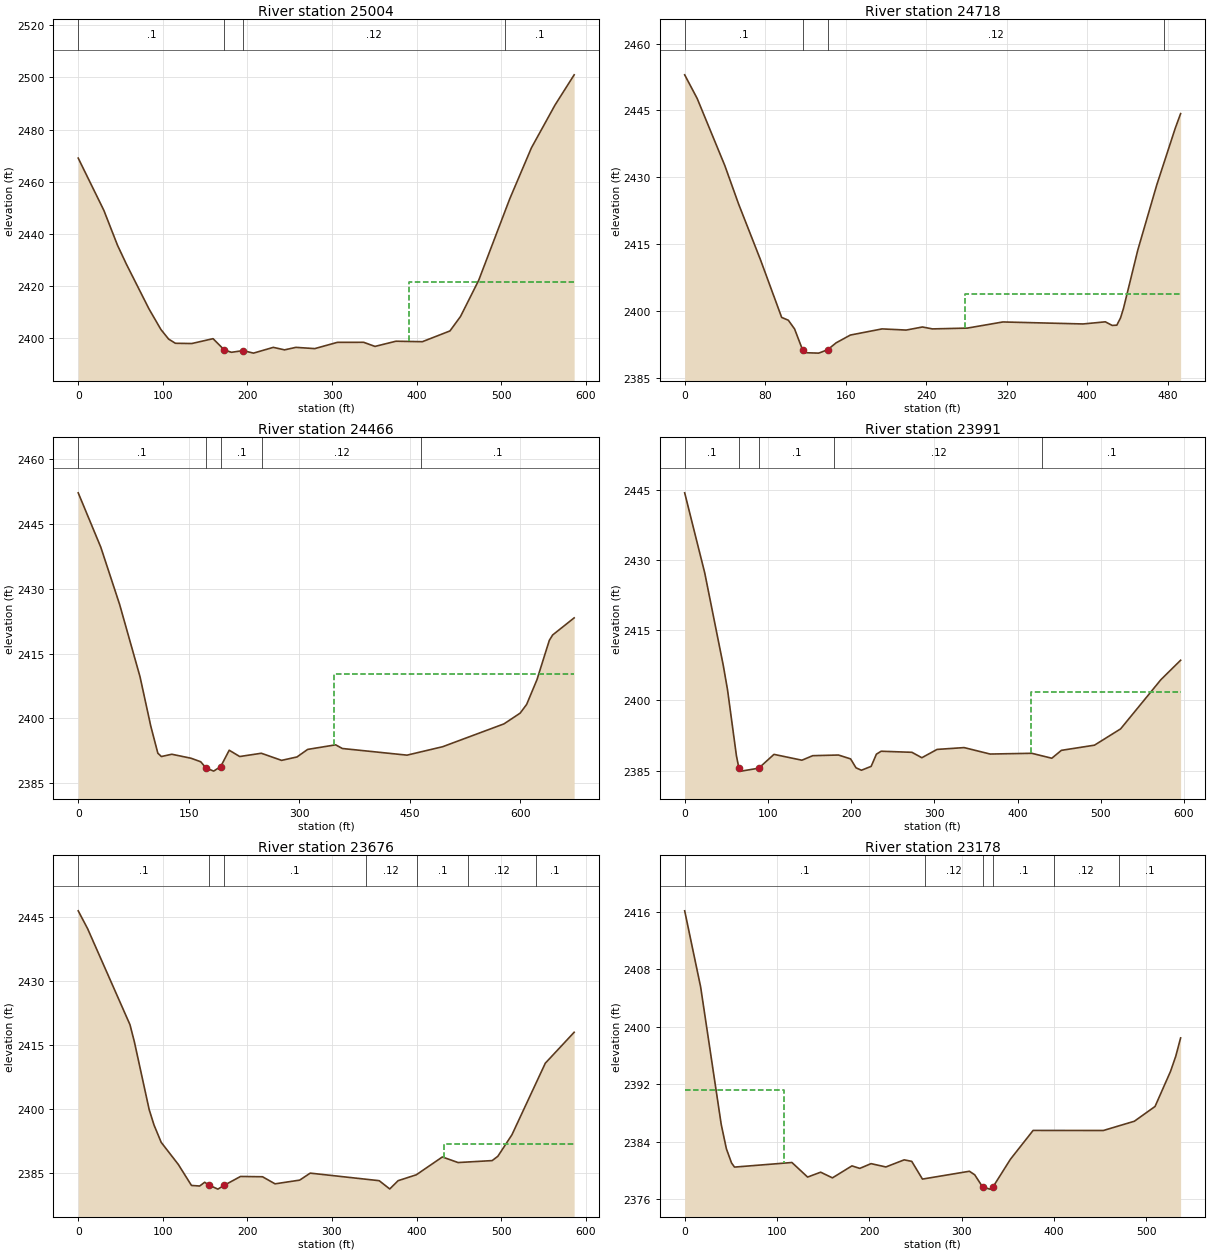
Type RM Length L Ch R = 1 ,25004   ,289.6,286.3,281.9
XS GIS Cut Line= 3
2212113.25104355392081.9695828372212290.82301779392445.650645477
2212410.34261584392582.244471821
#Sta/Elev= 30
       0 2469.05    30.3 2449.05    46.5 2435.62      57 2428.39    83.7 2411.26
    97.8 2403.37   106.9 2399.71   114.9 2398.11   134.3 2398.02   159.4 2399.88
   172.7 2395.54   181.1 2394.66     195  2395.3   207.2 2394.34   230.6 2396.55
   243.9 2395.59   257.3 2396.55   279.6 2396.07   306.3 2398.47   337.4 2398.49
   350.8 2396.91   375.5  2398.9   406.8 2398.72   439.4 2402.84   451.9 2408.39
   473.4 2422.26     510 2453.39   535.7 2472.99   563.5 2489.34   586.2 2500.96
#Mann= 4 ,-1,0
       0      .1       0   172.7    .045       0     195     .12       0
  504.72      .1       0
#XS Ineff= 2 , 0
                          390.78         2421.51
Permanent Ineff=
       F       F
Bank Sta=172.7,195
XS Rating Curve= 0 ,0
Exp/Cntr(USF)=0,0
Exp/Cntr=0.3,0.1

Type RM Length L Ch R = 1 ,24718   ,251.3,252.4,254
XS GIS Cut Line= 3
2211881.40729159392315.7581805332212028.24565491392488.207886292
 2212243.3809314392645.290786587
#Sta/Elev= 30
       0    2453    12.4  2447.7    39.9 2432.62    53.6 2423.98    75.4 2411.43
    96.4 2398.52     103 2397.89   109.2 2395.94   117.4  2391.1   121.5 2390.58
   133.2  2390.5     142 2391.25   150.5 2392.81   164.7 2394.56   196.2 2395.94
   220.2 2395.68   236.3 2396.37   246.2 2395.94   280.9 2396.12   316.3  2397.5
     396 2397.05   418.1 2397.53   424.9 2396.72   429.5 2396.78   433.2 2398.42
   436.1 2400.53   450.4  2413.7   469.1 2428.21   487.6 2441.03   492.9 2444.29
#Mann= 4 ,-1,0
       0      .1       0   117.4    .045       0     142     .12       0
   476.5      .1       0
#XS Ineff= 2 , 0
                          278.35         2403.86
Permanent Ineff=
       F       F
Bank Sta=117.4,142
XS Rating Curve= 0 ,0
Exp/Cntr(USF)=0,0
Exp/Cntr=0.3,0.1

Type RM Length L Ch R = 1 ,24466   ,482.9,474.7,471.7
XS GIS Cut Line= 4
2211676.51655208392431.8629329252211871.16275462392717.002545417
2211848.96625783392872.3780228832211920.67801666393027.753500349
#Sta/Elev= 30
       0 2452.23    30.7 2439.62    56.2 2426.39    83.9 2409.65    98.5 2398.22
   108.1 2391.94   112.9 2391.16   127.1 2391.69   153.3 2390.76   166.3 2389.95
   173.4 2388.53   183.9 2387.78   193.5 2388.85     205 2392.62   219.3 2391.16
   248.6 2391.92   276.1 2390.27     297 2391.06   311.5 2392.81   349.5 2393.87
   358.6 2393.02   446.4 2391.48   494.9 2393.44     578 2398.72     600 2401.21
   608.8 2403.23   622.8 2408.95   639.6 2418.07   644.1 2419.31   673.3 2423.27
#Mann= 5 ,-1,0
       0      .1       0   173.4    .045       0   193.5      .1       0
     250     .12       0  465.24      .1       0
#XS Ineff= 2 , 0
                          347.44         2410.31
Permanent Ineff=
       F       F
Bank Sta=173.4,193.5
XS Rating Curve= 0 ,0
Exp/Cntr(USF)=0,0
Exp/Cntr=0.3,0.1

Type RM Length L Ch R = 1 ,23991   ,313.6,315.3,314.6
XS GIS Cut Line= 2
2211331.61714056 392662.365014882211801.15841861393029.460923179
#Sta/Elev= 30
       0 2444.48    24.1 2427.33    46.4  2407.5    51.5 2402.29    62.2 2388.15
    65.1 2385.59    67.9 2384.87      89  2385.5   107.3 2388.46   140.9 2387.21
   153.9 2388.18   184.8 2388.32   199.4 2387.49   205.9 2385.58   212.4 2385.06
   224.1 2385.89   230.4  2388.5   236.1 2389.13   273.1  2388.9     285 2387.74
   303.3 2389.52   335.8 2389.91   367.1 2388.53   417.1 2388.69   441.2 2387.63
   452.7 2389.32   492.5 2390.43   523.9 2393.92   572.3 2404.46     596 2408.62
#Mann= 5 ,-1,0
       0      .1       0    65.1    .045       0      89      .1       0
     180     .12       0     430      .1       0
#XS Ineff= 2 , 0
                          416.59         2401.92
Permanent Ineff=
       F       F
Bank Sta=65.1,89
XS Rating Curve= 0 ,0
Exp/Cntr(USF)=0,0
Exp/Cntr=0.3,0.1

Type RM Length L Ch R = 1 ,23676   ,495.9,497.5,494.3
XS GIS Cut Line= 3
2211113.06701841392874.0854457132211452.84416144393155.810212547
2211556.99695402393256.548159475
#Sta/Elev= 30
       0 2446.52    11.1 2442.34    61.2 2419.83    66.4 2415.81    83.9 2399.92
    89.6 2396.32    98.1 2392.25   118.4 2387.05   133.9 2382.14   143.6 2382.01
   149.5 2382.89   154.7 2382.22   165.1 2381.28   172.72382.187   191.9 2384.25
   217.9 2384.18   232.7 2382.52   261.8 2383.39   274.3 2385.03   355.8 2383.26
   368.3 2381.32   378.2 2383.26   399.7 2384.64   430.5 2388.82   449.1 2387.51
   489.4 2387.97   496.1 2388.98   512.8 2394.04   552.2  2410.8   586.3 2418.05
#Mann= 7 ,-1,0
       0      .1       0   154.7    .045       0   172.7      .1       0
     340     .12       0     400      .1       0  461.38     .12       0
  541.38      .1       0
#XS Ineff= 2 , 0
                          432.68         2391.77
Permanent Ineff=
       F       F
Bank Sta=154.7,172.7
XS Rating Curve= 0 ,0
Exp/Cntr(USF)=0,0
Exp/Cntr=0.3,0.1

Type RM Length L Ch R = 1 ,23178   ,259.4,260.3,260
XS GIS Cut Line= 2
2210896.22431909393184.8364006452211271.85734153393569.006537236
#Sta/Elev= 30
       0 2416.16    17.3 2405.55    39.6 2386.39    45.2    2383    50.8 2381.02
      54 2380.45   116.2 2381.09   133.2 2379.06   147.3 2379.74   160.1 2378.95
   181.2 2380.62   189.7 2380.27   201.9 2380.93     218 2380.47   237.8 2381.46
     246 2381.25   257.6 2378.78   308.5 2379.87   314.2 2379.38   322.7  2377.7
   330.5 2377.38     334 2377.68   352.9 2381.54   377.5 2385.56   453.6 2385.55
   487.2 2386.84   509.6  2388.9   526.3 2393.77     532 2395.88   537.3 2398.45
#Mann= 6 ,-1,0
       0      .1       0     260     .12       0   322.7    .045       0
     334      .1       0     400     .12       0     470      .1       0
#XS Ineff= 2 , 0
          107.83 2391.18
Permanent Ineff=
       F       F
Bank Sta=322.7,334
XS Rating Curve= 0 ,0
Exp/Cntr(USF)=0,0
Exp/Cntr=0.3,0.1

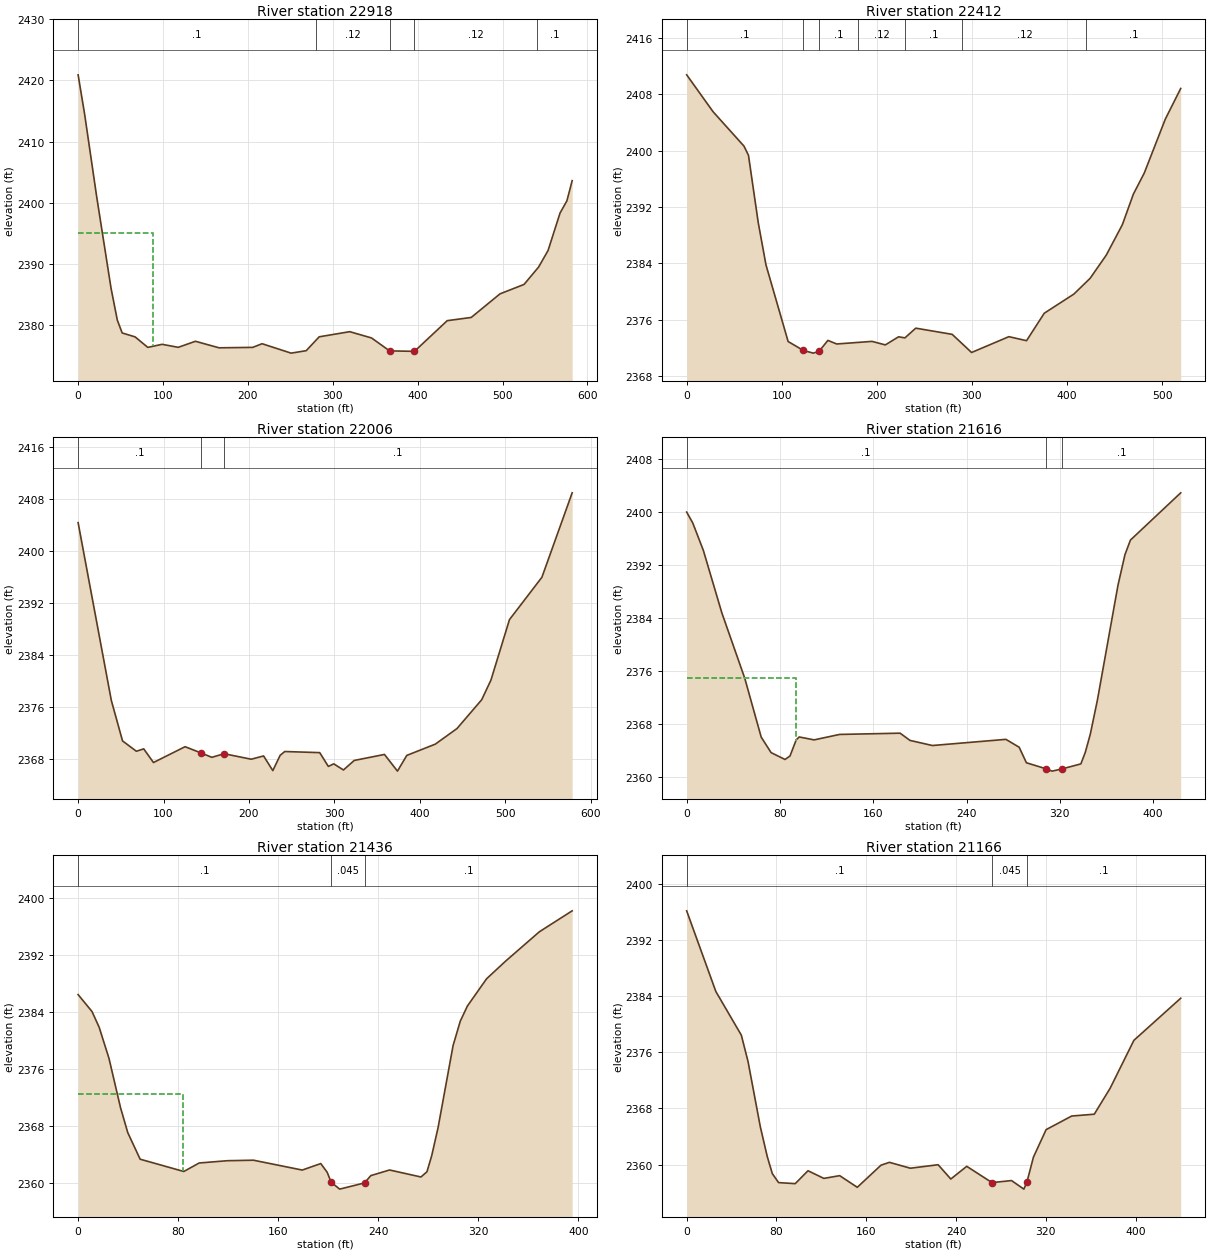
Type RM Length L Ch R = 1 ,22918   ,492.7,505.7,507
XS GIS Cut Line= 2
2210677.67419694393336.7970324522211092.57794446393744.871088654
#Sta/Elev= 30
       0 2420.92     7.7 2414.46    21.8 2401.04    38.8 2385.99    46.2 2380.77
    51.9 2378.68    67.1 2378.04    82.1 2376.32    98.9 2376.82     118 2376.33
   138.2 2377.32     166 2376.25   205.7 2376.32   216.7 2376.92   250.9 2375.38
   268.7 2375.78     284 2378.05     320 2378.89   345.7 2377.86   366.9 2375.75
   396.2 2375.67   434.8 2380.69   463.1 2381.22     497 2385.08   525.3 2386.62
   542.5 2389.47   553.6 2392.17   567.7  2398.3   575.8  2400.3     582  2403.6
#Mann= 5 ,-1,0
       0      .1       0     280     .12       0   366.9    .045       0
   396.2     .12       0     540      .1       0
#XS Ineff= 2 , 0
           88.48 2394.97
Permanent Ineff=
       F       F
Bank Sta=366.9,396.2
XS Rating Curve= 0 ,0
Exp/Cntr(USF)=0,0
Exp/Cntr=0.3,0.1

Type RM Length L Ch R = 1 ,22412   ,407,406.4,404.4
XS GIS Cut Line= 3
 2210465.9537661393661.207370018 2210664.0148143 393997.56966739
2210756.21564709394088.063077342
#Sta/Elev= 30
       0 2410.79    27.8 2405.54    60.3 2400.65      65 2399.35    75.3 2389.75
    83.4 2383.77   106.7 2372.87   122.6 2371.61   133.1 2371.22   139.2 2371.47
   148.5 2373.03   157.8 2372.52   194.9 2372.89   208.9 2372.39   222.8 2373.54
   229.5 2373.39   240.9 2374.77   279.2 2373.89   299.6 2371.31   338.8 2373.56
   357.4 2372.99     376 2376.89   407.2 2379.62   424.2 2381.85   441.2 2385.15
   458.1 2389.47   469.7 2393.82   481.2 2396.83   503.3 2404.49   519.5 2408.85
#Mann= 7 ,-1,0
       0      .1       0   122.6    .045       0   139.2      .1       0
     180     .12       0     230      .1       0     290     .12       0
  420.34      .1       0
Bank Sta=122.6,139.2
XS Rating Curve= 0 ,0
Exp/Cntr(USF)=0,0
Exp/Cntr=0.3,0.1

Type RM Length L Ch R = 1 ,22006   ,390,390.1,378.5
XS GIS Cut Line= 3
2210148.37311986393917.3207944132210402.77912142394246.853400467
2210522.29871947394356.128461542
#Sta/Elev= 30
       0 2404.34    38.9 2377.03      52 2370.83    68.2 2369.24    76.8 2369.61
    88.2 2367.51   125.2 2369.94   143.7 2368.99   156.5 2368.31   170.9 2368.86
   202.6 2368.02   217.1 2368.52   227.9 2366.27   236.5 2368.62   241.9  2369.2
   282.8 2369.03   292.9 2366.91   299.2 2367.31   310.6 2366.37   323.2 2367.83
   358.6 2368.75   373.8 2366.19   384.7  2368.6   418.2 2370.34   443.5 2372.73
   472.4 2377.15   483.2 2380.16   504.9 2389.45   542.9 2395.96   578.3 2408.92
#Mann= 3 ,-1,0
       0      .1       0   143.7    .045       0   170.9      .1       0
Bank Sta=143.7,170.9
XS Rating Curve= 0 ,0
Exp/Cntr(USF)=0,0
Exp/Cntr=0.3,0.1

Type RM Length L Ch R = 1 ,21616   ,179.6,179.3,178.6
XS GIS Cut Line= 2
2209928.76496307394158.3802742782210207.07488425394477.668343356
#Sta/Elev= 30
       0 2399.96     5.2 2398.33    14.3 2394.19    30.2 2384.75    49.8 2374.92
    63.9 2366.04    72.4  2363.7    84.3 2362.67    88.6 2363.19    93.9 2365.61
    96.5 2366.06   109.3 2365.62   131.1 2366.44     183 2366.63   191.5 2365.54
   210.7 2364.77   273.7  2365.7   285.1 2364.51   291.3 2362.17   307.8 2361.28
   313.4 2360.91   321.7 2361.24     338    2362   341.8 2363.75   346.1 2366.49
   352.2 2371.64   369.8 2388.92   375.8 2393.54   380.5 2395.74   423.6 2402.86
#Mann= 3 ,-1,0
       0      .1       0   307.8    .045       0   321.7      .1       0
#XS Ineff= 2 , 0
            93.7 2375.01
Permanent Ineff=
       F       F
Bank Sta=307.8,321.7
XS Rating Curve= 0 ,0
Exp/Cntr(USF)=0,0
Exp/Cntr=0.3,0.1

Type RM Length L Ch R = 1 ,21436   ,273.7,270.4,268.4
XS GIS Cut Line= 3
  2209844.511464394297.3735670892210036.75020035394555.996903042
2210093.45371251394601.636315269
#Sta/Elev= 30
       0 2386.41    11.1 2384.04    16.8 2381.85    24.7 2377.47    33.9 2370.58
    39.7 2367.08    49.6 2363.36    84.5 2361.64    96.8 2362.83   119.4 2363.15
   140.2 2363.22   179.2 2361.84     194 2362.75   199.1 2361.54   202.32360.146
   209.1 2359.17     229 2360.04     234 2361.06     249 2361.85   274.1 2360.87
   278.9  2361.6   282.7 2363.85   287.8 2367.79   299.8 2379.28   305.5 2382.67
   311.2  2384.8   326.6 2388.63     342 2391.13   368.8 2395.21     395 2398.14
#Mann= 3 ,-1,0
       0      .1       0   202.3    .045       0     229      .1       0
#XS Ineff= 2 , 0
           83.56 2372.47
Permanent Ineff=
       F       F
Bank Sta=202.3,229
XS Rating Curve= 0 ,0
Exp/Cntr(USF)=0,0
Exp/Cntr=0.3,0.1

Type RM Length L Ch R = 1 ,21166   ,339.6,341.5,342.2
XS GIS Cut Line= 3
2209613.54837788394490.9953159312209847.27748898394719.192377066
2209937.17330095394788.343001653
#Sta/Elev= 30
       0 2396.16      26 2384.66    48.7 2378.44    54.7 2374.66    65.6 2365.39
    71.8 2361.13    76.3  2358.7    81.9 2357.42    96.7 2357.27   108.1 2359.11
   122.2 2358.02   136.3 2358.41     152 2356.75   173.1  2359.9   180.6 2360.31
   199.3 2359.47     224 2359.97   235.3 2357.93   249.5 2359.74     272 2357.42
   289.4 2357.71   300.4 2356.49   303.2 2357.55   308.9 2361.05   320.2 2364.97
     343 2366.91   363.1 2367.17   377.2 2370.86   398.4  2377.7   440.1  2383.7
#Mann= 3 ,-1,0
       0      .1       0     272    .045       0   303.2      .1       0
Bank Sta=272,303.2
XS Rating Curve= 0 ,0
Exp/Cntr(USF)=0,0
Exp/Cntr=0.3,0.1

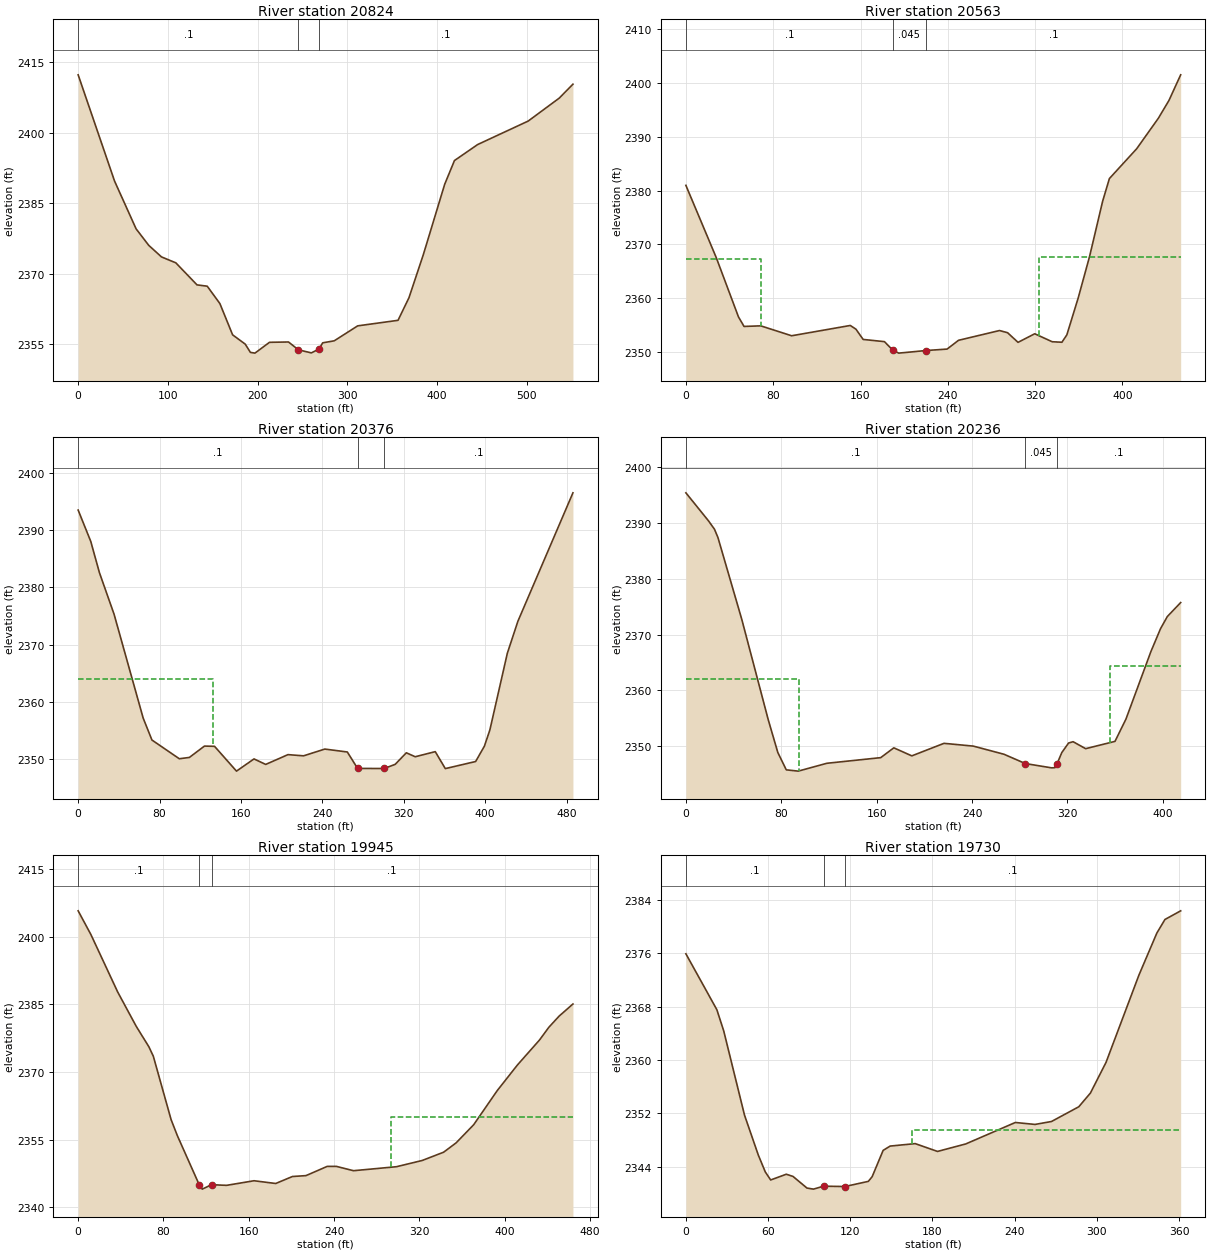
Type RM Length L Ch R = 1 ,20824   ,262.6,261.9,258.1
XS GIS Cut Line= 3
 2209359.0740794394679.0850148062209570.67499064394912.814125908
 2209660.5708026395131.330099602
#Sta/Elev= 30
       0  2412.3    40.6 2389.69    64.6 2379.53    78.7 2376.02    92.9 2373.56
   108.9  2372.3   132.5 2367.61   143.9 2367.33     158 2363.64   172.2 2356.98
   186.3    2355     192 2353.25   197.1 2353.09   213.3 2355.39   234.5 2355.46
   245.62353.789     260 2353.14   268.5 2353.96   272.6 2355.28   285.5 2355.71
   311.6 2358.89   356.6 2360.07   368.8 2364.88   384.9  2374.1   408.6    2389
   419.5 2394.06   445.4 2397.47   501.7 2402.46   536.3 2407.34   551.6 2410.31
#Mann= 3 ,-1,0
       0      .1       0   245.6    .045       0   268.5      .1       0
Bank Sta=245.6,268.5
XS Rating Curve= 0 ,0
Exp/Cntr(USF)=0,0
Exp/Cntr=0.3,0.1

Type RM Length L Ch R = 1 ,20563   ,179.7,186.3,189.7
XS GIS Cut Line= 4
 2209197.8202204394871.4042937072209287.43942987 394984.67301678
2209495.30620738395158.932590738 2209516.4662985395190.050371802
#Sta/Elev= 30
       0 2380.96    27.8 2367.57    48.2 2356.55    53.3 2354.79    68.6  2354.9
    96.9 2353.06   150.6 2354.97   155.8 2354.28   162.4 2352.38   181.9 2351.97
  189.67 2350.37     195 2349.84   219.9 2350.32   239.3 2350.59   249.8 2352.22
   287.3 2354.03   294.7 2353.63   304.3 2351.84   319.6 2353.43   335.6 2351.95
   344.5 2351.86     349 2353.22   359.4 2360.06   369.8 2367.74   381.8 2378.01
     388 2382.22     413 2387.75   432.9 2393.42   442.6 2396.72   453.3 2401.46
#Mann= 3 ,-1,0
       0      .1       0  189.67    .045       0   219.9      .1       0
#XS Ineff= 2 , 0
           68.36 2367.33  323.35         2367.59
Permanent Ineff=
       F       F
Bank Sta=189.67,219.9
XS Rating Curve= 0 ,0
Exp/Cntr(USF)=0,0
Exp/Cntr=0.3,0.1

Type RM Length L Ch R = 1 ,20376   ,140,139.8,138.9
XS GIS Cut Line= 3
2209047.60760178394932.5058088372209290.83345468395269.954289428
2209348.90088802395309.396319627
#Sta/Elev= 30
       0  2393.5    12.4 2388.03    20.9 2382.58    35.3 2375.32    63.9 2357.19
    72.5 2353.37    99.4  2350.1   109.3 2350.33   124.1 2352.31     134 2352.27
   155.6 2347.94   172.8 2350.07   184.3 2349.11   206.2 2350.82   221.5 2350.61
   242.4 2351.79   264.5 2351.28   274.6 2348.41   300.7  2348.4   311.5 2349.12
   322.5 2351.14   331.2 2350.45   350.9 2351.34   360.8 2348.38   390.6 2349.62
   399.2  2352.3   404.6 2355.14   421.7 2368.49   432.1 2374.09   486.2 2396.51
#Mann= 3 ,-1,0
       0      .1       0   274.6    .045       0   300.7      .1       0
#XS Ineff= 2 , 0
          132.87 2364.09
Permanent Ineff=
       F       F
Bank Sta=274.6,300.7
XS Rating Curve= 0 ,0
Exp/Cntr(USF)=0,0
Exp/Cntr=0.3,0.1

Type RM Length L Ch R = 1 ,20236   ,277.3,291.4,296.6
XS GIS Cut Line= 2
2208937.67557071395022.0143540562209187.86253046395353.107544577
#Sta/Elev= 30
       0 2395.45      19 2390.41      24 2388.91    26.9 2387.42    46.9 2372.72
    69.1  2354.7    77.1 2348.84    84.2 2345.72    94.2 2345.49   118.3  2346.9
   163.4 2347.91   174.4 2349.67   189.5 2348.23   216.5 2350.48   241.1 2349.98
   266.8 2348.52   284.7 2346.85   306.7 2346.08   309.6 2346.11   311.2 2346.75
   315.3 2348.82     321 2350.54   324.8 2350.77   335.3 2349.52   359.9 2350.83
   369.1 2354.83     390 2366.94   398.1 2371.06   403.8 2373.24     415 2375.75
#Mann= 3 ,-1,0
       0      .1       0   284.7    .045       0   311.2      .1       0
#XS Ineff= 2 , 0
           95.24 2361.99  355.61         2364.42
Permanent Ineff=
       F       F
Bank Sta=284.7,311.2
XS Rating Curve= 0 ,0
Exp/Cntr(USF)=0,0
Exp/Cntr=0.3,0.1

Type RM Length L Ch R = 1 ,19945   ,223.1,215,206.8
XS GIS Cut Line= 5
2208843.82377909395037.6845560342208881.07458539395161.488706381
2208952.28936213395249.1376623792208965.43670553395376.228648576
2209004.87873573395461.686380673
#Sta/Elev= 30
       0 2405.79      12  2400.5    37.1 2387.76    54.5 2380.13    66.3 2375.62
    70.5 2373.51    87.2 2359.41      93 2355.89  113.49    2345   116.4 2343.99
   125.1 2344.97   139.2 2344.83     165 2345.85   185.3 2345.24     201 2346.79
   213.7 2346.99   233.6 2349.04   242.2 2349.04   258.3 2348.08   298.6 2348.97
   322.7 2350.35   342.8 2352.19   354.5 2354.26     371 2358.29   393.1 2365.87
     412 2371.55   432.7 2377.09   441.5 2379.93   451.1  2382.4   464.1  2385.1
#Mann= 3 ,-1,0
       0      .1       0  113.49    .045       0   125.1      .1       0
#XS Ineff= 2 , 0
                          293.39         2360.11
Permanent Ineff=
       F       F
Bank Sta=113.49,125.1
XS Rating Curve= 0 ,0
Exp/Cntr(USF)=0,0
Exp/Cntr=0.3,0.1

Type RM Length L Ch R = 1 ,19730   ,176.1,179,178.8
XS GIS Cut Line= 3
2208670.33385852395228.1409740232208793.42197029395323.568835952
2208923.42514451395482.615272501
#Sta/Elev= 30
       0 2375.89    22.6 2367.53    27.6 2364.37    42.8 2351.75    52.9 2345.76
      58 2343.24    61.9 2342.05    73.3 2342.91    78.2 2342.58    88.4 2340.84
    93.1 2340.68   100.52341.118   116.1 2341.07   133.2 2341.84     136 2342.55
     144 2346.48   149.1 2347.12   167.4 2347.49   183.7 2346.32   204.3 2347.44
   240.5 2350.65   254.9 2350.36   266.9  2350.8   286.8    2353   295.3 2355.05
   306.7 2359.64   330.7 2372.69   343.8 2378.99   349.7 2381.02   361.2 2382.32
#Mann= 3 ,-1,0
       0      .1       0   100.5    .045       0   116.1      .1       0
#XS Ineff= 2 , 0
                          164.73         2349.55
Permanent Ineff=
       F       F
Bank Sta=100.5,116.1
XS Rating Curve= 0 ,0
Exp/Cntr(USF)=0,0
Exp/Cntr=0.3,0.1

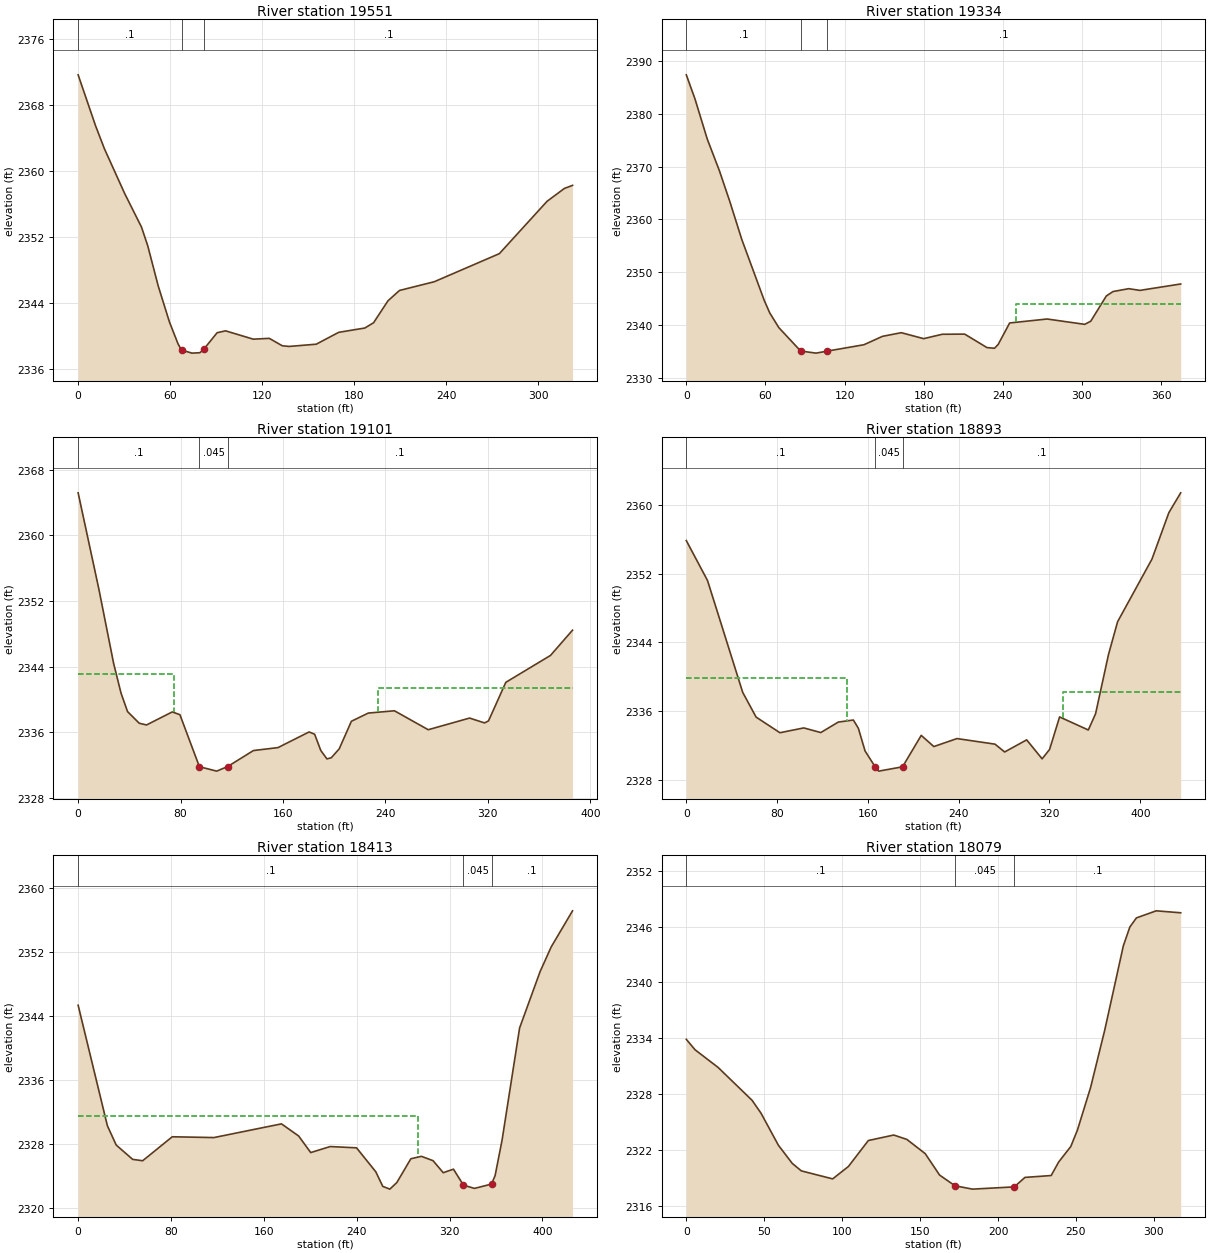
Type RM Length L Ch R = 1 ,19551   ,216.2,216.7,216.8
XS GIS Cut Line= 3
2208558.03864173395343.1498546362208713.62754705395488.781070016
2208792.04435533395564.708455812
#Sta/Elev= 30
       0 2371.63    11.4 2365.44    17.1 2362.69    30.3 2357.27    41.3 2353.19
    45.4 2350.91    52.2 2346.06    59.5 2341.71    65.2 2339.01    67.4  2338.3
    74.2 2337.92    79.4 2337.97    82.2 2338.46    90.6 2340.39    96.1 2340.62
   114.2 2339.61   124.6 2339.71   133.1 2338.81   137.6 2338.73   155.2    2339
   169.9 2340.44   186.9 2340.96   192.6  2341.6     202 2344.26   209.5 2345.51
   232.2 2346.57   274.6 2349.97   305.7 2356.31     317 2357.87   322.3 2358.24
#Mann= 3 ,-1,0
       0      .1       0    67.4    .045       0    82.2      .1       0
Bank Sta=67.4,82.2
XS Rating Curve= 0 ,0
Exp/Cntr(USF)=0,0
Exp/Cntr=0.3,0.1

Type RM Length L Ch R = 1 ,19334   ,236.7,233.4,230.2
XS GIS Cut Line= 2
2208386.26849026395472.5998238622208652.63669616395736.478607285
#Sta/Elev= 30
       0 2387.37     6.5 2382.87    15.9 2375.21    25.2 2369.14    32.9 2363.46
    42.1 2356.19      59 2344.73    63.3 2342.28    70.2  2339.5    86.72335.081
    98.4 2334.68   106.4 2335.04   134.7 2336.27   148.8 2337.86     163 2338.55
     180 2337.42   194.1 2338.25   211.1 2338.28     228 2335.73   233.7  2335.6
   236.5 2336.32   245.2 2340.39   273.6 2341.14   302.1 2340.13   306.7 2340.72
   318.5  2345.5   323.6 2346.34   335.5 2346.88     344 2346.56   374.9 2347.77
#Mann= 3 ,-1,0
       0      .1       0    86.7    .045       0   106.4      .1       0
#XS Ineff= 2 , 0
                          249.69         2343.95
Permanent Ineff=
       F       F
Bank Sta=86.7,106.4
XS Rating Curve= 0 ,0
Exp/Cntr(USF)=0,0
Exp/Cntr=0.3,0.1

Type RM Length L Ch R = 1 ,19101   ,209.6,207.7,205
XS GIS Cut Line= 4
2208215.74305003395630.6781516672208254.32909855395680.466601369
2208398.71560268395775.0646558042208529.41028315395849.747330357
#Sta/Elev= 30
       0 2365.19    16.3 2353.37    27.7  2344.4    33.5 2340.76    38.6 2338.51
    47.7 2337.09    53.4 2336.88    73.5 2338.47    79.5 2338.13    94.7 2331.79
   108.2 2331.25   116.8 2331.81   136.9 2333.76   156.1 2334.12   180.4 2336.03
   184.7 2335.75   189.5 2333.77   194.3 2332.74   197.7 2332.88   203.9 2333.97
   213.4 2337.33   226.6 2338.33     247 2338.61   273.4  2336.3   305.7 2337.72
   317.4 2337.13   320.5 2337.38     334 2342.08   368.9 2345.36   386.1 2348.44
#Mann= 3 ,-1,0
       0      .1       0    94.7    .045       0   116.8      .1       0
#XS Ineff= 2 , 0
           74.59  2343.1  234.37         2341.35
Permanent Ineff=
       F       F
Bank Sta=94.7,116.8
XS Rating Curve= 0 ,0
Exp/Cntr(USF)=0,0
Exp/Cntr=0.3,0.1

Type RM Length L Ch R = 1 ,18893   ,469.4,480.2,493.2
XS GIS Cut Line= 3
2208015.34453998395799.958880655 2208320.2987944395945.590096034
2208388.75791274396015.293925617
#Sta/Elev= 30
       0 2355.85    18.7  2351.2    49.7 2338.18    61.5  2335.3    82.5 2333.48
   103.5 2334.04   118.5  2333.5   133.9 2334.72   147.2 2334.96   151.6    2334
   157.5 2331.36   166.5 2329.49   169.5 2329.01   190.5 2329.51     207 2333.17
   218.1 2331.87   238.5  2332.8     272 2332.15   280.5 2331.24   299.9 2332.65
   313.5 2330.44   320.1 2331.54   328.9 2335.32   354.2  2333.8   360.6 2335.69
     372 2342.59     380  2346.4   410.3  2353.7   425.2 2359.11   435.6 2361.41
#Mann= 3 ,-1,0
       0      .1       0   166.5    .045       0   190.5      .1       0
#XS Ineff= 2 , 0
          141.97 2339.85  331.55         2338.19
Permanent Ineff=
       F       F
Bank Sta=166.5,190.5
XS Rating Curve= 0 ,0
Exp/Cntr(USF)=0,0
Exp/Cntr=0.3,0.1

Type RM Length L Ch R = 1 ,18413   ,333.8,334.2,336.2
XS GIS Cut Line= 3
2207777.86350903395993.4314433942207889.58191936396134.549435385
 2207991.0104761396358.721245578
#Sta/Elev= 30
       0 2345.35    25.2 2330.32    32.8 2327.91      47 2326.12    55.6 2325.95
    81.1 2328.94     117 2328.84   175.2 2330.55     190 2329.04   200.4 2326.97
   217.2 2327.72   239.9 2327.56   256.5 2324.57   262.5 2322.75   268.6 2322.41
   274.6 2323.23   286.7  2326.2   295.8  2326.5   305.8 2325.96   314.6 2324.46
   323.4  2324.9     332 2322.91   341.5  2322.5   356.2 2323.04   359.3  2324.1
   365.3 2328.53   380.4 2342.51     398 2349.52   407.6 2352.61     426 2357.12
#Mann= 3 ,-1,0
       0      .1       0     332    .045       0   356.2      .1       0
#XS Ineff= 2 , 0
          293.24 2331.57
Permanent Ineff=
       F       F
Bank Sta=332,356.2
XS Rating Curve= 0 ,0
Exp/Cntr(USF)=0,0
Exp/Cntr=0.3,0.1

Type RM Length L Ch R = 1 ,18079   ,332.9,308.4,284.8
XS GIS Cut Line= 3
2207537.84257069396196.5857054132207613.90825773396303.077667276
2207671.99478239396480.103266218
#Sta/Elev= 30
       0 2333.89     5.6 2332.77    20.4 2330.87    42.2 2327.34      48 2325.94
    59.1 2322.51      68 2320.56    73.8 2319.76    93.9  2318.9     104 2320.23
   116.8 2323.02   133.1 2323.61   141.5 2323.14   153.3 2321.61   162.5 2319.31
   172.4 2318.16   183.6  2317.8   210.4 2318.04   217.3 2319.06   234.1 2319.26
   238.9 2320.71   246.7 2322.38     251 2324.17   259.4 2328.72   268.5  2334.9
   280.4 2343.93   284.6 2345.96   288.8 2346.93   301.5 2347.69   317.2 2347.48
#Mann= 3 ,-1,0
       0      .1       0   172.4    .045       0   210.4      .1       0
Bank Sta=172.4,210.4
XS Rating Curve= 0 ,0
Exp/Cntr(USF)=0,0
Exp/Cntr=0.3,0.1