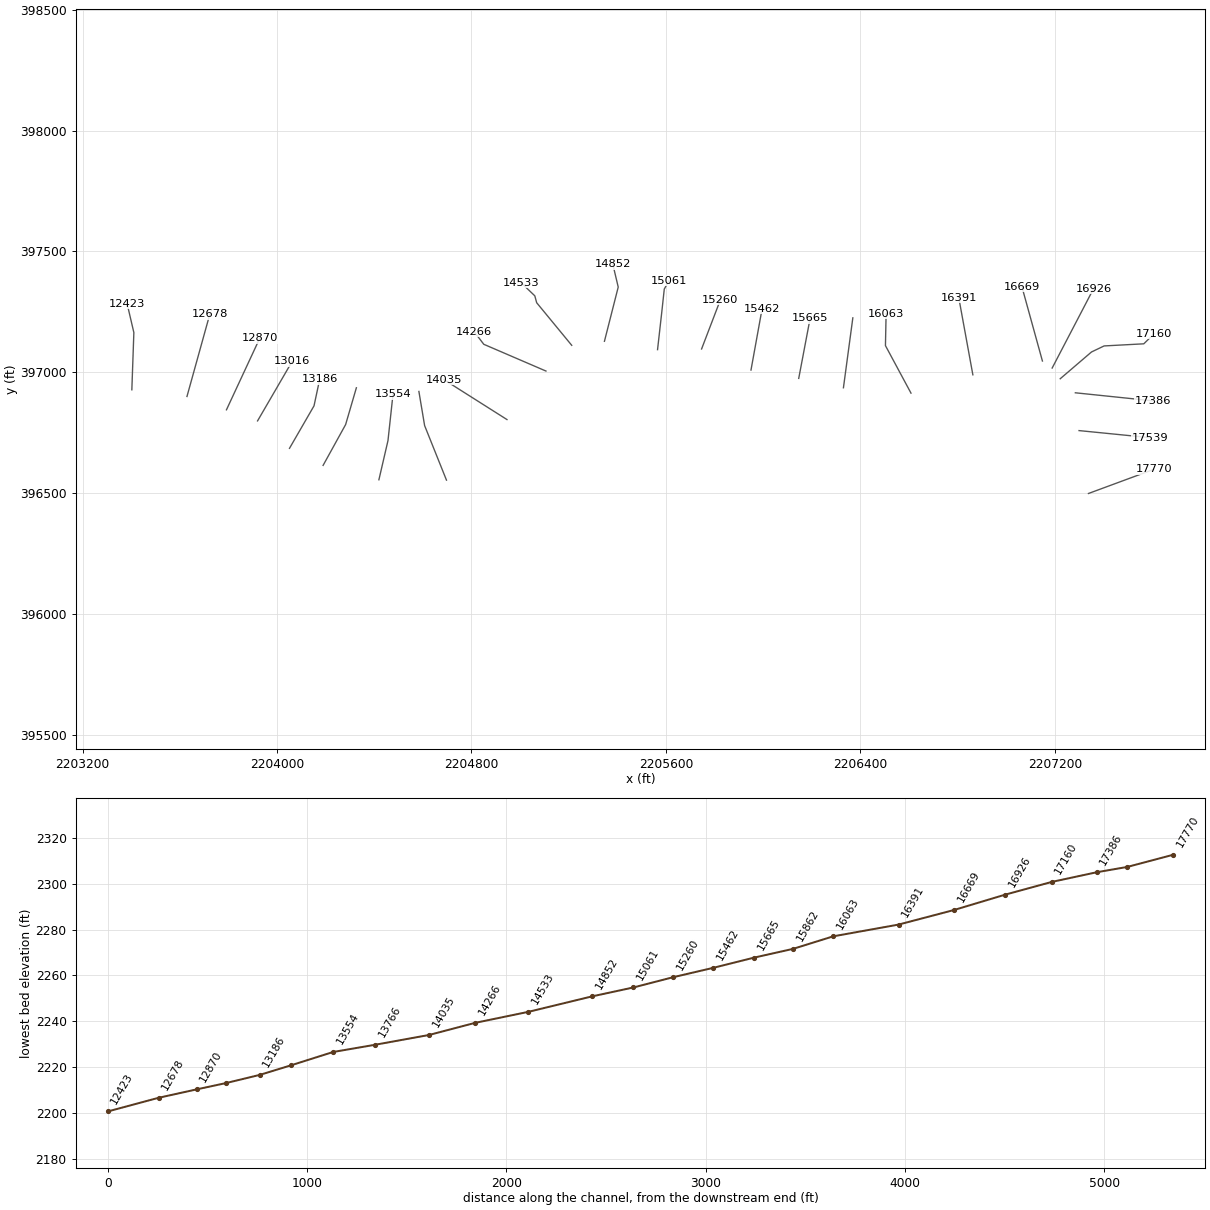
HEC-RAS study LAURELRN1.prj: LAURELRN1

--- LAURELRN1.g01 (geometry) --- (continued)

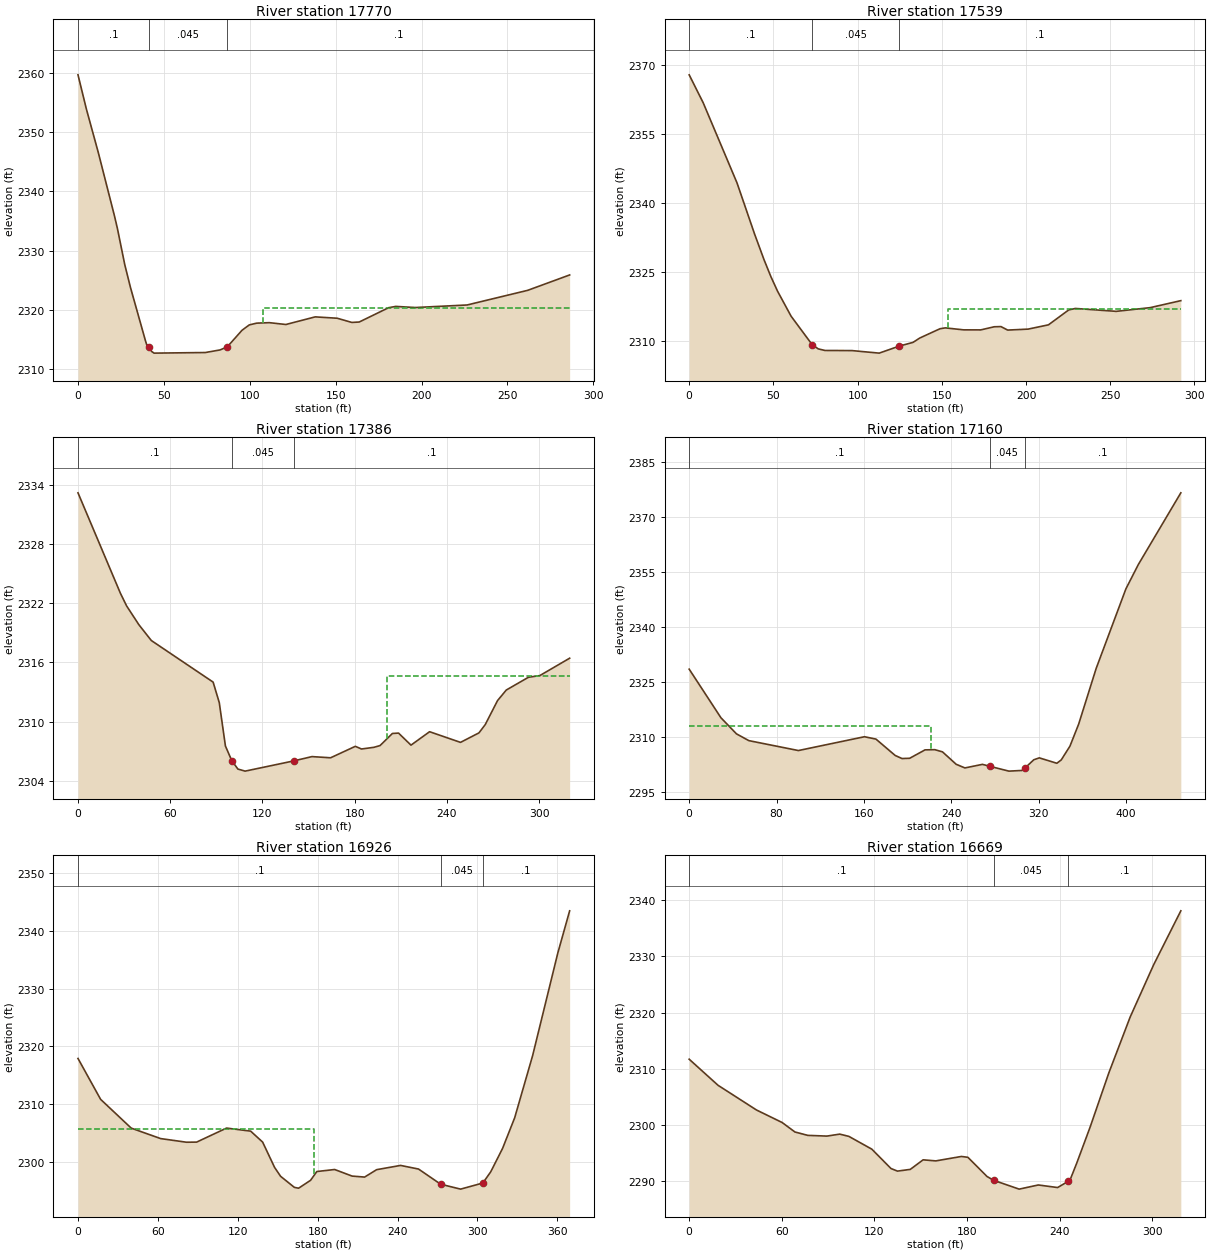
Type RM Length L Ch R = 1 ,17770   ,243.5,231.3,217.3
XS GIS Cut Line= 2
2207338.68877188396499.4654411022207606.99319527396599.042340506
#Sta/Elev= 30
       0 2359.71     4.9  2353.9    11.8 2346.59    21.2 2335.89    22.9 2333.79
    27.2 2327.65    30.5  2323.8    39.4 2314.61      40 2314.07   41.11 2313.68
    42.9 2312.92    44.3 2312.65    74.1 2312.75    82.7 2313.19    86.9 2313.71
    95.5 2316.52    99.7 2317.42     104 2317.72   111.4  2317.8     121 2317.49
   138.1 2318.78   150.9 2318.55   159.4 2317.84   163.7 2317.91   180.8 2320.33
     185 2320.55   196.4 2320.36   226.5 2320.79   261.8 2323.27   286.2 2325.87
#Mann= 3 ,-1,0
       0      .1       0   41.11    .045       0    86.9      .1       0
#XS Ineff= 2 , 0
                          107.83         2320.26
Permanent Ineff=
       F       F
Bank Sta=41.11,86.9
XS Rating Curve= 0 ,0
Exp/Cntr(USF)=0,0
Exp/Cntr=0.3,0.1

Type RM Length L Ch R = 1 ,17539   ,153.7,153.6,154.3
XS GIS Cut Line= 2
2207299.96442211396759.4717895472207590.39704537396730.428527221
#Sta/Elev= 30
       0 2367.94     8.3 2361.87    28.4  2344.4    38.8 2333.29    44.4 2327.71
    48.5 2323.99    52.5 2320.79    60.5 2315.37      732309.172    76.6 2308.25
    80.6  2307.9    96.7 2307.87   112.8 2307.32   124.8 2308.86   132.9 2309.66
   136.9 2310.61   148.9 2312.63   152.1 2312.82   162.9 2312.39   173.1 2312.38
   181.1 2313.06   185.1  2313.1   189.1 2312.34   201.2 2312.55   213.3 2313.48
   225.3 2316.72   229.3 2317.05   253.5 2316.42   273.6 2317.22   291.9 2318.75
#Mann= 3 ,-1,0
       0      .1       0      73    .045       0   124.8      .1       0
#XS Ineff= 2 , 0
                          153.46         2316.89
Permanent Ineff=
       F       F
Bank Sta=73,124.8
XS Rating Curve= 0 ,0
Exp/Cntr(USF)=0,0
Exp/Cntr=0.3,0.1

Type RM Length L Ch R = 1 ,17386   ,220,225.5,225.9
XS GIS Cut Line= 2
 2207284.7512847396915.752201113 2207602.8441578396882.559901311
#Sta/Elev= 30
       0 2333.17    27.6    2323    31.6 2321.73    39.6 2319.82    47.7 2318.22
    87.9 2314.01    91.9 2311.93    95.9 2307.54     100 2306.07     104 2305.21
   108.7    2305   140.2 2306.03   152.2 2306.47   164.3 2306.35   180.4 2307.51
   184.4 2307.24   192.5 2307.41   196.5 2307.59   204.5 2308.81   208.5 2308.85
   216.6 2307.63   228.7 2308.99   248.8 2307.91   260.8 2308.87   264.9 2309.71
   272.9 2312.14   278.6 2313.21     293  2314.5   300.4 2314.67   319.8 2316.43
#Mann= 3 ,-1,0
       0      .1       0     100    .045       0   140.2      .1       0
#XS Ineff= 2 , 0
                          200.73          2314.6
Permanent Ineff=
       F       F
Bank Sta=100,140.2
XS Rating Curve= 0 ,0
Exp/Cntr(USF)=0,0
Exp/Cntr=0.3,0.1

Type RM Length L Ch R = 1 ,17160   ,206.3,233.8,252.6
XS GIS Cut Line= 5
2207222.51572257396973.838725765 2207351.1358843397084.479725104
2207403.09406487397109.4867534312207566.34024542397118.251649031
2207608.60961809397159.827731719
#Sta/Elev= 30
       0 2328.52    29.1 2315.29    43.3 2310.92    54.6 2309.08     100 2306.38
   160.5 2310.14     171 2309.49   188.6 2305.04   194.9  2304.2   201.9 2304.28
   215.9 2306.56   224.9 2306.62   231.9 2306.02   244.4 2302.65   252.4 2301.65
   268.5 2302.62 275.0222302.109   292.7 2300.78   304.5 2300.96 307.6262301.688
   315.5 2303.87   320.5 2304.39   336.6 2302.92   340.6 2303.82   348.6 2307.58
   356.6  2313.6   372.6 2328.73   399.8 2350.36   411.1 2356.94   450.1  2376.5
#Mann= 3 ,-1,0
       0      .1       0 275.022    .045       0 307.626      .1       0
#XS Ineff= 2 , 0
          221.13 2313.07
Permanent Ineff=
       F       F
Bank Sta=275.022,307.626
XS Rating Curve= 0 ,0
Exp/Cntr(USF)=0,0
Exp/Cntr=0.3,0.1

Type RM Length L Ch R = 1 ,16926   ,237.1,256.8,268.8
XS GIS Cut Line= 2
2207189.32342277397018.0951255012207359.43395925397345.869086041
#Sta/Elev= 30
       0 2317.88      17 2310.79      40  2305.8    62.1 2303.99    81.5 2303.36
    89.1 2303.38   111.6 2305.81   129.7 2305.28   138.7 2303.38   147.7 2298.98
   152.2 2297.45   162.5 2295.54   165.7 2295.39   174.7 2296.76   179.4 2298.28
   192.8 2298.63   205.9 2297.49   215.3 2297.32   224.3  2298.6   242.3 2299.34
   255.8 2298.71   272.42296.085   287.4 2295.23   304.1 2296.29     310 2298.22
   318.9 2302.28     328 2307.59   341.5 2318.38   360.4 2336.15   369.3 2343.47
#Mann= 3 ,-1,0
       0      .1       0   272.4    .045       0   304.1      .1       0
#XS Ineff= 2 , 0
          177.57 2305.69
Permanent Ineff=
       F       F
Bank Sta=272.4,304.1
XS Rating Curve= 0 ,0
Exp/Cntr(USF)=0,0
Exp/Cntr=0.3,0.1

Type RM Length L Ch R = 1 ,16669   ,279.6,278.4,273.5
XS GIS Cut Line= 2
2207149.21606051397047.1383878272207064.85229852397354.167160991
#Sta/Elev= 30
       0 2311.68    18.7 2307.03    43.6 2302.63    60.2  2300.4    68.5 2298.71
    76.8 2298.11    89.2 2297.98    97.5 2298.33   103.4 2297.93   118.3 2295.65
   130.7  2292.2   134.9 2291.74   143.2 2292.05   151.5 2293.75   159.7 2293.56
   176.3 2294.35   180.5  2294.2   192.9 2290.78   197.1 2290.11   213.7 2288.53
   226.1 2289.27   238.6 2288.81   245.5 2289.93   246.9 2290.33     251 2293.17
   259.6 2299.54   271.8 2309.26   285.6  2319.2   300.8 2328.51   318.4 2338.12
#Mann= 3 ,-1,0
       0      .1       0   197.1    .045       0   245.5      .1       0
Bank Sta=197.1,245.5
XS Rating Curve= 0 ,0
Exp/Cntr(USF)=0,0
Exp/Cntr=0.3,0.1

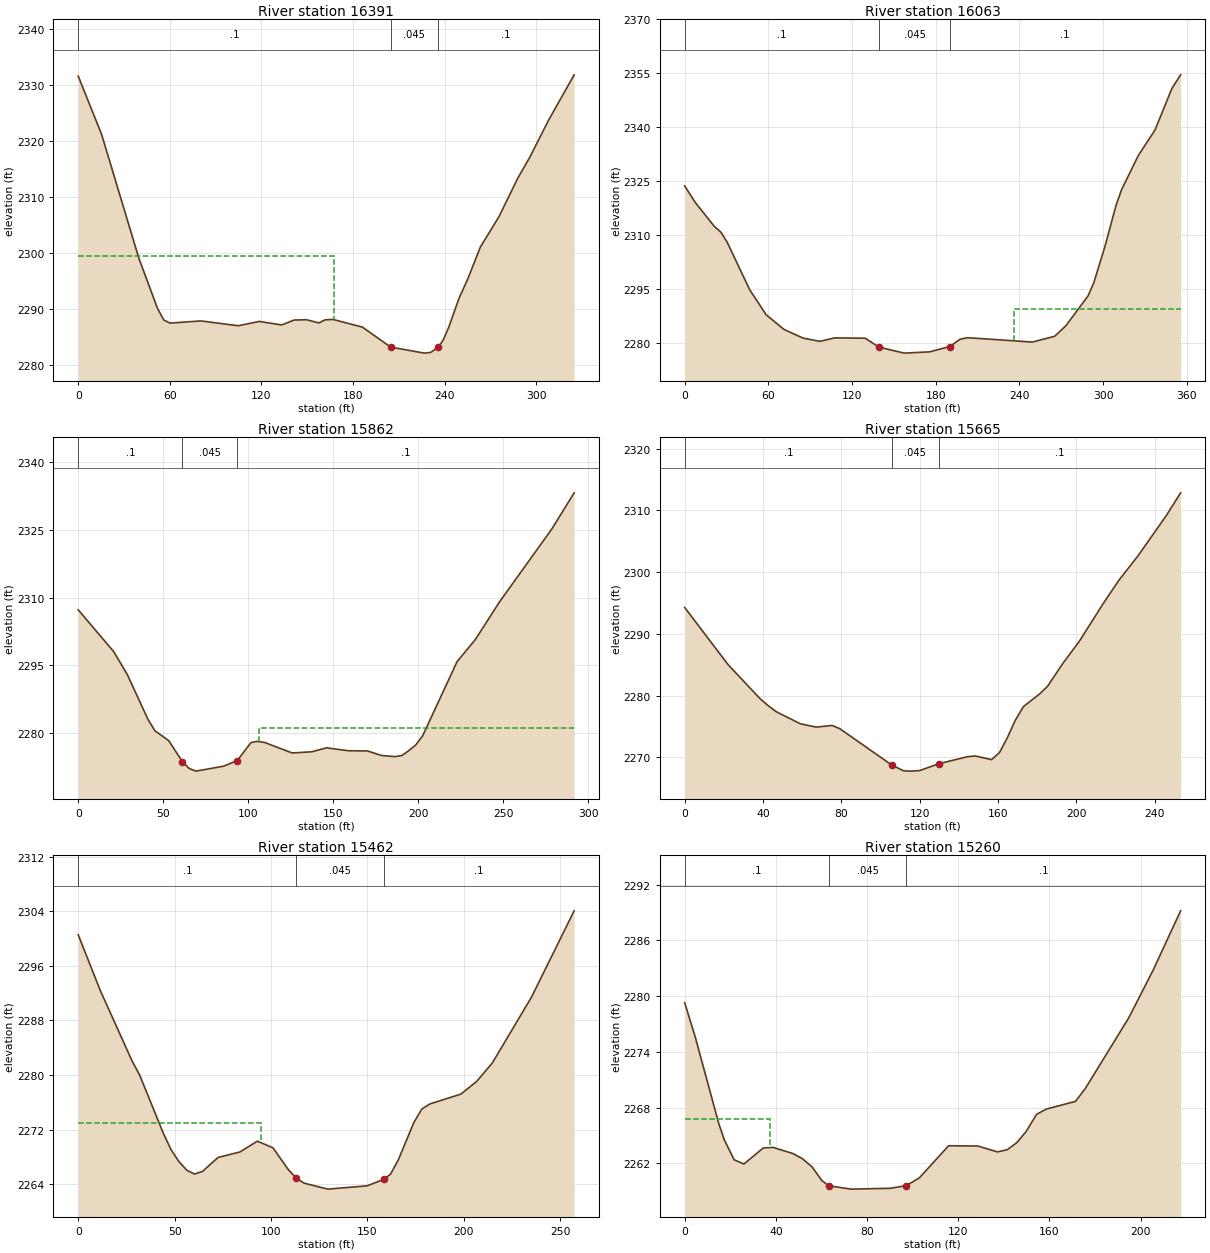
Type RM Length L Ch R = 1 ,16391   ,324.4,327.7,336.7
XS GIS Cut Line= 2
2206863.01987799 396990.110973362206804.93335334 397309.58685895
#Sta/Elev= 30
       0 2331.65    15.3 2321.25    39.7 2299.12    51.9 2290.17      56  2288.1
      60 2287.53    80.4 2287.92   104.8 2287.06   118.6 2287.83   133.2  2287.2
   141.3 2288.08   149.5 2288.13   157.6 2287.57   161.7 2288.12   166.8 2288.19
   186.1 2286.81   204.6 2283.24   226.7 2282.17   230.8  2282.3   235.6  2283.2
   238.9 2284.48   242.5 2286.72   249.3 2291.94   255.2 2295.51   263.3 2301.11
   275.5 2306.55   287.7 2313.36   295.8 2317.22     308 2323.79   324.7 2331.87
#Mann= 3 ,-1,0
       0      .1       0   204.6    .045       0   235.6      .1       0
#XS Ineff= 2 , 0
          167.61 2299.59
Permanent Ineff=
       F       F
Bank Sta=204.6,235.6
XS Rating Curve= 0 ,0
Exp/Cntr(USF)=0,0
Exp/Cntr=0.3,0.1

Type RM Length L Ch R = 1 ,16063   ,216.2,201.6,185.3
XS GIS Cut Line= 3
2206608.45817624396914.3691886212206503.34922687397110.756962447
2206506.11525186397243.526161653
#Sta/Elev= 30
       0 2323.63     7.7 2318.97    21.3 2312.33    25.9 2310.78    30.4 2308.01
    46.6 2294.71    58.4 2287.75    71.2 2283.65    84.9 2281.23    96.9 2280.33
   107.5  2281.3   129.4  2281.2   139.3 2278.72   157.4 2277.05   175.6 2277.41
   190.12278.896   197.3  2280.9   202.8 2281.35   249.2 2280.13   265.2 2281.74
   273.2 2284.65   289.2 2293.02   293.2 2296.57   301.2 2306.68   309.2 2318.21
   313.2  2322.6   325.2 2332.11   337.2 2339.25   349.2 2350.74   355.5 2354.58
#Mann= 3 ,-1,0
       0      .1       0   139.3    .045       0   190.1      .1       0
#XS Ineff= 2 , 0
                          235.94         2289.47
Permanent Ineff=
       F       F
Bank Sta=139.3,190.1
XS Rating Curve= 0 ,0
Exp/Cntr(USF)=0,0
Exp/Cntr=0.3,0.1

Type RM Length L Ch R = 1 ,15862   ,195.8,196.2,192.8
XS GIS Cut Line= 2
2206330.47266541396936.4973884892206369.19701517 397225.54699926
#Sta/Elev= 30
       0 2307.32    20.9 2298.04    28.9 2292.94      41 2283.06    45.1 2280.52
    53.2 2278.35    61.2 2273.71    65.3 2272.15    69.3 2271.58    85.4 2272.67
    93.5 2273.92   101.6 2277.91   105.3 2278.17   109.7 2277.92   125.8  2275.6
   137.4 2275.87     146 2276.74   158.7  2276.1   170.2 2276.04   178.3 2275.04
   186.3 2274.79   190.4 2275.05   194.3  2276.1   198.4 2277.35   202.5 2279.39
   222.8 2295.86   233.5 2300.73   247.7 2309.06   278.4 2325.18   291.6 2333.23
#Mann= 3 ,-1,0
       0      .1       0    61.2    .045       0    93.5      .1       0
#XS Ineff= 2 , 0
                          106.48         2281.16
Permanent Ineff=
       F       F
Bank Sta=61.2,93.5
XS Rating Curve= 0 ,0
Exp/Cntr(USF)=0,0
Exp/Cntr=0.3,0.1

Type RM Length L Ch R = 1 ,15665   ,203.8,203.6,204
XS GIS Cut Line= 2
2206146.53200401396975.2217382572206193.55442873397224.163986769
#Sta/Elev= 30
       0 2294.26    22.3 2284.95    38.6 2279.46    42.7 2278.34    46.8 2277.37
      59 2275.43    67.1 2274.88    75.3 2275.15    79.3 2274.61   105.8 2268.73
   111.9 2267.79   115.8 2267.75     120 2267.84   129.8 2268.95   144.5 2270.09
   148.5  2270.2   156.7 2269.61   160.8 2270.76   164.8 2273.16   168.9 2276.01
     173 2278.19   181.3 2280.26   185.2 2281.44   193.3 2285.27   201.5 2288.75
   213.7 2294.86   221.8 2298.68   231.3 2302.52   246.2 2309.24   253.3 2312.83
#Mann= 3 ,-1,0
       0      .1       0   105.8    .045       0   129.8      .1       0
Bank Sta=105.8,129.8
XS Rating Curve= 0 ,0
Exp/Cntr(USF)=0,0
Exp/Cntr=0.3,0.1

Type RM Length L Ch R = 1 ,15462   ,205,201.5,197.3
XS GIS Cut Line= 2
2205950.14423018397009.7970505512205995.78364241397262.888336537
#Sta/Elev= 30
       0 2300.55    11.4 2292.42    27.8 2282.16    31.9 2279.99    44.1 2271.52
    48.1 2269.12    52.2 2267.36    56.3 2266.09    60.3 2265.53    64.4  2265.9
    72.5 2267.95    83.9 2268.76    92.9 2270.34     101 2269.37   109.1 2266.12
   113.2 2264.91   117.2 2264.19   129.4 2263.32   149.8  2263.8   158.72264.773
     162 2265.53     166 2267.59   174.1 2273.09   178.2 2275.03   182.3 2275.78
   198.5 2277.23   206.7  2279.1   214.8  2281.8   235.1 2291.43   257.2 2304.05
#Mann= 3 ,-1,0
       0      .1       0   113.2    .045       0   158.7      .1       0
#XS Ineff= 2 , 0
           94.99 2272.99
Permanent Ineff=
       F       F
Bank Sta=113.2,158.7
XS Rating Curve= 0 ,0
Exp/Cntr(USF)=0,0
Exp/Cntr=0.3,0.1

Type RM Length L Ch R = 1 ,15260   ,194.2,199.2,205.3
XS GIS Cut Line= 2
 2205746.8413939 397096.926837532205824.29009343397300.229673814
#Sta/Elev= 30
       0  2279.3     4.6 2275.64      15 2266.25    17.4 2264.53    21.7 2262.39
      26 2261.94    34.5 2263.66    38.8 2263.72    47.4 2263.07    51.6 2262.52
    55.9 2261.62    60.2 2260.15    63.2 2259.59      73 2259.23    90.2 2259.32
    97.3 2259.61     103 2260.45   115.8  2263.9   128.7 2263.87   137.2 2263.24
   141.5 2263.47   145.8 2264.25   149.8 2265.43   154.4 2267.28   158.6 2267.84
   171.5 2268.68   175.8 2270.07   194.8 2277.65   205.6 2282.83   217.6 2289.19
#Mann= 3 ,-1,0
       0      .1       0    63.2    .045       0    97.3      .1       0
#XS Ineff= 2 , 0
           37.46 2266.81
Permanent Ineff=
       F       F
Bank Sta=63.2,97.3
XS Rating Curve= 0 ,0
Exp/Cntr(USF)=0,0
Exp/Cntr=0.3,0.1

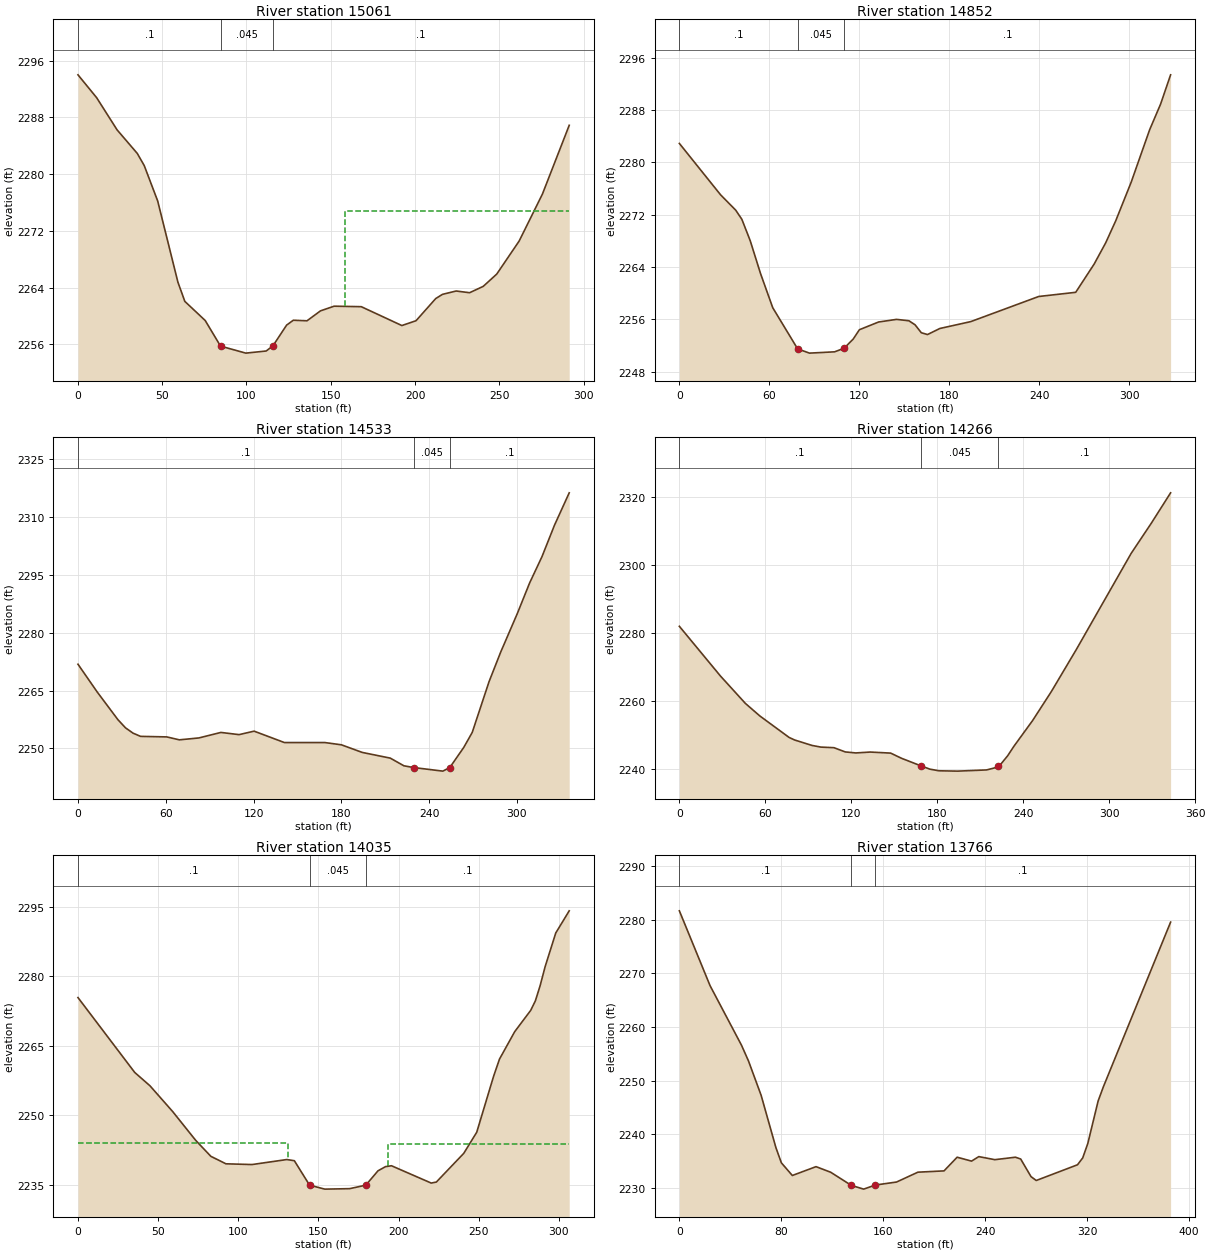
Type RM Length L Ch R = 1 ,15061   ,211.1,208.9,205.5
XS GIS Cut Line= 4
2205565.66675748397094.1608125462205583.64591987397254.590261587
2205593.32700731397344.486073549 2205612.6891822397379.061385843
#Sta/Elev= 30
       0 2294.01    11.1 2290.78    23.2 2286.25    35.2 2282.92    39.3 2281.22
    47.3 2276.22    59.3 2264.77    63.4 2262.06    75.5 2259.36    84.6 2255.75
    99.6 2254.76   111.7 2255.06   115.7 2255.79   123.8 2258.71   127.8  2259.4
   135.9 2259.32   143.9 2260.72     152 2261.38   168.1 2261.31   192.2 2258.65
   200.6 2259.33   212.3 2262.46   216.3 2263.05   224.4 2263.52   232.4 2263.28
   240.5 2264.18   248.5 2265.91   261.8 2270.57   275.6 2277.19   291.5 2286.89
#Mann= 3 ,-1,0
       0      .1       0    84.6    .045       0   115.7      .1       0
#XS Ineff= 2 , 0
                           158.2         2274.84
Permanent Ineff=
       F       F
Bank Sta=84.6,115.7
XS Rating Curve= 0 ,0
Exp/Cntr(USF)=0,0
Exp/Cntr=0.3,0.1

Type RM Length L Ch R = 1 ,14852   ,308.9,318.9,328.6
XS GIS Cut Line= 3
2205347.15078379397128.7361248392205403.85429595  397352.7841485
2205381.72609608397446.828997937
#Sta/Elev= 30
       0 2282.91    27.5 2275.05    37.6  2272.7    41.7  2271.3    47.3 2268.01
    54.1 2263.04    62.3 2257.78    78.9 2251.49    86.8 2250.84   103.6 2251.04
   109.9 2251.59     116    2253   120.1 2254.42   132.9  2255.6   144.9    2256
   153.1 2255.79   157.2 2255.18   161.4 2253.96   165.5 2253.68   173.8 2254.61
   194.4 2255.66   239.7  2259.5   264.4 2260.14   276.7 2264.46   284.4 2267.71
   291.1 2271.08   301.4 2276.98   313.7 2284.99     321 2288.91   327.7  2293.4
#Mann= 3 ,-1,0
       0      .1       0    78.9    .045       0   109.9      .1       0
Bank Sta=78.9,109.9
XS Rating Curve= 0 ,0
Exp/Cntr(USF)=0,0
Exp/Cntr=0.3,0.1

Type RM Length L Ch R = 1 ,14533   ,252.8,267.1,284.8
XS GIS Cut Line= 4
2205212.49521068397112.0319945052205068.34499948397288.071501276
2205060.67571583397316.5574119762205003.91282606397371.104701651
#Sta/Elev= 30
       0 2271.82    13.1 2264.65    27.3 2257.45    32.5 2255.33    37.7 2253.94
    42.8 2253.12    60.7 2252.98    69.3 2252.22    82.6 2252.71    97.7 2254.14
   110.1 2253.57   120.4 2254.47   141.1 2251.52   168.7 2251.52   180.1 2250.93
   194.3 2248.96   213.5 2247.48   222.8 2245.49229.51192245.038   249.4 2244.11
 254.146 2245.03   263.7 2250.25   269.5 2254.14     281  2267.3   288.9 2274.91
   300.3 2284.94   308.7 2292.85   317.2 2299.72   325.7 2307.83   335.8 2316.25
#Mann= 3 ,-1,0
       0      .1       0229.5119    .045       0 254.146      .1       0
Bank Sta=229.5119,254.146
XS Rating Curve= 0 ,0
Exp/Cntr(USF)=0,0
Exp/Cntr=0.3,0.1

Type RM Length L Ch R = 1 ,14266   ,232.9,230.9,221.1
XS GIS Cut Line= 3
2205106.50661023397005.6480130752204850.64929925397116.289012414
2204811.92494949397167.460474608
#Sta/Elev= 30
       0 2281.99    28.7 2267.33    46.1 2259.26    56.2 2255.56    76.6 2249.24
    80.5 2248.48    92.7 2246.87    98.8 2246.39   107.9 2246.22   115.8 2244.97
   123.1 2244.67   133.3 2244.93   147.5 2244.62   155.1 2243.09   168.7 2240.85
   174.8  2239.9   181.2 2239.41   194.3 2239.31   214.4 2239.66   220.4  2240.3
  222.68 2240.88   224.8 2241.58   229.2 2243.86   233.5 2246.62   246.6 2254.23
   259.7 2262.79   277.1 2275.16   315.4 2303.51   329.3 2312.29   342.9 2321.33
#Mann= 3 ,-1,0
       0      .1       0   168.7    .045       0  222.68      .1       0
Bank Sta=168.7,222.68
XS Rating Curve= 0 ,0
Exp/Cntr(USF)=0,0
Exp/Cntr=0.3,0.1

Type RM Length L Ch R = 1 ,14035   ,278.2,269.3,259.2
XS GIS Cut Line= 2
2204946.07716118396805.1112017742204687.45382523 396969.68968829
#Sta/Elev= 30
       0 2275.41    35.4 2259.24    44.9 2256.36    59.1 2250.78    73.4 2244.59
    82.9 2241.12    92.3  2239.5   108.6 2239.34   130.3 2240.42     135 2240.17
   144.5 2234.89     154 2234.03   169.5 2234.13  179.61 2234.89   187.2 2237.99
   191.9 2238.89   195.6 2239.08   220.4 2235.34   223.6 2235.56   240.7 2241.76
   248.8 2246.32   259.3 2258.39     263 2262.12   272.5 2268.05   282.5 2272.66
   285.4 2274.72   288.3 2277.92   291.5 2282.12   298.1 2289.36   306.5 2294.15
#Mann= 3 ,-1,0
       0      .1       0   144.5    .045       0  179.61      .1       0
#XS Ineff= 2 , 0
          130.93 2243.91  193.24         2243.83
Permanent Ineff=
       F       F
Bank Sta=144.5,179.61
XS Rating Curve= 0 ,0
Exp/Cntr(USF)=0,0
Exp/Cntr=0.3,0.1

Type RM Length L Ch R = 1 ,13766   ,220.2,212,194
XS GIS Cut Line= 3
2204697.13491267396554.7859407712204607.23910071396780.216976923
2204583.72788835 396921.28425108
#Sta/Elev= 30
       0 2281.66    24.1 2267.71    48.8  2256.6    54.3 2253.66    64.2 2247.27
    75.8 2237.52    80.1 2234.68    88.7 2232.32   107.3 2233.97   118.8 2232.93
     135 2230.48   144.7 2229.78   153.8 2230.54   170.5  2231.1   187.3 2232.94
   207.8 2233.18   218.1 2235.73   229.4    2235   235.1 2235.84   247.7 2235.27
   263.9 2235.73     268 2235.39   276.1 2232.11   280.2 2231.39   312.6 2234.32
   316.7  2235.6   320.7  2238.3   328.8 2246.21   332.9 2248.85   385.7 2279.55
#Mann= 3 ,-1,0
       0      .1       0     135    .045       0   153.8      .1       0
Bank Sta=135,153.8
XS Rating Curve= 0 ,0
Exp/Cntr(USF)=0,0
Exp/Cntr=0.3,0.1

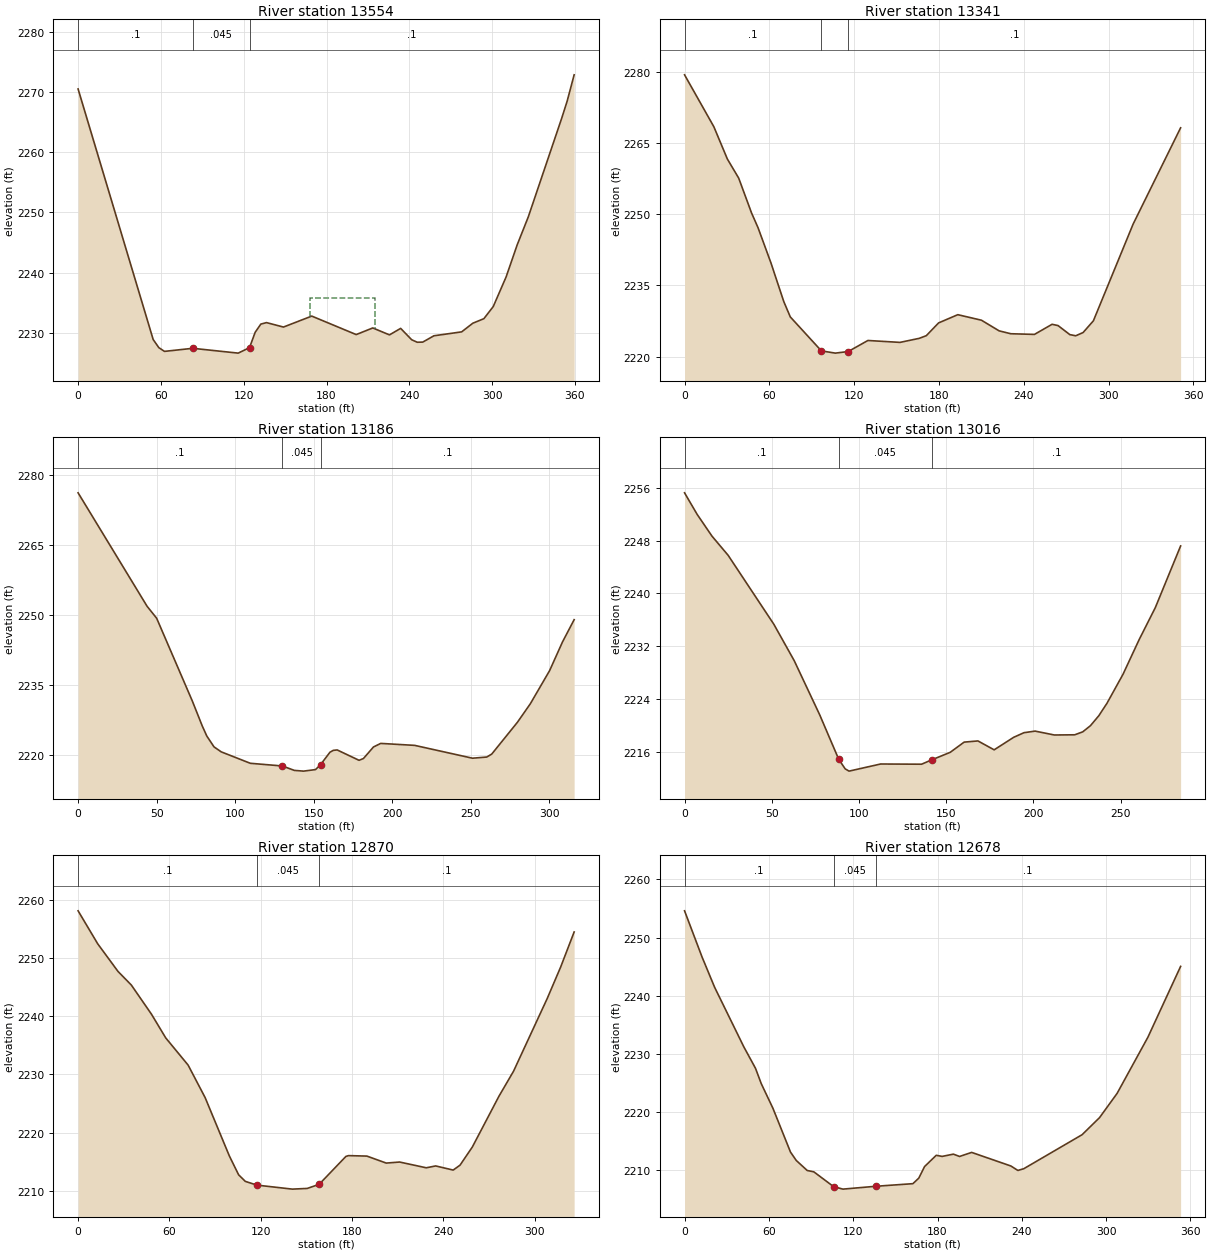
Type RM Length L Ch R = 1 ,13554   ,217.2,212.7,209.3
XS GIS Cut Line= 3
2204419.14940184396556.1689532632204456.49073911396717.981414795
2204477.23592649396910.220151146
#Sta/Elev= 30
       0 2270.48    54.4 2228.87    58.5 2227.52    62.6  2226.9    83.1 2227.41
     116 2226.61   124.2 2227.52   128.3 2230.07   132.4 2231.43   136.5 2231.68
   148.8 2230.94   169.3 2232.76   201.5 2229.69   213.5 2230.79   225.6 2229.64
   233.7 2230.72   241.7 2228.83   245.7 2228.42   249.7 2228.44   257.8 2229.49
   277.9 2230.14     286 2231.58     294 2232.33   300.8 2234.35   310.1 2239.26
   318.1 2244.57   326.2 2249.25   350.4 2265.63   354.3 2268.43   359.4 2272.83
#Mann= 3 ,-1,0
       0      .1       0    83.1    .045       0   124.2      .1       0
#XS Ineff= 1 ,-1
  167.89  214.76 2235.83
Permanent Ineff=
       F
Bank Sta=83.1,124.2
XS Rating Curve= 0 ,0
Exp/Cntr(USF)=0,0
Exp/Cntr=0.3,0.1

Type RM Length L Ch R = 1 ,13341   ,155.9,155.5,156.5
XS GIS Cut Line= 3
2204189.56932821396615.6384904072204282.23116515396784.366014398
2204326.48756489396936.497388489
#Sta/Elev= 30
       0 2279.33    20.7 2268.42    30.3  2261.6    38.3 2257.59    47.4 2250.25
      52 2247.14    61.1 2239.76    70.2  2231.6    74.8 2228.38    96.8 2221.23
   106.7 2220.76   115.8  2221.1   129.7 2223.42   152.4 2223.02     166 2223.87
     171 2224.43   179.7 2227.12   193.3 2228.85     210 2227.69   222.5 2225.45
   230.8 2224.84   247.5  2224.7     260 2226.83   264.2 2226.56   272.5 2224.66
   276.7 2224.41   281.9 2225.09   289.2 2227.56   317.3 2247.91   350.9 2268.18
#Mann= 3 ,-1,0
       0      .1       0    96.8    .045       0   115.8      .1       0
Bank Sta=96.8,115.8
XS Rating Curve= 0 ,0
Exp/Cntr(USF)=0,0
Exp/Cntr=0.3,0.1

Type RM Length L Ch R = 1 ,13186   ,170.4,170.1,170.3
XS GIS Cut Line= 3
2204051.26807904396686.1721274862204152.22799093396861.814713935
2204175.73920329396972.455713274
#Sta/Elev= 30
       0 2276.27    43.9 2251.96      50 2249.39    72.7 2231.65      79 2226.32
    81.9 2224.15    86.5 2221.82    91.1 2220.75   109.6  2218.3     1302217.724
   137.6 2216.78   143.5 2216.62   151.1 2216.95   154.3 2218.01   160.3 2220.67
   162.4 2221.07   164.9 2221.16   178.8 2218.94   181.6 2219.32     188  2221.8
   192.6 2222.56   214.2 2222.14     251 2219.39   260.1 2219.64   263.3 2220.29
   279.6 2227.09   287.8 2231.05   300.1 2238.17   308.3 2244.32   315.7 2249.08
#Mann= 3 ,-1,0
       0      .1       0     130    .045       0   154.3      .1       0
Bank Sta=130,154.3
XS Rating Curve= 0 ,0
Exp/Cntr(USF)=0,0
Exp/Cntr=0.3,0.1

Type RM Length L Ch R = 1 ,13016   ,143.6,146,146.7
XS GIS Cut Line= 2
2203919.88189232396799.5791518072204062.33217897397045.755375336
#Sta/Elev= 30
       0 2255.25     7.2 2251.99    15.7 2248.69      25 2245.77    51.2 2235.31
    62.9 2229.78    77.5 2221.57    88.4 2214.83    92.1 2213.38    94.3 2213.04
   112.4 2214.12   135.9 2214.09   141.9 2214.77   152.3 2215.89   160.3 2217.44
   168.2 2217.62   177.5 2216.27   188.7 2218.17   194.6 2218.87     201 2219.11
     212 2218.52   223.7 2218.55   228.3    2219   232.7 2219.93   237.5 2221.44
   242.2 2223.34   251.4 2227.74   260.6 2232.97   269.9 2237.84   284.4 2247.19
#Mann= 3 ,-1,0
       0      .1       0    88.4    .045       0   141.9      .1       0
Bank Sta=88.4,141.9
XS Rating Curve= 0 ,0
Exp/Cntr(USF)=0,0
Exp/Cntr=0.3,0.1

Type RM Length L Ch R = 1 ,12870   ,188.8,191.8,195
XS GIS Cut Line= 2
2203791.95707777396845.4442734882203928.90857151 397141.25949998
#Sta/Elev= 30
       0 2258.07    12.9 2252.41    26.2 2247.68      35 2245.33    48.2 2240.34
    57.6 2236.26    72.3  2231.6    83.5 2226.01    99.4 2216.01   105.5 2212.77
   109.9 2211.64   117.5    2211   140.8 2210.31   150.6 2210.43   158.4 2211.13
     176 2215.92   177.7 2216.06   189.8 2215.98   202.5 2214.78   211.3 2214.96
   228.8 2213.97     235 2214.29   246.5 2213.58     251 2214.42   259.1 2217.54
   276.6 2226.26   286.2 2230.56   308.3 2243.02   317.1  2248.4     326 2254.44
#Mann= 3 ,-1,0
       0      .1       0   117.5    .045       0   158.4      .1       0
Bank Sta=117.5,158.4
XS Rating Curve= 0 ,0
Exp/Cntr(USF)=0,0
Exp/Cntr=0.3,0.1

Type RM Length L Ch R = 1 ,12678   ,252.2,254.7,261.6
XS GIS Cut Line= 2
2203629.44926906396900.539063704 2203723.4941185397240.760136669
#Sta/Elev= 30
       0  2254.6    12.5 2246.61    21.4 2241.42    42.2 2231.14    50.5 2227.45
    54.6  2224.8    62.9 2220.56    75.4 2213.01    79.5 2211.57    87.3 2209.84
      92 2209.61     106 2207.07   112.7 2206.63     136 2207.12   162.5 2207.57
   166.7 2208.53   170.8 2210.52   179.1 2212.46   183.3 2212.27   191.3 2212.66
   195.7 2212.26   204.3 2212.96   232.2 2210.62   237.2 2209.85   241.4 2210.15
   282.9 2216.01   295.3 2218.95   307.8 2223.13   329.7  2232.8     353 2245.02
#Mann= 3 ,-1,0
       0      .1       0     106    .045       0     136      .1       0
Bank Sta=106,136
XS Rating Curve= 0 ,0
Exp/Cntr(USF)=0,0
Exp/Cntr=0.3,0.1

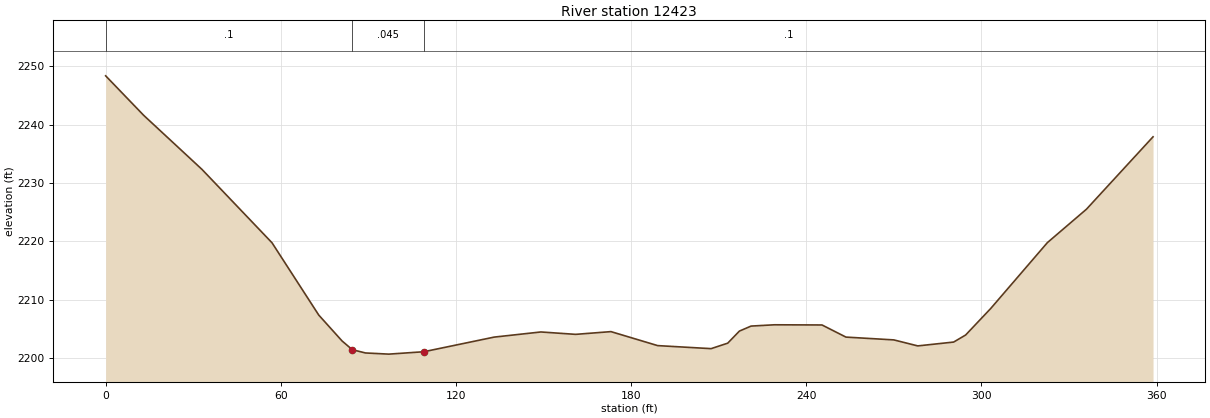
Type RM Length L Ch R = 1 ,12423   ,174.6,181.6,189.4
XS GIS Cut Line= 3
2203402.63522041396928.1993135382203410.93329536397164.694449624
2203383.27304553397283.633523913
#Sta/Elev= 30
       0  2248.4      13 2241.64      33 2232.35      57 2219.76      73 2207.37
      81 2202.92    84.52201.429      89 2200.87      97 2200.67     109 2201.08
   133.1 2203.59   149.1 2204.47     161 2204.06   173.1 2204.53   189.1 2202.13
   207.4 2201.61   213.1 2202.55   217.1 2204.62   221.1 2205.48   229.1  2205.7
   245.4 2205.67   253.6 2203.59     270 2203.11   278.2 2202.08   290.5 2202.74
   294.6 2203.95   303.2  2208.5   322.6 2219.79     336 2225.53   358.8 2237.94
#Mann= 3 ,-1,0
       0      .1       0    84.5    .045       0     109      .1       0
Bank Sta=84.5,109
XS Rating Curve= 0 ,0
Exp/Cntr(USF)=0,0
Exp/Cntr=0.3,0.1