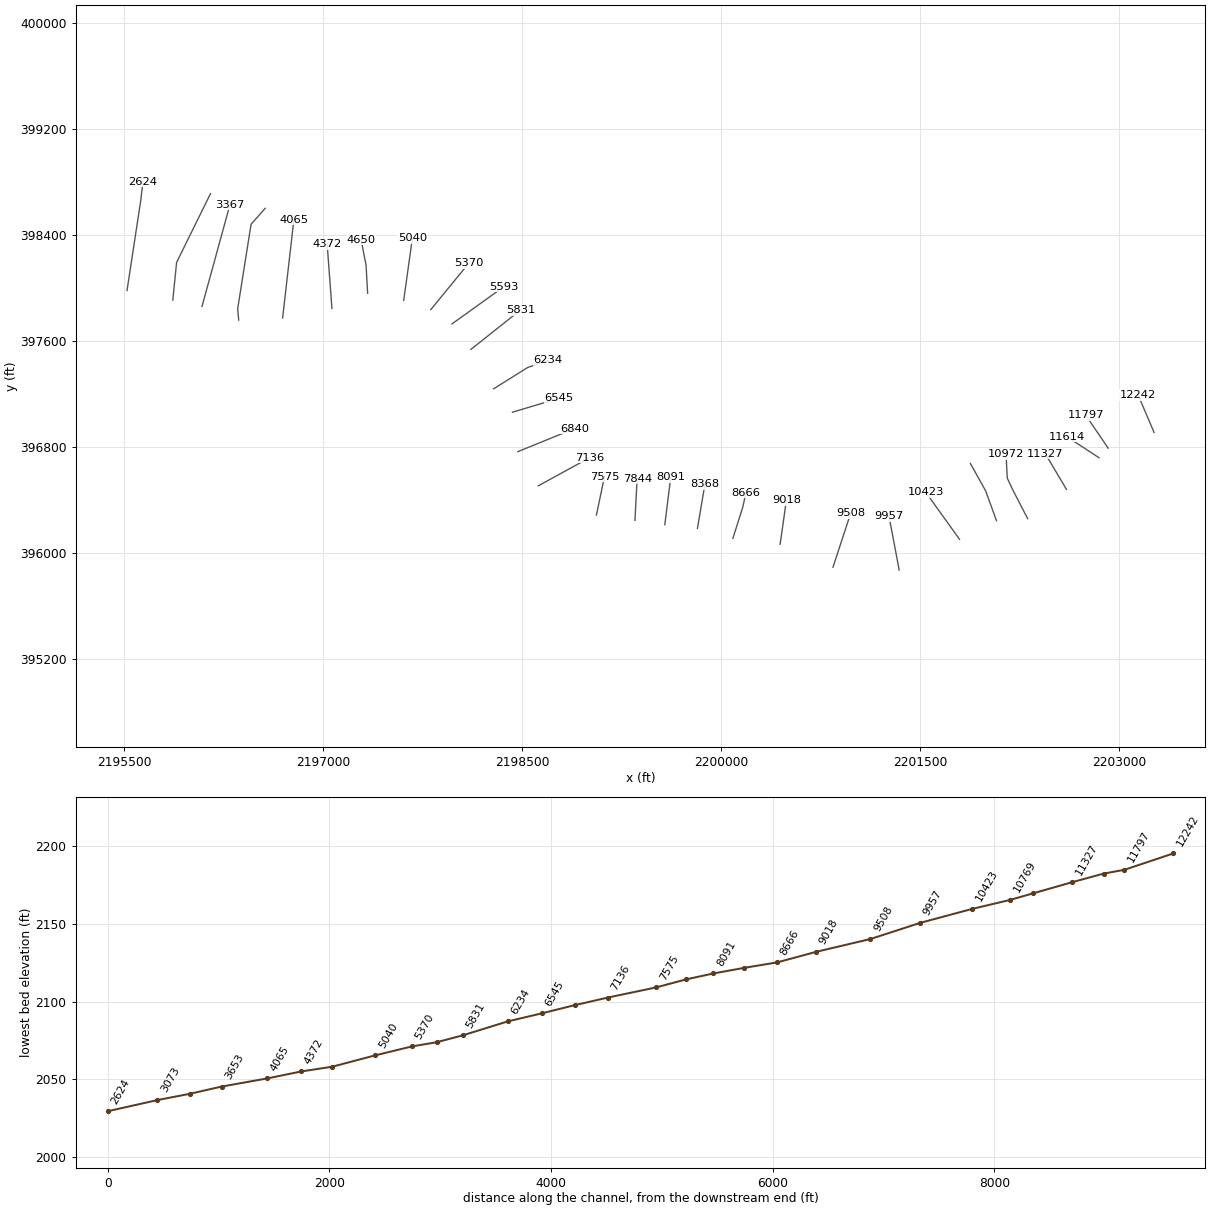
HEC-RAS study LAURELRN1.prj: LAURELRN1

--- LAURELRN1.g01 (geometry) --- (continued)

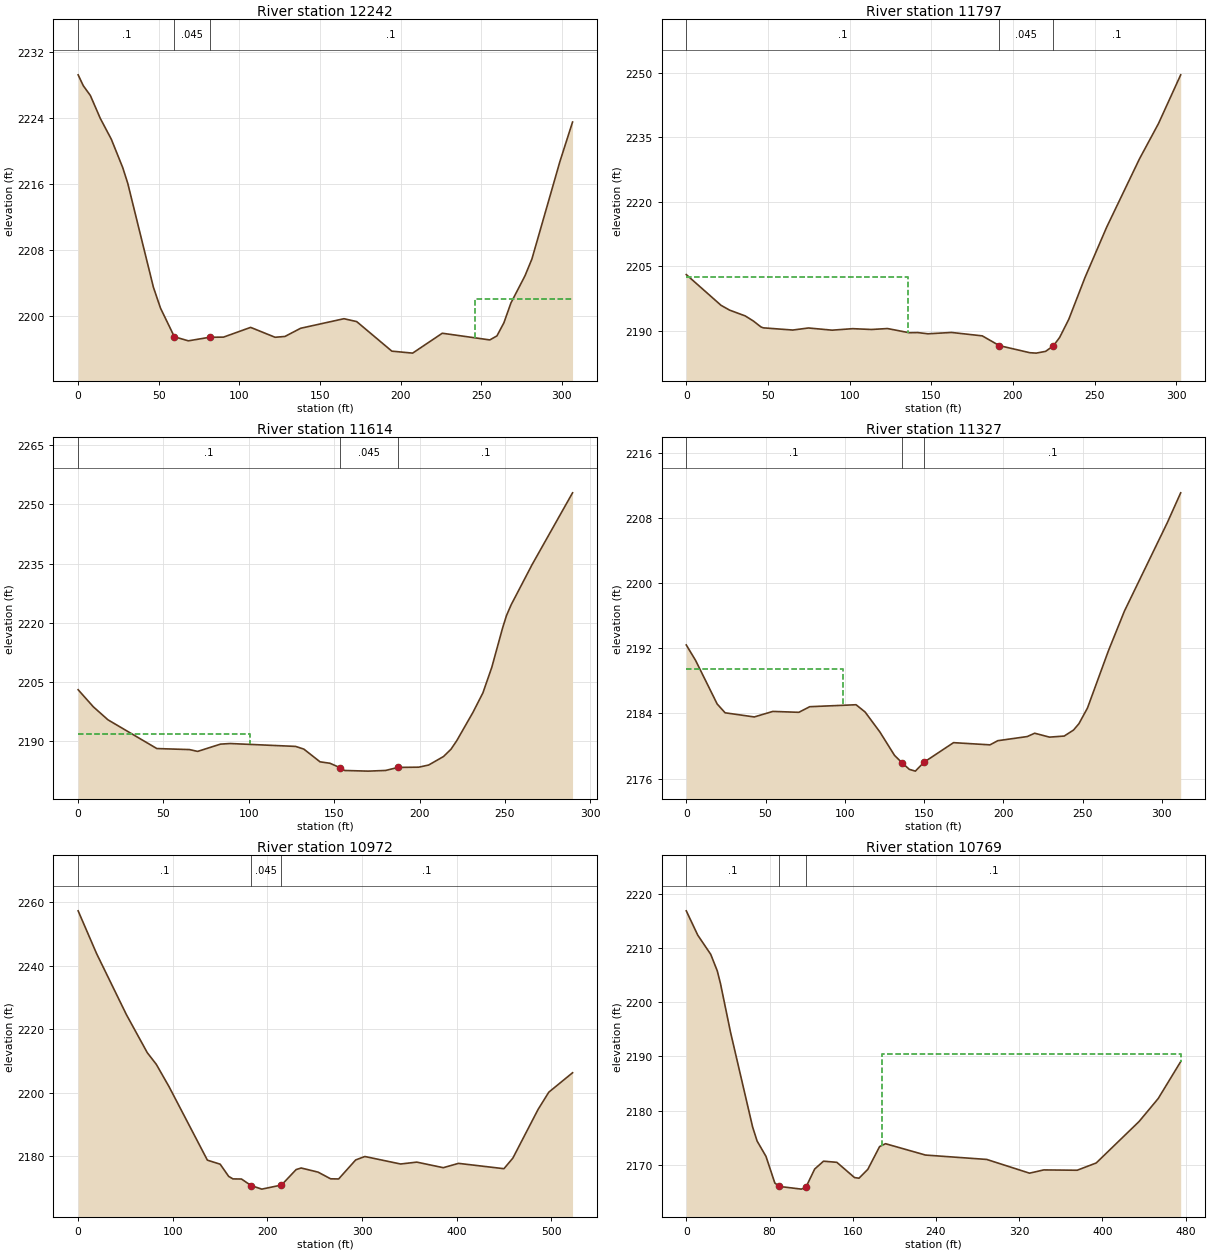
Type RM Length L Ch R = 1 ,12242   ,433.2,444.5,446
XS GIS Cut Line= 2
2203261.56794626396910.2201511462203141.24585948397192.354699459
#Sta/Elev= 30
       0 2229.19     3.2 2227.87     7.6 2226.68    13.7 2223.93    20.6 2221.38
    27.7 2217.93    30.8 2216.03    46.7 2203.45    51.1 2200.92    59.7 2197.45
    68.4 2196.96    81.5 2197.39    90.2 2197.41     107 2198.59   122.2 2197.39
   128.3 2197.49     138 2198.48   164.9 2199.64   172.8 2199.29   194.6 2195.71
   207.5 2195.47   225.9 2197.88   255.4 2197.07   259.8 2197.56   264.1 2199.14
   268.5 2201.56   277.2 2204.84   281.5 2206.88   298.9 2218.71   306.7 2223.47
#Mann= 3 ,-1,0
       0      .1       0    59.7    .045       0    81.5      .1       0
#XS Ineff= 2 , 0
                          246.08         2202.07
Permanent Ineff=
       F       F
Bank Sta=59.7,81.5
XS Rating Curve= 0 ,0
Exp/Cntr(USF)=0,0
Exp/Cntr=0.3,0.1

Type RM Length L Ch R = 1 ,11797   ,170.7,183.1,188
XS GIS Cut Line= 2
2202915.81482332396791.2810768572202745.70428684 397041.60633786
#Sta/Elev= 30
       0 2203.12    21.3 2195.98    26.5 2194.87    36.1 2193.52      41 2192.36
    45.8 2190.94    47.2 2190.75    65.2 2190.24    74.8 2190.72    89.3 2190.21
   101.9 2190.56   113.4 2190.37   123.2 2190.59   136.4 2189.62   141.7 2189.65
     148 2189.37   162.4 2189.68   181.2 2188.89   191.72186.619   210.3 2184.98
   214.2 2184.88     220 2185.29   224.8 2186.59   228.6 2188.53   234.2 2192.75
   244.1 2202.43   257.4 2214.15   277.5 2230.02   289.1 2238.19   302.7 2249.51
#Mann= 3 ,-1,0
       0      .1       0   191.7    .045       0   224.8      .1       0
#XS Ineff= 2 , 0
          135.86 2202.47
Permanent Ineff=
       F       F
Bank Sta=191.7,224.8
XS Rating Curve= 0 ,0
Exp/Cntr(USF)=0,0
Exp/Cntr=0.3,0.1

Type RM Length L Ch R = 1 ,11614   ,289,287.2,278.5
XS GIS Cut Line= 2
2202846.66419874396719.3644272872202604.63701269396878.410863836
#Sta/Elev= 30
       0 2203.09     8.9 2198.77    17.5 2195.47    46.1 2188.21    65.2 2187.95
      70 2187.49    83.4 2189.33    89.1 2189.48   127.4 2188.75   132.2 2188.07
   141.7 2184.85   147.5 2184.49   153.42183.374   156.1 2182.66   169.9  2182.5
   180.1 2182.67   187.42183.438   199.5  2183.5   205.3 2184.04     214 2186.19
   218.4 2188.04   221.8 2190.22   231.3 2197.39   237.1  2202.3   242.3 2208.76
   248.6 2218.68   250.9 2221.84   253.6 2224.54   265.9 2234.73   289.6 2252.89
#Mann= 3 ,-1,0
       0      .1       0   153.4    .045       0   187.4      .1       0
#XS Ineff= 2 , 0
          100.56 2191.97
Permanent Ineff=
       F       F
Bank Sta=153.4,187.4
XS Rating Curve= 0 ,0
Exp/Cntr(USF)=0,0
Exp/Cntr=0.3,0.1

Type RM Length L Ch R = 1 ,11327   ,355.3,354.7,354
XS GIS Cut Line= 2
 2202601.8709877396480.1032662182202442.82455115396748.407689613
#Sta/Elev= 30
       0 2192.42     5.9 2190.51    19.5 2185.16    24.5 2184.08    42.9 2183.57
    54.6 2184.25      71 2184.14    77.9 2184.83   107.1 2185.07   112.8 2184.18
   122.1 2181.73   131.4 2178.84   136.1 2177.94   140.7 2177.13   144.5 2176.91
     150 2178.01   168.6 2180.41   191.6 2180.14   196.5 2180.65   215.1 2181.16
   219.8 2181.57   229.1 2181.09   238.4 2181.22   244.3 2181.96   247.7 2182.74
   253.1 2184.67   266.3  2191.7   276.4 2196.58   303.5 2207.47   311.9 2211.12
#Mann= 3 ,-1,0
       0      .1       0   136.1    .045       0     150      .1       0
#XS Ineff= 2 , 0
           98.59 2189.45
Permanent Ineff=
       F       F
Bank Sta=136.1,150
XS Rating Curve= 0 ,0
Exp/Cntr(USF)=0,0
Exp/Cntr=0.3,0.1

Type RM Length L Ch R = 1 ,10972   ,205,203,200.6
XS GIS Cut Line= 4
2202309.35861162396259.839885816  2202195.530423396479.907717148
2202155.69055698396565.278858613 2202146.2048746396745.506823927
#Sta/Elev= 30
       0 2257.28    19.5 2243.82      51 2224.61    73.1 2212.61    82.6 2208.96
    96.1 2201.91   136.6 2178.79   150.1 2177.52   159.1 2173.68   163.6 2172.89
   172.6 2172.85   182.9 2170.78   194.1 2169.67   214.9 2170.96   230.4 2175.83
   235.7 2176.32   253.6 2175.02   266.8 2172.92   275.3 2172.87   293.3 2178.86
     303 2179.94   340.8 2177.58   357.9 2178.17   385.9 2176.42     402 2177.78
     450  2176.1   459.4 2179.43   486.1 2194.77   497.4 2200.19   522.5  2206.3
#Mann= 3 ,-1,0
       0      .1       0   182.9    .045       0   214.9      .1       0
Bank Sta=182.9,214.9
XS Rating Curve= 0 ,0
Exp/Cntr(USF)=0,0
Exp/Cntr=0.3,0.1

Type RM Length L Ch R = 1 ,10769   ,344,346.6,352
XS GIS Cut Line= 3
2202074.37132429396245.2249085122201992.39629133396470.070713193
2201877.63124519396676.179367484
#Sta/Elev= 30
       0 2216.82      11 2212.35    23.5  2208.8    29.8 2205.75    32.9 2203.39
    42.5 2194.47    63.8 2176.95    68.1 2174.38    76.6 2171.57    85.1 2166.66
    89.4 2166.03   110.6 2165.53   114.9 2165.84   123.4 2169.23   131.9 2170.68
   144.7 2170.47   161.7 2167.66     166 2167.54   174.5 2169.18   185.8 2173.37
   191.5  2173.9   229.9 2171.81   288.8    2171   329.9 2168.47   343.6 2169.07
   375.7 2169.01     394 2170.35   435.2 2177.99   453.6 2182.23   475.2 2189.03
#Mann= 3 ,-1,0
       0      .1       0    89.4    .045       0   114.9      .1       0
#XS Ineff= 2 , 0
                          187.89         2190.46
Permanent Ineff=
       F       F
Bank Sta=89.4,114.9
XS Rating Curve= 0 ,0
Exp/Cntr(USF)=0,0
Exp/Cntr=0.3,0.1

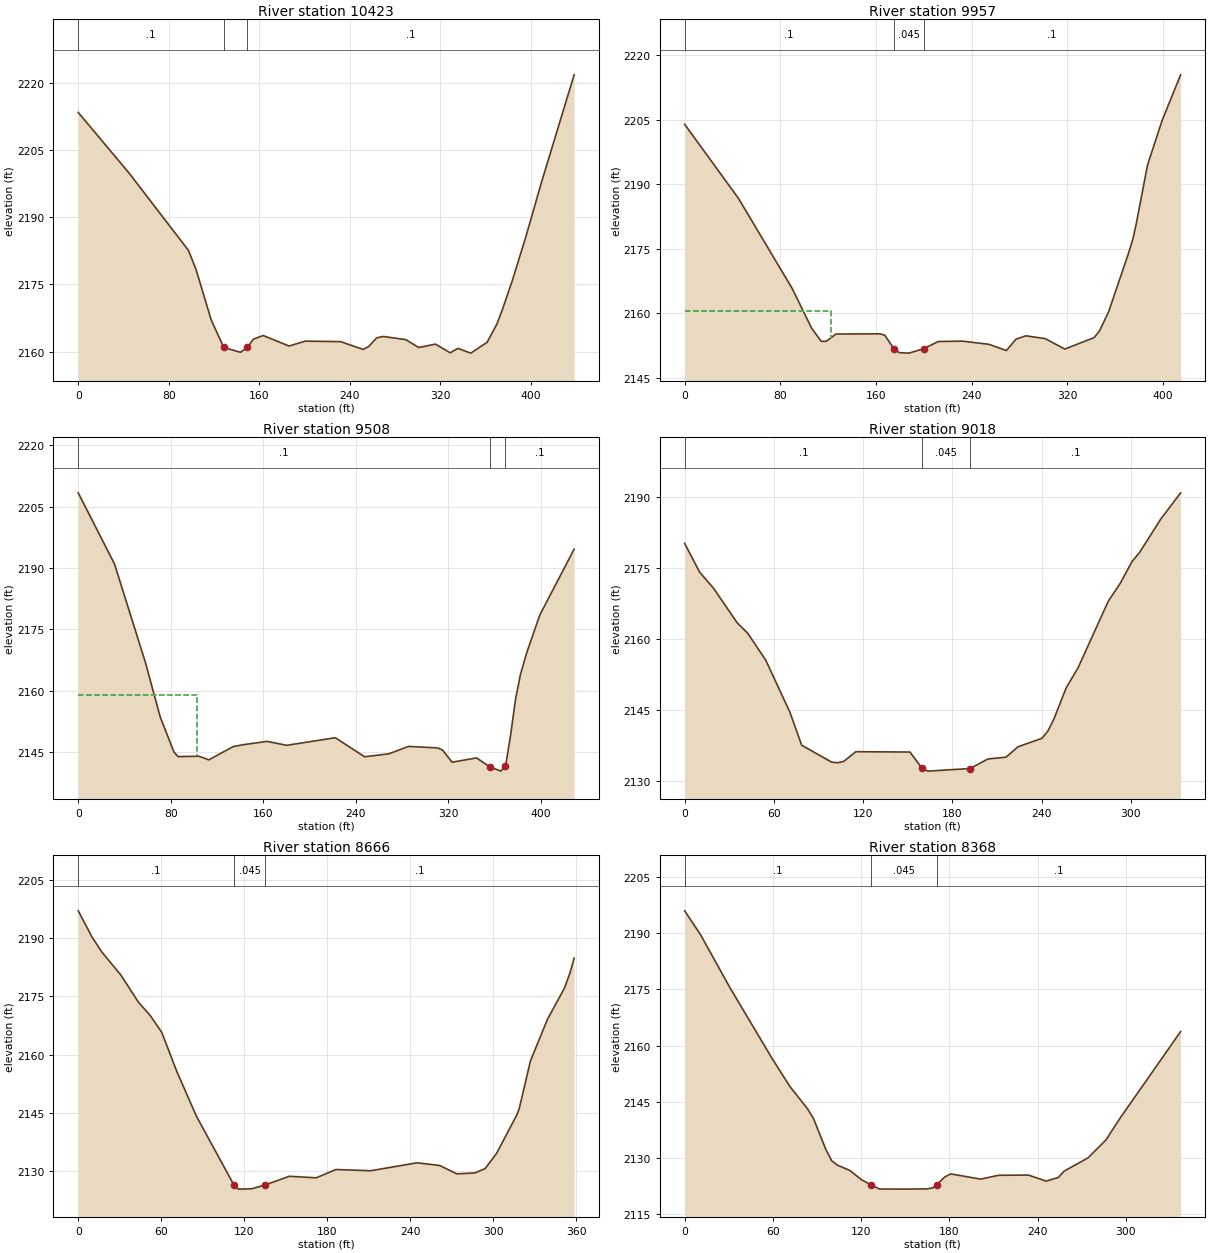
Type RM Length L Ch R = 1 ,10423   ,471.5,465.6,457.2
XS GIS Cut Line= 2
2201795.65621224396104.6962805862201540.36253817396460.702137998
#Sta/Elev= 30
       0 2213.34    44.9 2199.82    97.4 2182.57     104 2178.37   117.5 2167.06
   128.6 2160.92   143.3 2159.85  149.42 2160.93   154.8 2162.79   163.4 2163.58
   186.3 2161.24   200.6 2162.34   231.9 2162.22   251.6 2160.49   256.5 2161.11
   263.7 2163.07   269.4 2163.38   289.5 2162.66   300.8 2160.91   315.6 2161.67
   328.6 2159.73   335.4 2160.72   346.8 2159.66   361.2 2162.07   369.8 2166.12
   374.7 2169.36   383.5 2175.85   395.6 2185.75   409.1 2197.64   438.1 2221.72
#Mann= 3 ,-1,0
       0      .1       0   128.6    .045       0  149.42      .1       0
Bank Sta=128.6,149.42
XS Rating Curve= 0 ,0
Exp/Cntr(USF)=0,0
Exp/Cntr=0.3,0.1

Type RM Length L Ch R = 1 ,9957    ,460.5,449.1,439.2
XS GIS Cut Line= 2
2201341.28031528395872.8240445092201263.98956992396280.357065493
#Sta/Elev= 30
       0 2203.98    45.1 2186.69    89.9 2165.78   106.2 2156.52   114.2 2153.46
   118.4 2153.48   126.6 2155.17   163.2 2155.21   167.3 2154.91   174.9 2151.79
   179.5 2150.83   187.6 2150.72   199.9 2151.75   212.1 2153.42   232.4 2153.51
   254.5 2152.77   269.1 2151.33   277.2 2153.99   285.4 2154.75   301.6 2154.09
   317.9 2151.67   342.4 2154.32   346.9 2155.86   354.6 2160.36   370.9 2173.69
   374.9  2177.3   377.7 2180.83   387.1  2194.5   399.3 2204.85   414.8  2215.5
#Mann= 3 ,-1,0
       0      .1       0   174.9    .045       0   199.9      .1       0
#XS Ineff= 2 , 0
          122.12 2160.44
Permanent Ineff=
       F       F
Bank Sta=174.9,199.9
XS Rating Curve= 0 ,0
Exp/Cntr(USF)=0,0
Exp/Cntr=0.3,0.1

Type RM Length L Ch R = 1 ,9508    ,489.1,489.3,490.4
XS GIS Cut Line= 2
2200842.40368614395893.9033386982200975.90588267396301.436359682
#Sta/Elev= 30
       0 2208.37    31.4 2190.96    58.2 2166.81    70.8 2153.65    82.8 2144.98
    86.4 2143.86   104.5 2143.95   112.9 2143.06   133.9  2146.3   142.3 2146.76
   163.4 2147.59   180.2 2146.62   222.3 2148.48   247.6 2143.82   268.6 2144.54
   285.5 2146.35   310.7 2145.99   314.9  2145.5   323.3 2142.49   344.4 2143.54
   355.9 2141.36   365.4 2140.31   368.92141.447   369.6 2141.72   373.9 2149.16
   378.1 2157.86   382.3 2163.85   387.6 2169.12   399.1 2178.48   428.8 2194.61
#Mann= 3 ,-1,0
       0      .1       0   355.9    .045       0   368.9      .1       0
#XS Ineff= 2 , 0
          102.92 2158.82
Permanent Ineff=
       F       F
Bank Sta=355.9,368.9
XS Rating Curve= 0 ,0
Exp/Cntr(USF)=0,0
Exp/Cntr=0.3,0.1

Type RM Length L Ch R = 1 ,9018    ,354.1,352.5,350.9
XS GIS Cut Line= 2
2200444.23924035396067.2219798062200491.08211633396397.464255431
#Sta/Elev= 30
       0 2180.12    10.1 2174.04    19.4 2170.67    35.3 2163.37    42.4 2161.17
    54.5 2155.49    70.7 2144.55    78.7 2137.52    98.9 2133.95     103 2133.83
     107 2134.12   115.1 2136.16   151.5 2136.09   159.5 2132.71   163.6 2132.06
   191.9 2132.61     204 2134.63   216.1 2135.01   224.2 2137.21   240.3 2138.99
   244.4  2140.6   248.4 2143.15   256.5 2149.59   264.6 2153.91   284.8 2167.89
   292.9 2171.71   300.9 2176.33     306 2178.26   320.1 2185.24   333.5  2190.8
#Mann= 3 ,-1,0
       0      .1       0   159.5    .045       0   191.9      .1       0
Bank Sta=159.5,191.9
XS Rating Curve= 0 ,0
Exp/Cntr(USF)=0,0
Exp/Cntr=0.3,0.1

Type RM Length L Ch R = 1 ,8666    ,294.2,297.8,303
XS GIS Cut Line= 3
2200088.23338294396111.722711982 2200163.1819845396348.279235657
2200186.60342249  396456.0178504
#Sta/Elev= 30
       0 2197.12     9.9 2190.42      17 2186.51    30.9 2180.51    43.5 2173.53
    51.9 2170.15    60.3 2165.79    71.2 2155.68    85.4 2144.11   112.6 2126.26
   115.8 2125.25   125.4 2125.34   135.2 2126.35   152.6 2128.57     172 2128.17
   186.2 2130.31   211.4    2130   244.9 2132.05   261.3 2131.35   273.6  2129.2
   286.7 2129.43   294.1 2130.57   302.3 2134.45     317 2144.43   318.7 2146.04
   326.8 2158.34   339.1  2169.1   351.4 2177.16   355.5 2181.19   358.4 2184.91
#Mann= 3 ,-1,0
       0      .1       0   112.6    .045       0   135.2      .1       0
Bank Sta=112.6,135.2
XS Rating Curve= 0 ,0
Exp/Cntr(USF)=0,0
Exp/Cntr=0.3,0.1

Type RM Length L Ch R = 1 ,8368    ,277.7,277,272.2
XS GIS Cut Line= 2
2199821.22898988396186.6713135432199877.44044105396519.255732967
#Sta/Elev= 30
       0 2195.96    10.7 2189.65    30.9 2175.39    59.3 2156.68    71.5 2149.14
    83.7 2143.07    87.7 2140.47    95.8 2132.51    99.9 2129.32     104  2128.1
   112.3 2126.71   120.2 2124.25     1272122.778   132.4 2121.76   148.6 2121.72
   164.8 2121.78   168.9 2122.07   171.3 2122.85     177 2125.01     181 2125.78
   201.3 2124.39   213.5 2125.41   233.8 2125.47   245.9 2123.86   254.1 2124.82
   258.1 2126.53   274.3 2130.05   286.5 2134.83   296.2  2140.7   337.3 2163.75
#Mann= 3 ,-1,0
       0      .1       0     127    .045       0   171.3      .1       0
Bank Sta=127,171.3
XS Rating Curve= 0 ,0
Exp/Cntr(USF)=0,0
Exp/Cntr=0.3,0.1

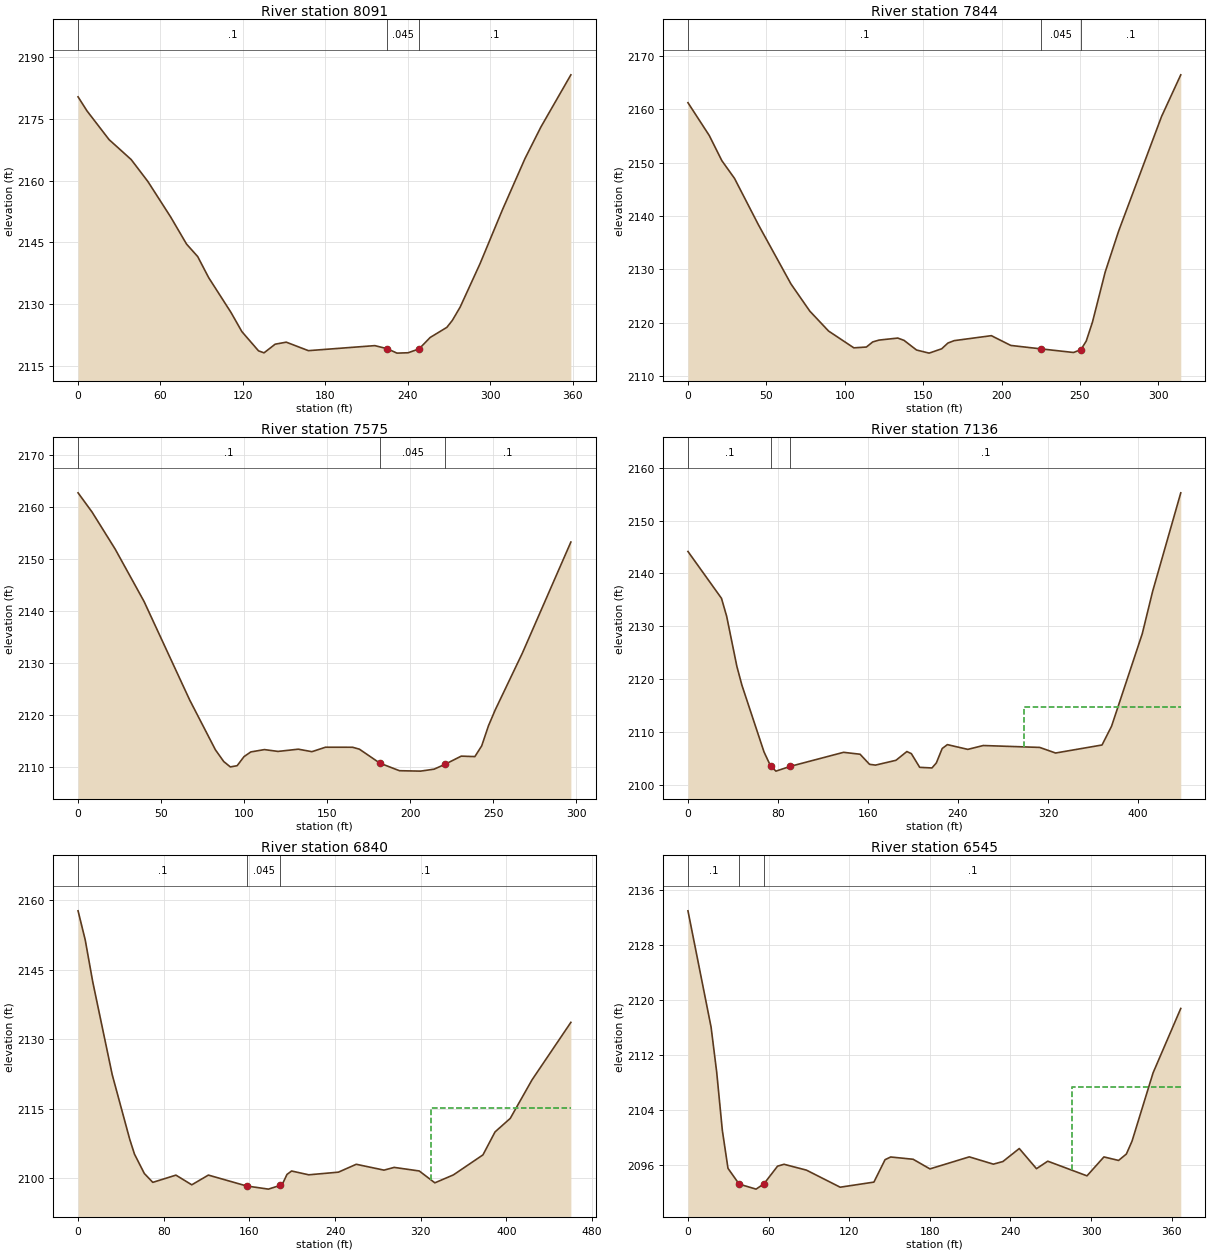
Type RM Length L Ch R = 1 ,8091    ,245.3,246.7,247.8
XS GIS Cut Line= 2
2199575.30389101396214.7770391282199619.80462319 396570.78289654
#Sta/Elev= 30
       0 2180.32     6.5 2176.91    22.6 2169.93    38.7 2165.09    50.8 2159.79
    67.4 2151.18      79 2144.58    87.1 2141.56    95.1 2136.44   111.3 2128.02
   119.3 2123.33   131.4 2118.67   135.4 2118.19   143.5 2120.29   151.6 2120.78
   167.7 2118.72   216.1 2119.94   225.1 2119.19   232.2 2118.12   240.3 2118.21
   248.3 2119.15   256.4 2121.93   268.5 2124.37   272.5 2126.06   278.2  2129.3
   292.7 2139.85   308.8 2152.77   325.4 2165.34     337 2173.01   358.8 2185.66
#Mann= 3 ,-1,0
       0      .1       0   225.1    .045       0   248.3      .1       0
Bank Sta=225.1,248.3
XS Rating Curve= 0 ,0
Exp/Cntr(USF)=0,0
Exp/Cntr=0.3,0.1

Type RM Length L Ch R = 1 ,7844    ,271.2,269.1,261.9
XS GIS Cut Line= 2
2199350.45808633396247.5670523112199366.85309292396561.414321345
#Sta/Elev= 30
       0  2161.2    13.6 2155.05    21.6 2150.35    29.7 2147.02      45  2138.3
    65.7 2127.25    77.7 2122.17    89.7 2118.43   105.8 2115.29   113.8 2115.44
   117.8 2116.39   121.8 2116.74   133.8 2117.12   137.8 2116.69   145.8 2114.88
   153.8  2114.3   161.8 2115.11   165.8 2116.19   169.8 2116.64   193.5 2117.57
   205.9 2115.74   224.92115.105   245.9 2114.42   250.6 2114.95     254 2116.55
     258 2120.13   266.1 2129.49   274.6  2137.1     302 2158.59   314.3 2166.42
#Mann= 3 ,-1,0
       0      .1       0   224.9    .045       0   250.6      .1       0
Bank Sta=224.9,250.6
XS Rating Curve= 0 ,0
Exp/Cntr(USF)=0,0
Exp/Cntr=0.3,0.1

Type RM Length L Ch R = 1 ,7575    ,449.2,439.3,428.4
XS GIS Cut Line= 2
2199060.03225528396287.3834968892199120.92799405396577.809327936
#Sta/Elev= 30
       0  2162.8     8.4 2159.11    22.3 2151.98    39.7 2141.88    67.2 2122.87
    82.7 2113.26    87.7    2111    91.7 2109.96    95.8  2110.2    99.9 2111.94
     104 2112.85   112.2  2113.3   120.4 2112.95   132.6 2113.38   140.8  2112.9
     149 2113.76   165.3 2113.75   169.4 2113.38   181.7 2110.69   193.5 2109.23
   206.2 2109.15   214.4 2109.53   221.2 2110.51   230.7 2112.04   238.9 2111.95
     243 2114.01   247.1  2117.9   251.1 2120.91   267.5  2131.9   296.7 2153.31
#Mann= 3 ,-1,0
       0      .1       0   181.7    .045       0   221.2      .1       0
Bank Sta=181.7,221.2
XS Rating Curve= 0 ,0
Exp/Cntr(USF)=0,0
Exp/Cntr=0.3,0.1

Type RM Length L Ch R = 1 ,7136    ,296.5,296,294.4
XS GIS Cut Line= 2
2198622.05136491396507.5450139732199006.16294791396718.337955862
#Sta/Elev= 30
       0 2144.15    29.8 2135.28    34.4 2131.88    43.5 2122.37      48  2118.8
    67.6 2106.19    73.5  2103.5    78.2 2102.55    91.1 2103.46   138.3 2106.11
     153 2105.75   161.4 2103.84   166.7 2103.69   184.9  2104.6   194.6 2106.26
   198.6 2105.86     206 2103.27   216.9 2103.15   220.8  2104.1     226 2106.83
   230.6 2107.57   248.8 2106.67   262.5  2107.4   312.7 2107.04   326.8 2105.98
   368.1  2107.5   376.6 2111.07   403.9  2128.6   413.1 2136.61   438.1 2155.26
#Mann= 3 ,-1,0
       0      .1       0    73.5    .045       0    91.1      .1       0
#XS Ineff= 2 , 0
                          298.77          2114.7
Permanent Ineff=
       F       F
Bank Sta=73.5,91.1
XS Rating Curve= 0 ,0
Exp/Cntr(USF)=0,0
Exp/Cntr=0.3,0.1

Type RM Length L Ch R = 1 ,6840    ,295.2,294.8,295.3
XS GIS Cut Line= 2
2198467.46987419396765.1808318372198893.74004557396938.499472945
#Sta/Elev= 30
       0 2157.76     6.7 2151.48    13.7 2142.45    31.9  2122.4    48.3 2108.42
    52.7 2105.25    61.9 2101.07    69.8 2099.16    91.4 2100.72   106.2 2098.63
   121.7 2100.73   157.42098.379   177.8  2097.7     1892098.535   190.8 2098.77
   195.1 2100.87   199.4 2101.61   215.4 2100.79   243.1 2101.36   259.8 2103.06
   285.7  2101.8   295.2 2102.39   318.6 2101.62   333.2 2099.06   350.5 2100.77
   378.1 2105.09   389.4 2110.05   403.6 2112.97   423.9 2121.27   460.2 2133.69
#Mann= 3 ,-1,0
       0      .1       0   157.4    .045       0     189      .1       0
#XS Ineff= 2 , 0
                          329.91         2115.16
Permanent Ineff=
       F       F
Bank Sta=157.4,189
XS Rating Curve= 0 ,0
Exp/Cntr(USF)=0,0
Exp/Cntr=0.3,0.1

Type RM Length L Ch R = 1 ,6545    ,309.2,311.2,317.5
XS GIS Cut Line= 2
2198427.65342962 397062.633094282198778.97499943397168.029565224
#Sta/Elev= 30
       0 2132.92    17.2 2116.03    21.4 2109.45    25.6 2100.99    29.8 2095.49
    38.1  2093.2    50.7 2092.47    56.6 2093.25    66.7 2095.81    71.5 2096.08
    88.2 2095.23   113.3 2092.75   138.4 2093.49   146.7 2096.75   150.9 2097.14
   167.6 2096.81   180.1 2095.41   209.4 2097.16   227.3  2096.1   234.4 2096.48
   246.6 2098.37   259.4 2095.44   267.8 2096.53     297  2094.4   309.6 2097.15
   320.5 2096.64   326.3 2097.57   330.5 2099.43   346.2 2109.38   366.8 2118.73
#Mann= 3 ,-1,0
       0      .1       0    38.1    .045       0    56.6      .1       0
#XS Ineff= 2 , 0
                          285.63         2107.34
Permanent Ineff=
       F       F
Bank Sta=38.1,56.6
XS Rating Curve= 0 ,0
Exp/Cntr(USF)=0,0
Exp/Cntr=0.3,0.1

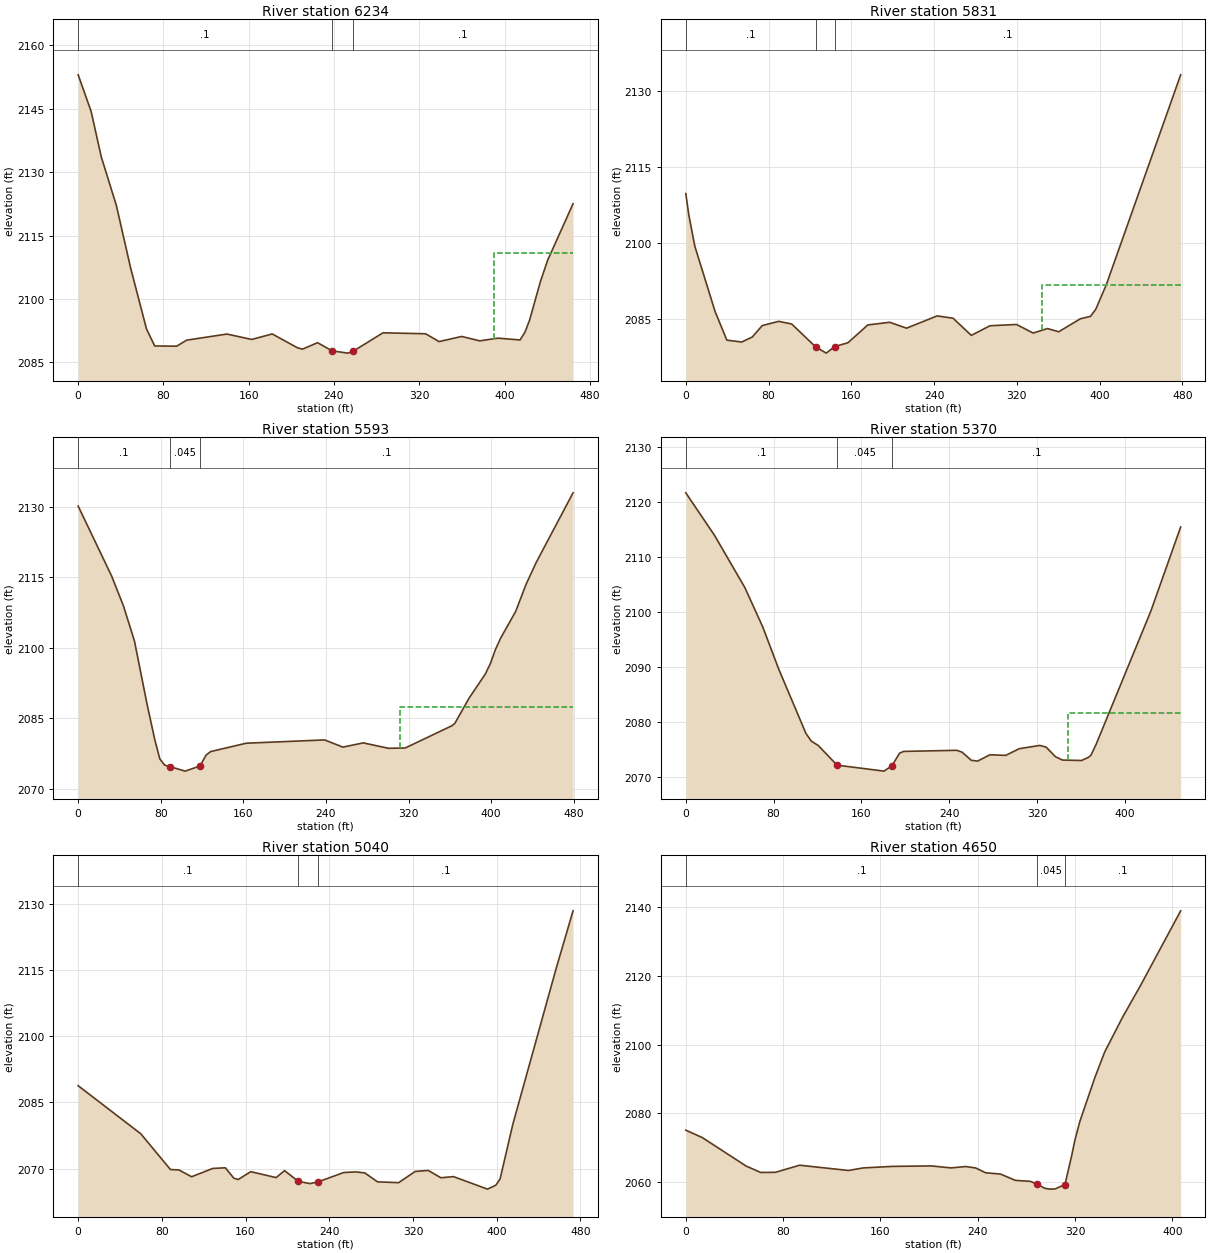
Type RM Length L Ch R = 1 ,6234    ,402,403,405.5
XS GIS Cut Line= 3
2198285.86989344397239.0187028862198542.41847576397399.901801301
2198694.65782267397453.771108673
#Sta/Elev= 30
       0 2152.99    12.2 2144.33    21.6 2133.67    35.8 2122.16    49.2 2107.37
    64.1 2092.94    71.8 2088.91    92.4 2088.85   101.9 2090.28   139.6 2091.72
   162.8 2090.44   182.1 2091.74   205.7 2088.48   210.5 2088.15   224.6 2089.68
   238.3 2087.75     253 2087.21   257.7 2087.61     286 2092.01   325.9 2091.79
   338.6 2089.94   359.8 2091.15   376.8 2090.11   393.8 2090.75   414.6 2090.32
   419.2 2092.16   423.5 2094.99   433.7 2104.13   440.5 2109.18   464.3 2122.51
#Mann= 3 ,-1,0
       0      .1       0   238.3    .045       0   257.7      .1       0
#XS Ineff= 2 , 0
                          390.17         2110.79
Permanent Ineff=
       F       F
Bank Sta=238.3,257.7
XS Rating Curve= 0 ,0
Exp/Cntr(USF)=0,0
Exp/Cntr=0.3,0.1

Type RM Length L Ch R = 1 ,5831    ,238.7,238.6,237
XS GIS Cut Line= 2
2198113.80616058397535.7461416292198488.54916838397833.198404072
#Sta/Elev= 30
       0 2109.74       3 2105.45     8.7  2099.4    28.3  2086.5    39.7 2080.84
    54.1 2080.47    64.3 2081.46    73.9 2083.71    89.8 2084.55   102.4 2084.02
   125.6  2079.5   135.8 2078.28   143.9 2079.57   156.7 2080.32     176 2083.84
   197.1 2084.36   213.4  2083.2     243 2085.62   258.4 2085.16     276 2081.78
   294.1 2083.68   319.7 2083.93   335.8 2082.24   349.7 2083.13   360.5 2082.49
   381.4 2085.05   391.2 2085.53   396.3 2086.92   406.5 2091.76   478.4 2133.16
#Mann= 3 ,-1,0
       0      .1       0   125.6    .045       0   143.9      .1       0
#XS Ineff= 2 , 0
                          344.57          2091.8
Permanent Ineff=
       F       F
Bank Sta=125.6,143.9
XS Rating Curve= 0 ,0
Exp/Cntr(USF)=0,0
Exp/Cntr=0.3,0.1

Type RM Length L Ch R = 1 ,5593    ,216.9,222.8,231.1
XS GIS Cut Line= 2
2197971.91348283397728.3722107992198361.20705652398007.947898852
#Sta/Elev= 30
       0  2130.1    32.3  2115.3    43.8 2108.94    54.5 2101.47    66.7 2088.05
    74.2 2080.49    79.1 2076.38    83.7 2075.08      89 2074.74   103.7 2073.79
     118 2074.89     124 2077.22   128.4 2077.95   162.8 2079.72   238.7 2080.42
   256.4 2078.89   276.1 2079.79   300.7 2078.64   316.8 2078.71   361.9 2083.42
   364.8 2083.93   378.5 2089.26   394.3 2094.41   399.2 2096.62   404.1 2099.61
   409.1 2102.01   423.8 2107.75   433.7 2113.43   443.5 2118.07   479.3 2132.92
#Mann= 3 ,-1,0
       0      .1       0      89    .045       0     118      .1       0
#XS Ineff= 2 , 0
                          311.58         2087.37
Permanent Ineff=
       F       F
Bank Sta=89,118
XS Rating Curve= 0 ,0
Exp/Cntr(USF)=0,0
Exp/Cntr=0.3,0.1

Type RM Length L Ch R = 1 ,5370    ,319.3,329.6,339.4
XS GIS Cut Line= 2
2197811.66961054397835.5405478712198097.41115399398184.519973886
#Sta/Elev= 30
       0 2121.61    26.1 2113.92    53.8 2104.42    70.3 2097.19    84.8 2089.56
   109.5 2077.92   114.4 2076.53   120.8 2075.72   137.82072.168   180.6 2071.08
   187.92072.052   194.8 2074.34   198.6 2074.66     247 2074.86   251.7 2074.53
   260.2 2073.05   265.9  2072.9   277.2 2074.05   291.5 2073.94   303.9 2075.15
   322.6 2075.75   328.4 2075.44   336.9  2073.7   343.3 2073.09   360.7 2073.01
     367 2073.59   369.2 2073.96   373.9 2075.92   423.8 2100.12     451 2115.41
#Mann= 3 ,-1,0
       0      .1       0   137.8    .045       0   187.9      .1       0
#XS Ineff= 2 , 0
                          348.24          2081.7
Permanent Ineff=
       F       F
Bank Sta=137.8,187.9
XS Rating Curve= 0 ,0
Exp/Cntr(USF)=0,0
Exp/Cntr=0.3,0.1

Type RM Length L Ch R = 1 ,5040    ,385.2,390.2,396.9
XS GIS Cut Line= 2
2197607.90310005397905.8048618342197673.48312641398374.233621586
#Sta/Elev= 30
       0 2088.77    59.9 2077.88    88.2 2069.79    96.3 2069.71   108.4 2068.16
   128.6 2070.04   140.7 2070.19   148.8 2067.83   152.9 2067.53     165 2069.31
   189.2 2067.97   197.3 2069.55   210.3 2067.14   221.5 2066.61   229.6 2067.02
   253.8 2069.12   265.4 2069.26     274 2069.03   286.1 2067.01   306.3 2066.82
   322.1 2069.36   334.6 2069.59   346.7 2067.93   358.8 2068.19   391.2 2065.36
   399.2 2066.25   403.3 2067.69   415.4    2080   456.7 2115.17     473 2128.35
#Mann= 3 ,-1,0
       0      .1       0   210.3    .045       0   229.6      .1       0
Bank Sta=210.3,229.6
XS Rating Curve= 0 ,0
Exp/Cntr(USF)=0,0
Exp/Cntr=0.3,0.1

Type RM Length L Ch R = 1 ,4650    ,280.5,277.5,273.1
XS GIS Cut Line= 3
2197336.21441939397959.674169205 2197324.5037004398170.467111094
2197287.02939962398362.522902592
#Sta/Elev= 30
       0 2075.14    13.5    2073    49.6 2064.71    61.6 2062.85    73.6 2062.88
    93.6 2064.95   133.7 2063.42   145.7 2064.16   169.8 2064.61   201.8 2064.75
     218 2064.17   230.2 2064.57   238.3 2064.15   246.5 2062.75   258.7 2062.38
   270.9 2060.55   283.2 2060.26   288.7 2059.46   295.1 2058.24   299.5    2058
   303.5 2058.05   311.7 2059.34   317.3 2067.87   319.8 2072.16   323.9 2077.64
   336.1 2090.27   344.3 2097.83     359 2107.94     374 2117.32   406.8  2138.9
#Mann= 3 ,-1,0
       0      .1       0   288.7    .045       0   311.7      .1       0
Bank Sta=288.7,311.7
XS Rating Curve= 0 ,0
Exp/Cntr(USF)=0,0
Exp/Cntr=0.3,0.1

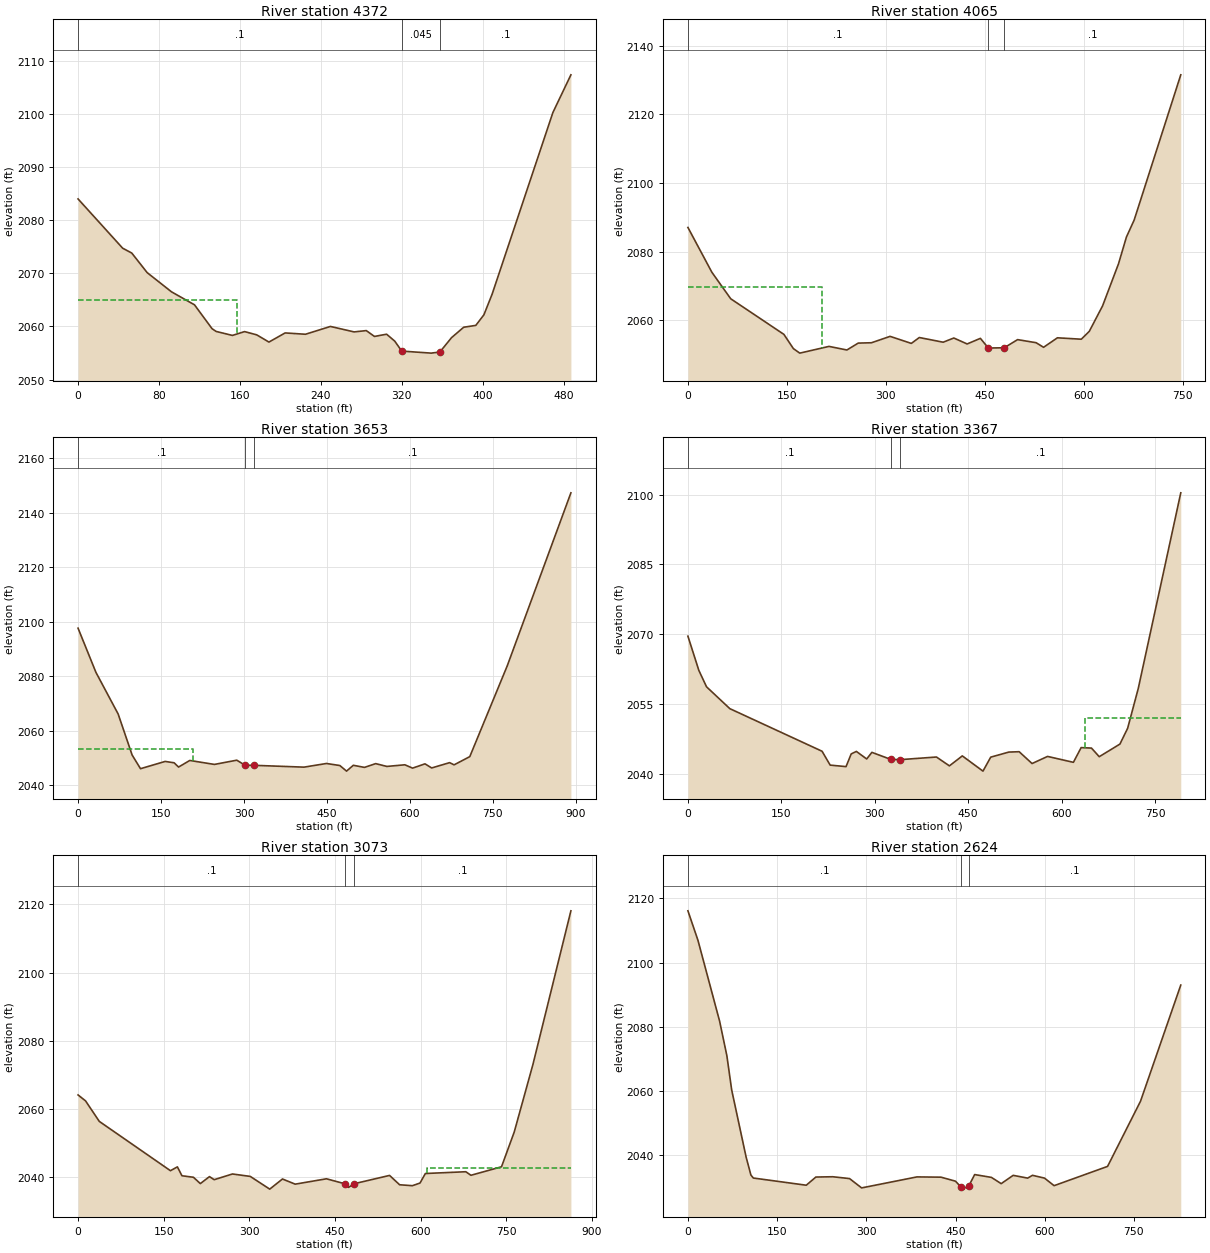
Type RM Length L Ch R = 1 ,4372    ,310.1,307.2,299.7
XS GIS Cut Line= 2
2197067.28352672397845.0312468012197031.22177767398330.915865551
#Sta/Elev= 30
       0 2083.99    44.1 2074.72    53.1 2073.81    68.3 2070.13    92.4 2066.51
   115.1 2064.07   132.5 2059.57   136.5 2059.06   152.6 2058.31   164.6 2059.03
   176.6 2058.42   188.7 2057.06   204.7 2058.78   224.8 2058.53   249.5    2060
   272.9 2058.97   284.9 2059.22     293 2058.12     305 2058.54     313 2057.25
     3202055.365   349.1 2054.98   357.72055.194   369.2 2057.89   381.2 2059.85
   393.2  2060.2   401.2 2062.19   409.3 2066.06   469.4 2100.25   487.2 2107.34
#Mann= 3 ,-1,0
       0      .1       0     320    .045       0   357.7      .1       0
#XS Ineff= 2 , 0
          156.68 2064.92
Permanent Ineff=
       F       F
Bank Sta=320,357.7
XS Rating Curve= 0 ,0
Exp/Cntr(USF)=0,0
Exp/Cntr=0.3,0.1

Type RM Length L Ch R = 1 ,4065    ,408,412.6,411.1
XS GIS Cut Line= 2
 2196695.6233988397772.6642662052196780.68752113398515.020584374
#Sta/Elev= 30
       0 2087.06    36.3 2074.02    64.9  2066.3   145.5 2055.94   159.9 2051.79
   169.6 2050.48   213.9 2052.44     241 2051.39   258.2  2053.4   278.3  2053.5
   306.5 2055.36   338.7 2053.31   350.8 2055.02     387 2053.66   403.1 2054.88
   423.3 2053.15   443.4 2054.78   455.5 2051.96   479.6 2052.04   499.8 2054.41
   527.9 2053.51   539.2 2052.18   560.2 2054.94   596.4 2054.53   608.5 2056.82
   628.6 2064.21   652.8 2076.47   664.8 2084.27   676.5 2089.19   747.2 2131.48
#Mann= 3 ,-1,0
       0      .1       0   455.5    .045       0   479.6      .1       0
#XS Ineff= 2 , 0
          202.76 2069.65
Permanent Ineff=
       F       F
Bank Sta=455.5,479.6
XS Rating Curve= 0 ,0
Exp/Cntr(USF)=0,0
Exp/Cntr=0.3,0.1

Type RM Length L Ch R = 1 ,3653    ,283.9,285.3,279.3
XS GIS Cut Line= 4
2196364.80366891397756.9934158642196357.13438526397842.451147962
2196457.93068466398479.001690896 2196564.2050438398599.519005393
#Sta/Elev= 30
       0 2097.63    32.3 2081.44    72.5 2066.16    97.8 2051.12   112.9 2046.12
   157.4 2048.78   173.6 2048.29   181.7 2046.72     202 2049.14   246.5 2047.69
     287 2049.24     302 2047.38   318.72047.352   408.5 2046.69     449 2048.03
   473.3 2047.28   485.4 2045.23   497.6 2047.37   517.8  2046.6   538.1 2047.98
   558.3 2046.95   590.8 2047.55   604.8 2046.33   627.2  2047.9   639.3 2046.39
   671.7 2048.34   679.8 2047.53   708.2 2050.54   775.9 2083.81     891 2147.23
#Mann= 3 ,-1,0
       0      .1       0     302    .045       0   318.7      .1       0
#XS Ineff= 2 , 0
          207.32 2053.49
Permanent Ineff=
       F       F
Bank Sta=302,318.7
XS Rating Curve= 0 ,0
Exp/Cntr(USF)=0,0
Exp/Cntr=0.3,0.1

Type RM Length L Ch R = 1 ,3367    ,295.1,294.3,289.2
XS GIS Cut Line= 2
2196088.28666887397860.3053664712196299.07961076398627.591674946
#Sta/Elev= 30
       0 2069.57    17.5 2062.23    29.9 2058.69    67.3    2054   215.4 2044.85
   228.4 2041.87   253.9 2041.55   262.2 2044.28   270.5 2044.81   287.1 2043.19
   295.4 2044.61     326 2043.09   341.1 2043.05   399.1 2043.61   419.9 2041.71
   440.6 2043.85   473.8 2040.58   486.2 2043.58   515.3 2044.67   531.9 2044.75
   552.6 2042.21   577.5 2043.74     619 2042.47   631.4 2045.63     648 2045.53
   660.5 2043.68   693.7 2046.39   706.1 2049.79   723.1 2058.31   791.4 2100.36
#Mann= 3 ,-1,0
       0      .1       0     326    .045       0   341.1      .1       0
#XS Ineff= 2 , 0
                          636.85         2051.92
Permanent Ineff=
       F       F
Bank Sta=326,341.1
XS Rating Curve= 0 ,0
Exp/Cntr(USF)=0,0
Exp/Cntr=0.3,0.1

Type RM Length L Ch R = 1 ,3073    ,444.7,448.7,451.4
XS GIS Cut Line= 3
2195868.49145557 397908.187864962195896.97736627398191.951360003
2196152.25495061 398710.17581234
#Sta/Elev= 30
       0 2064.14    13.1  2062.4    37.2 2056.38   161.8 2041.92   173.9 2043.05
   181.9 2040.44     202    2040   214.1 2038.14   230.1 2040.19   238.3 2039.29
   270.3 2040.96   301.5 2040.25   335.6 2036.52   357.9 2039.49   380.2 2037.98
   434.9 2039.55   466.92038.104   473.7 2037.04     483 2038.09   545.4 2040.54
     563  2037.8   585.3 2037.53   598.7  2038.3   608.1  2041.1   678.9 2041.62
   687.9 2040.58   741.4 2043.07   763.7 2053.28   796.4 2073.07   862.9 2118.13
#Mann= 3 ,-1,0
       0      .1       0   466.9    .045       0     483      .1       0
#XS Ineff= 2 , 0
                          610.89         2042.77
Permanent Ineff=
       F       F
Bank Sta=466.9,483
XS Rating Curve= 0 ,0
Exp/Cntr(USF)=0,0
Exp/Cntr=0.3,0.1

Type RM Length L Ch R = 1 ,2624    ,287.9,289.8,288.3
XS GIS Cut Line= 3
2195523.36158461397980.4573433482195626.65012614 398657.10268681
2195643.51356149398800.441887294
#Sta/Elev= 30
       0 2116.14    16.9 2106.93    53.3 2081.71    65.5 2070.95    73.6 2060.26
    97.8 2039.38   105.9 2033.73     110 2032.79     199 2030.55   215.2  2033.1
   243.5 2033.19   271.8 2032.62   292.1 2029.71   385.1 2033.14   425.6 2033.06
   449.9 2031.81   458.62030.111     462 2029.33   472.6 2030.41   482.2 2033.87
   510.4 2032.99   526.8 2031.04     547 2033.63   571.3 2032.76   579.4 2033.64
   599.6 2032.77   615.8 2030.41   705.7 2036.42   761.1 2056.75   828.8 2092.98
#Mann= 3 ,-1,0
       0      .1       0   458.6    .045       0   472.6      .1       0
Bank Sta=458.6,472.6
XS Rating Curve= 0 ,0
Exp/Cntr(USF)=0,0
Exp/Cntr=0.3,0.1