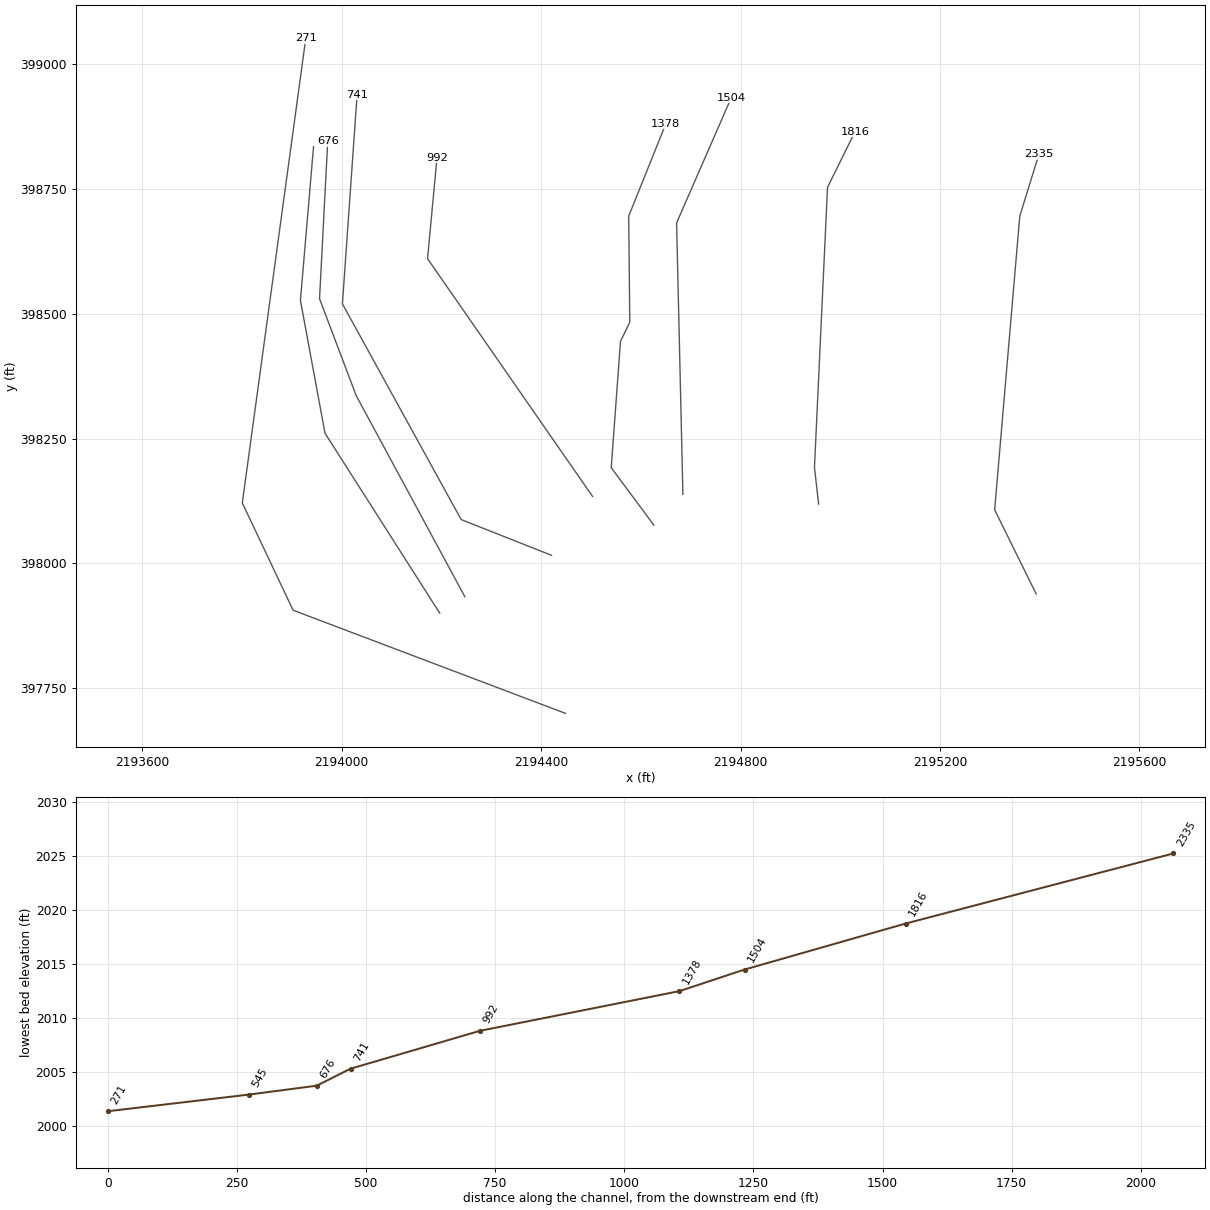
HEC-RAS study LAURELRN1.prj: LAURELRN1

--- LAURELRN1.g01 (geometry) --- (continued)

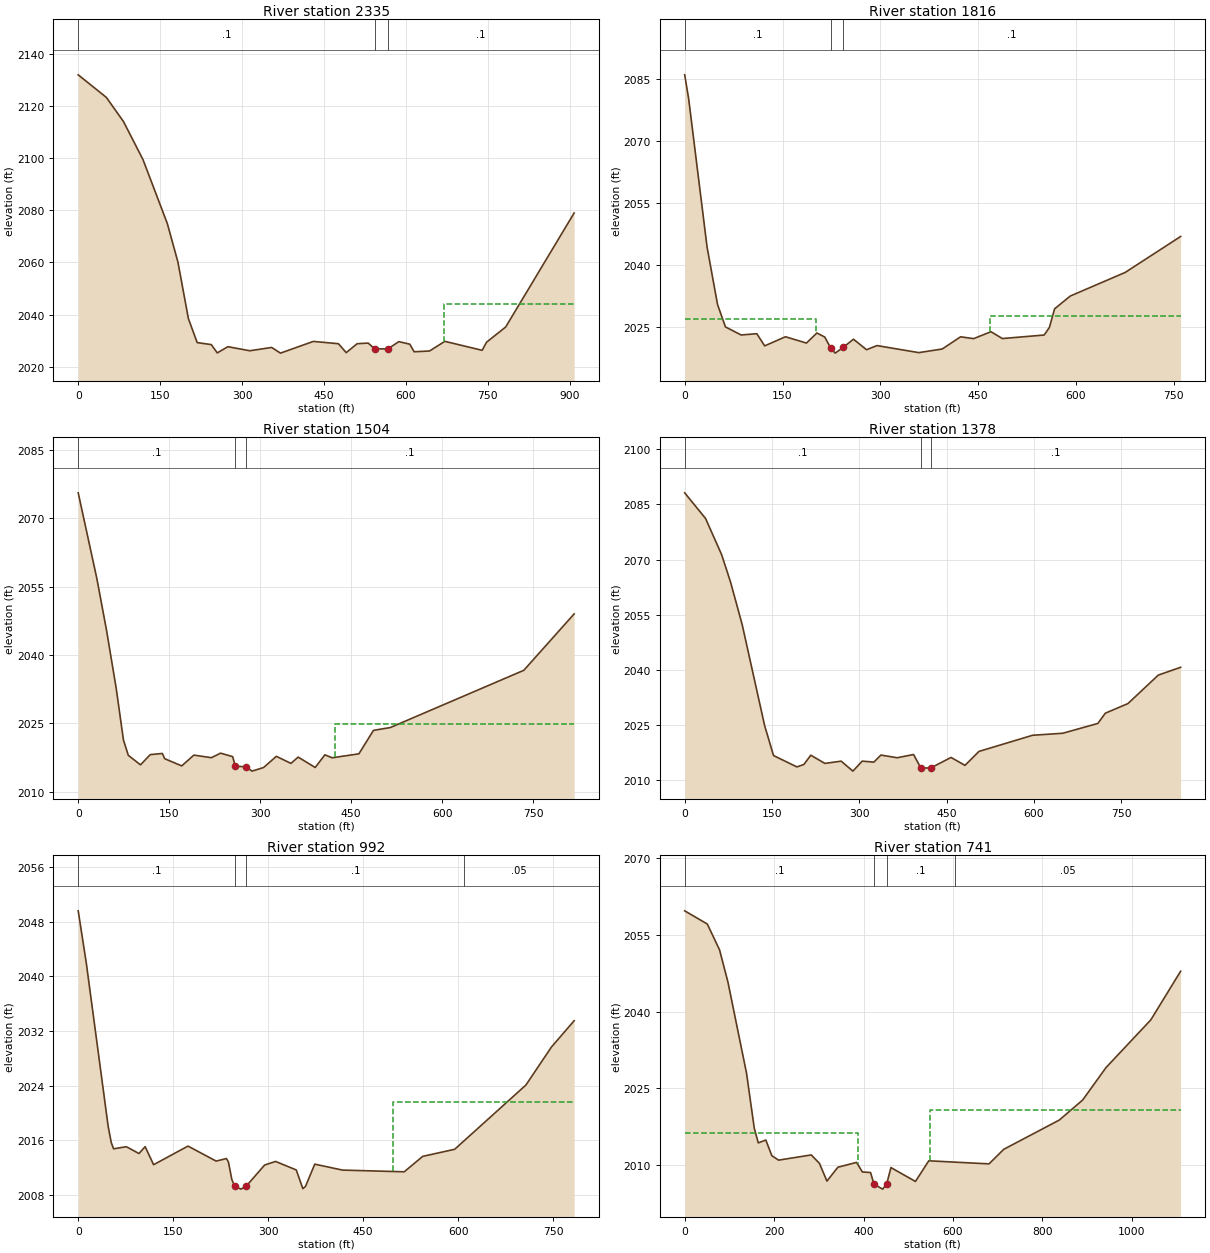
Type RM Length L Ch R = 1 ,2335    ,516,518.5,513.3
XS GIS Cut Line= 4
2195392.99586928 397938.864999562195309.72936109398107.589239855
2195360.12751078 398695.932856992195398.47392903398819.737007337
#Sta/Elev= 30
       0 2131.95    51.6 2123.28    82.9 2114.03   118.6 2099.46   163.2 2074.91
   182.6 2060.17   201.8 2038.46   217.9 2029.25   243.7 2028.48   254.7  2025.3
   274.1 2027.68   314.2 2026.12   354.3 2027.39   370.4 2025.21   430.6  2029.7
   476.6 2028.82   490.8  2025.4   510.9 2028.82     531 2029.06     543 2026.88
   567.1 2026.81   587.2 2029.62   607.3 2028.64   615.3 2025.73   643.4 2026.02
   671.5 2029.73   739.8 2026.29   747.8 2029.38   782.9 2035.23   908.3 2078.96
#Mann= 3 ,-1,0
       0      .1       0     543    .045       0   567.1      .1       0
#XS Ineff= 2 , 0
                          669.74         2044.09
Permanent Ineff=
       F       F
Bank Sta=543,567.1
XS Rating Curve= 0 ,0
Exp/Cntr(USF)=0,0
Exp/Cntr=0.3,0.1

Type RM Length L Ch R = 1 ,1816    ,310.3,311.7,310.2
XS GIS Cut Line= 4
2194956.59123807398119.0681344122194948.31332566398192.775153287
2194974.47977459398753.5486981042195029.71519558 398865.44173766
#Sta/Elev= 30
       0 2085.92     6.1 2080.15    34.3 2044.36    50.4 2030.45    62.5 2025.06
    86.6 2023.11   110.6 2023.42   122.6 2020.48   154.5 2022.68   186.7 2021.16
   202.7 2023.59   214.7 2022.62   223.6 2020.03   230.7 2018.73   242.8 2020.09
   258.8 2022.09   278.8 2019.55   294.8 2020.55   358.9 2018.85   394.9 2019.73
     423 2022.67     443 2022.23   469.6  2023.9     487 2022.25   551.1  2023.1
   559.1 2024.91   567.1 2029.42   591.1 2032.51   675.3 2038.21   760.3 2046.89
#Mann= 3 ,-1,0
       0      .1       0   223.6    .045       0   242.8      .1       0
#XS Ineff= 2 , 0
          201.92 2027.09  468.73         2027.69
Permanent Ineff=
       F       F
Bank Sta=223.6,242.8
XS Rating Curve= 0 ,0
Exp/Cntr(USF)=0,0
Exp/Cntr=0.3,0.1

Type RM Length L Ch R = 1 ,1504    ,130.9,126.5,117.9
XS GIS Cut Line= 3
2194684.40567589398138.5520497642194671.75809938398682.397839837
2194781.37042916398933.241440684
#Sta/Elev= 30
       0  2075.6    30.6 2056.86    46.6 2045.49    62.6  2032.7    74.6 2021.32
    82.6 2017.95   102.7 2015.86   118.7  2018.1   138.7 2018.36   142.7  2017.2
   170.7 2015.63   190.7    2018   219.6 2017.43   234.7 2018.43   254.7 2017.66
   259.12015.529   276.32015.457   286.7 2014.48   305.6 2015.27   326.7 2017.73
   350.7 2016.18   362.7 2017.56   390.7 2015.28   406.7 2018.06   418.7 2017.41
   462.8 2018.28   486.8 2023.43   514.8 2024.06   734.7 2036.62   817.7 2049.01
#Mann= 3 ,-1,0
       0      .1       0   259.1    .045       0   276.3      .1       0
#XS Ineff= 2 , 0
                          423.96         2024.83
Permanent Ineff=
       F       F
Bank Sta=259.1,276.3
XS Rating Curve= 0 ,0
Exp/Cntr(USF)=0,0
Exp/Cntr=0.3,0.1

Type RM Length L Ch R = 1 ,1378    ,373.5,386.3,401.6
XS GIS Cut Line= 6
 2194626.0675043398076.912105256 2194540.6097722398191.951360003
2194559.23517535398445.037720447 2194577.8605785398483.384138696
 2194575.6693546 398695.93285699 2194650.1709672398881.091276535
#Sta/Elev= 30
       0 2088.17    35.9 2081.19    63.5 2071.35    78.7 2063.95    98.8 2052.32
   137.3 2024.89   152.6 2016.72   192.7 2013.63   204.7 2014.28   216.7 2016.81
   240.8 2014.58   268.9 2015.19   288.9 2012.48     305  2015.2     325 2014.93
   337.1 2016.85   365.1 2016.12   393.2    2017   405.72013.312   422.92013.359
   457.5  2016.2   481.5 2014.05   505.5 2017.84   597.6 2022.23   649.5 2022.78
   709.7 2025.45   722.6 2028.24   761.4 2030.85   813.5 2038.59   851.9 2040.72
#Mann= 3 ,-1,0
       0      .1       0   405.7    .045       0   422.9      .1       0
Bank Sta=405.7,422.9
XS Rating Curve= 0 ,0
Exp/Cntr(USF)=0,0
Exp/Cntr=0.3,0.1

Type RM Length L Ch R = 1 ,992     ,245.8,250.3,247
XS GIS Cut Line= 3
2194503.12374587398134.3361909262194172.17882711398610.728239594
2194191.15019188398813.089463807
#Sta/Elev= 30
       0 2049.61    12.8 2041.94    47.3 2018.02    52.2 2015.63    55.9 2014.72
      76 2015.03      96 2014.03   105.7 2015.04   119.1 2012.39   173.4 2015.12
   217.8 2012.92   234.1 2013.29   237.2 2012.81   242.7  2010.2     247 2009.25
   257.1 2008.81   265.7 2009.28   294.4 2012.34   311.7 2012.87   344.4 2011.62
   354.8 2008.88     359 2009.21   373.6 2012.47   417.5  2011.6   514.9 2011.35
   544.1 2013.61   594.6 2014.65   707.1 2024.07   747.6 2029.66   783.3  2033.5
#Mann= 4 ,-1,0
       0      .1       0     247    .045       0   265.7      .1       0
  610.06     .05       0
#XS Ineff= 2 , 0
                          496.47         2021.64
Permanent Ineff=
       F       F
Bank Sta=247,265.7
XS Rating Curve= 0 ,0
Exp/Cntr(USF)=0,0
Exp/Cntr=0.3,0.1

Type RM Length L Ch R = 1 ,741     ,66.1,65.6,65.3
XS GIS Cut Line= 4
2194420.91449853398016.2921434692194239.63256851398087.961743711
2194001.43654418398520.0872745822194030.94755604398939.565228941
#Sta/Elev= 30
       0 2059.75    50.6 2057.17      78 2052.11    96.8 2045.79   138.4 2027.95
   155.6 2017.23   164.6 2014.35   181.4 2014.92   194.9 2011.85     210 2010.98
   283.1    2012   301.4 2010.34   318.1 2006.88   342.5 2009.59   384.4 2010.54
   397.3 2008.67   415.6 2008.56   423.3 2006.27   442.8 2005.31   451.7 2006.32
   461.2 2009.53     516 2006.81   545.8 2010.85   680.5 2010.25   713.5  2013.1
   837.6 2018.82     890 2022.75   942.1 2029.09  1042.3 2038.42  1108.9 2047.93
#Mann= 4 ,-1,0
       0      .1       0   423.3    .045       0   451.7      .1       0
  604.94     .05       0
#XS Ineff= 2 , 0
           386.7 2016.36  547.61          2020.7
Permanent Ineff=
       F       F
Bank Sta=423.3,451.7
XS Rating Curve= 0 ,0
Exp/Cntr(USF)=0,0
Exp/Cntr=0.3,0.1

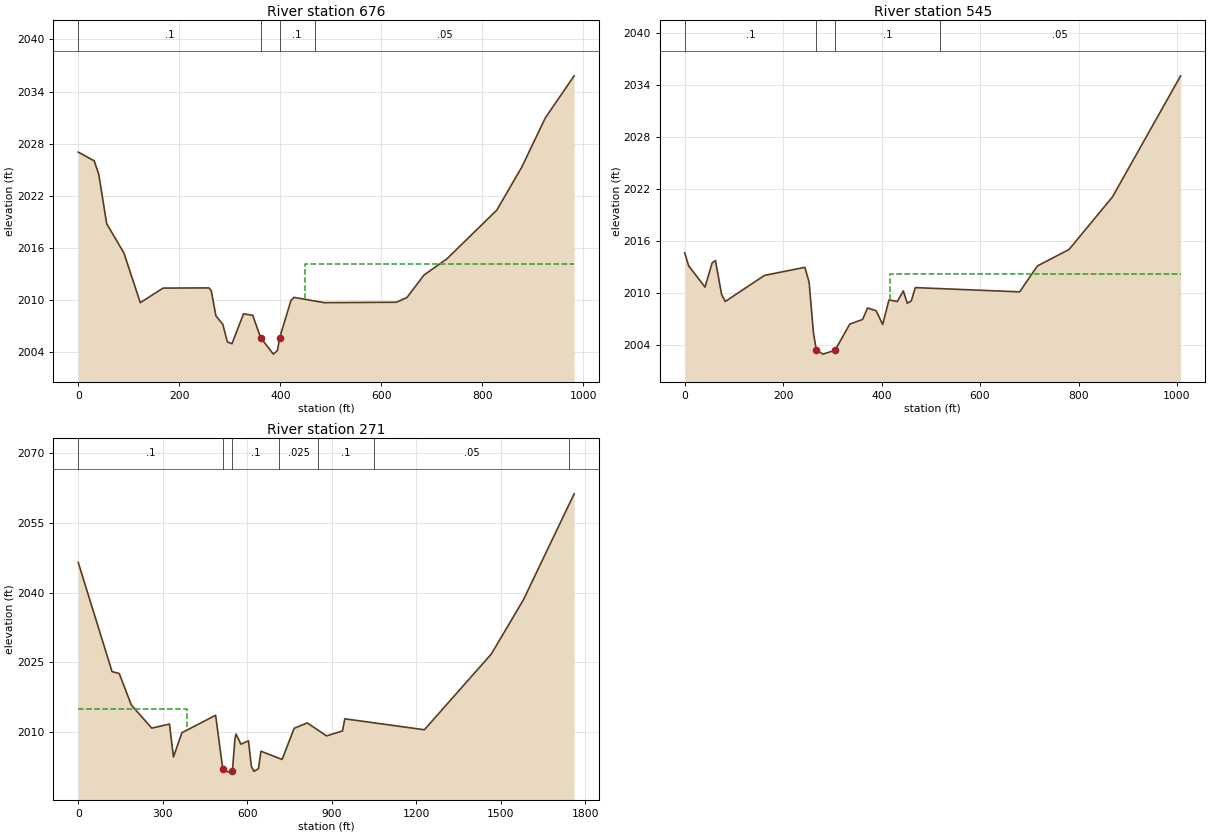
Type RM Length L Ch R = 1 ,676     ,135.5,131.1,121.5
XS GIS Cut Line= 4
2194246.98576961 397933.386939812194028.95899157398336.572137399
2193955.55299092398530.4954525442193971.98717017398846.031694136
#Sta/Elev= 30
       0 2027.02    31.6 2026.02    40.7 2024.45    56.4 2018.77    90.5 2015.39
   122.9 2009.67     168 2011.35     259 2011.37   263.5    2011   272.6 2008.15
   286.2 2007.18   295.3 2005.14   304.4 2004.94   327.2 2008.38   345.4 2008.22
   361.12005.645   386.3 2003.74   394.5 2004.17   398.5 2005.58     421  2009.9
   426.9 2010.28   487.4 2009.67   630.1 2009.72   650.8 2010.27   684.4 2012.85
   729.8 2014.72   828.5 2020.33   878.3 2025.32   924.7 2030.97   981.7 2035.81
#Mann= 4 ,-1,0
       0      .1       0   361.1    .045       0   398.5      .1       0
  468.36     .05       0
#XS Ineff= 2 , 0
                          449.58         2014.07
Permanent Ineff=
       F       F
Bank Sta=361.1,398.5
XS Rating Curve= 0 ,0
Exp/Cntr(USF)=0,0
Exp/Cntr=0.3,0.1

Type RM Length L Ch R = 1 ,545     ,262.2,273.3,278.1
XS GIS Cut Line= 4
2194196.58761991397900.5185813112193966.50911042398260.974912851
2193917.20657267398527.2086166942193943.50125947398835.075574637
#Sta/Elev= 30
       0 2014.61     8.2  2013.1    41.3 2010.66    55.8 2013.45    62.5 2013.73
    75.1 2009.78    82.5    2009   162.1 2012.01   244.1 2012.94   252.8 2011.22
   261.5  2005.4   267.3 2003.41   280.8 2002.92   305.6 2003.37   335.3 2006.39
   361.4 2006.92   371.5 2008.25   388.9 2007.93   402.2 2006.34     415 2009.19
   431.9 2008.99   444.1 2010.22   452.2 2008.79   460.4 2009.07   468.5  2010.6
   680.4 2010.11   716.4  2013.1   780.7    2015     869 2021.07  1007.4 2035.05
#Mann= 4 ,-1,0
       0      .1       0   267.3    .045       0   305.6      .1       0
  517.63     .05       0
#XS Ineff= 2 , 0
                          417.13         2012.16
Permanent Ineff=
       F       F
Bank Sta=267.3,305.6
XS Rating Curve= 0 ,0
Exp/Cntr(USF)=0,0
Exp/Cntr=0.3,0.1

Type RM Length L Ch R = 1 ,271     ,,,
XS GIS Cut Line= 4
2194448.57565261397699.750561285 2193902.4914228397906.300554947
2193800.63115195398121.3389045132193927.95649051399052.228601977
#Sta/Elev= 30
       0 2046.53   120.2 2023.02   145.8  2022.6   188.6 2015.83   261.3 2010.85
   324.1 2011.73   338.3 2004.65   368.2 2009.86     488 2013.62   513.6 2001.98
     535 2001.38   547.8 2001.69   556.4 2008.47   560.7 2009.58   577.8 2007.39
   604.7 2008.13   614.8 2002.65   623.8 2001.55   640.1 2002.12     649 2005.88
   724.2 2004.11   766.8 2010.81   813.5 2011.97   882.2 2009.18   938.7 2010.25
   946.8 2012.86  1229.4  2010.5  1467.6 2026.84  1581.3  2038.5  1761.3 2061.29
#Mann= 7 ,-1,0
       0      .1       0   513.6    .045       0   547.8      .1       0
  713.84    .025       0  851.78      .1       0 1051.78     .05       0
 1741.78      .1       0
#XS Ineff= 2 , 0
          385.35 2015.05
Permanent Ineff=
       F       F
Bank Sta=513.6,547.8
XS Rating Curve= 0 ,0
Exp/Cntr(USF)=0,0
Exp/Cntr=0.3,0.1
LCMann Table=0

Chan Stop Cuts=-1
Use User Specified Reach Order=0
Composite Channel Slope=5